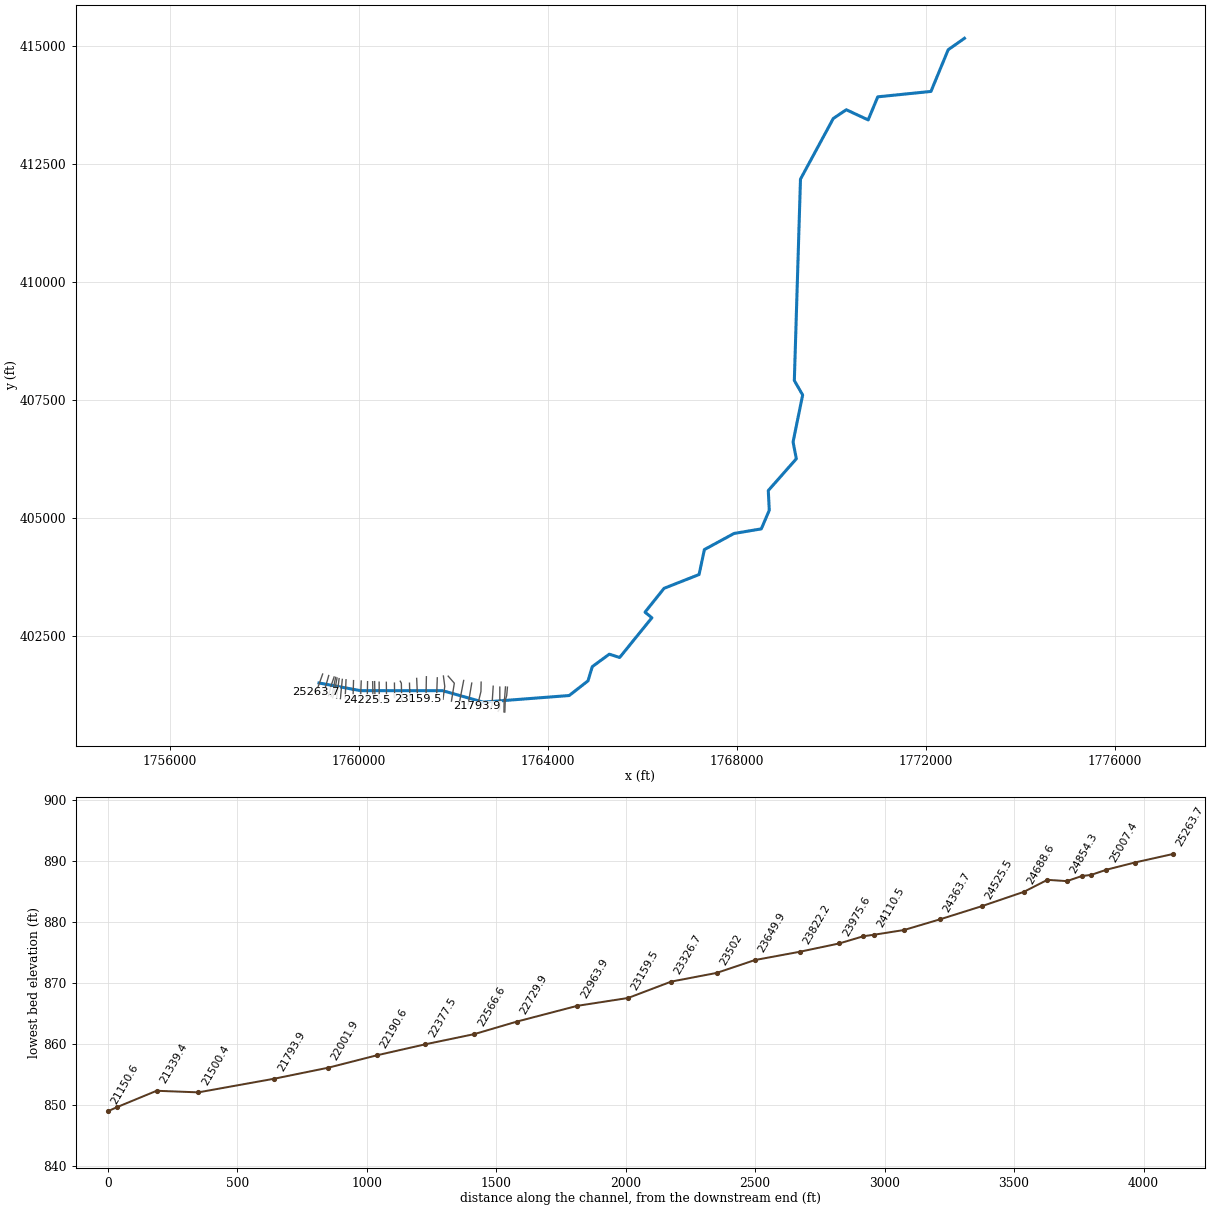
--- DRAWDYCK.prj (project) ---

Proj Title=DRAWDYCK
Current Plan=p01
Default Exp/Contr=0,0
English Units
Geom File=g01
Flow File=f01
Plan File=p01
BEGIN DESCRIPTION:
END DESCRIPTION:
DSS Export Rating Curves= 0
DSS Export Rating Curve Sorted= 0
DSS Export Volume Flow Curves= 0
DXF Filename=.\backup\DRAWDYCK.
DXF OffsetX= 0
DXF OffsetY= 0
DXF ScaleX= 0
DXF ScaleY= 0

--- DRAWDYCK.p01 (plan) ---

Plan Title=Floodplain
Program Version=4.00
Geom File=g01
Flow File=f01
K Sum by GR=0
Std Step Tol=0.01
Critical Tol=0.01
Num of Std Step Trials=20
Max Error Tol=0.3
Flow Tol Ratio=0.001
Split Flow NTrial=30
Split Flow Tol=0.02
Split Flow Ratio=0.02
Log Output Level=0
Friction Slope Method=1
Unsteady Friction Slope Method=2
Unsteady Bridges Friction Slope Method=1
Global Log Level=0
CheckData=False
Run HTab=0
Run UNet=0
Run PostProcess=0
UNET Theta=0
UNET Theta Warmup=0
UNET ZTol=0
UNET ZSATol=0
UNET MxIter=0
UNET MaxInSteps=0
UNET DtIC=0
UNET DtMin=0
UNET MaxCRTS=0
UNET WFStab=0
UNET SFStab=0
UNET WFX=0
UNET SFX=0
UNET DSS MLevel=0
UNET DZMax Abort=0
UNET Convert EG Bridges=0
UNET Use Existing IB Tables=0
UNET Froude Limit=0
UNET Froude Power=0
Write IC File=0
Echo Input=False
Echo Output=False
Write Detailed=0

--- DRAWDYCK.f01 (steady flow) ---

Flow Title=NFF Regression Equation
Program Version=4.10
Number of Profiles= 1
Profile Names=P100yr
River Rch & RM=DRAWDYCK,Main            ,25263.7
  808.64
River Rch & RM=DRAWDYCK,Main            ,25116.9
   898.9
River Rch & RM=DRAWDYCK,Main            ,24225.5
  983.23
River Rch & RM=DRAWDYCK,Main            ,22377.5
 1018.83
River Rch & RM=DRAWDYCK,Main            ,22190.6
  1156.7
River Rch & RM=DRAWDYCK,Main            ,21793.9
 1168.68
River Rch & RM=DRAWDYCK,Main            ,19421.1
 1294.52
River Rch & RM=DRAWDYCK,Main            ,19045.7
 1454.48
River Rch & RM=DRAWDYCK,Main            ,15611.7
 1585.68
River Rch & RM=DRAWDYCK,Main            ,9417.2
 1760.96
River Rch & RM=DRAWDYCK,Main            ,8546.5
 1954.73
River Rch & RM=DRAWDYCK,Main            ,579.1
 2130.11
River Rch & RM=DRAWDYCK,Main            ,248.7
 2132.93
Boundary for River Rch & Prof#=DRAWDYCK,Main            , 1
Up Type= 0
Dn Type= 3
Dn Slope=0.022228
DSS Import GetInterval= 0
DSS Import GetPeak= 0
DSS Import FillOption= 0

--- DRAWDYCK.g01 (geometry) ---

Geom Title=USGS 10m DEM
Program Version=4.10

River Reach=DRAWDYCK        ,Main
Reach XY= 30
     1759151.318      401510.761     1760031.858      401348.219
     1761769.219      401347.525     1762624.775      401104.816
     1764446.581      401244.955     1764844.775      401555.719
     1764935.053      401856.414     1765295.191      402120.927
     1765514.636      402050.789     1766196.581      402892.455
     1766051.442      403011.205     1766454.914      403516.761
     1767195.738      403808.783     1767307.717      404337.342
     1767935.321      404678.922     1768512.578      404776.144
     1768680.981      405170.241     1768660.148      405588.296
     1769253.897      406261.908     1769184.453      406618.071
     1769387.578      407612.863     1769211.363      407920.154
     1769341.571      412187.255     1770036.016      413472.498
     1770311.189      413657.394     1770773.863      413442.116
     1770976.988      413931.005     1772102.856      414045.588
     1772467.439      414929.008     1772812.075      415171.934

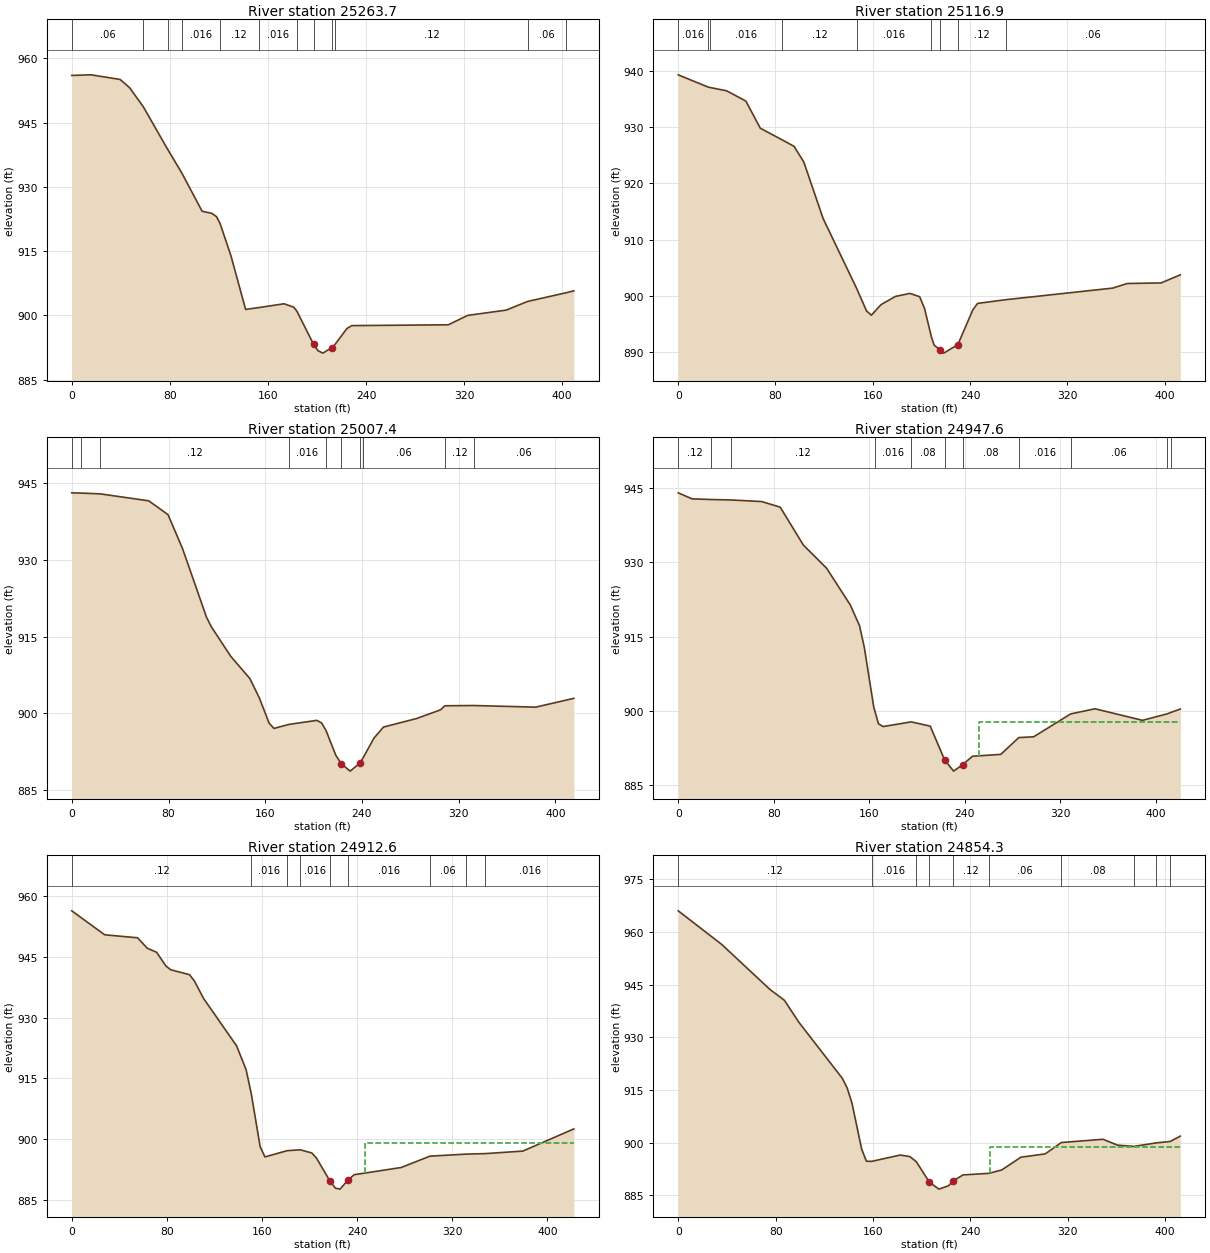
Type RM Length L Ch R = 1 ,25263.7 ,145.4,146.9,148.4
XS GIS Cut Line= 3
      1759229.45      401700.281     1759160.738      401507.405
     1759092.025      401314.529
#Sta/Elev= 30
       0  955.99    15.8  956.13    39.4  955.05    47.2  953.12   58.29948.7002
   78.16938.7744   89.65933.2822   106.3   924.3   114.2  923.81   118.1  923.02
     121921.4105   129.9  913.84   141.8  901.39  152.35901.8081   173.2  902.71
   181.1   901.9  183.71900.9343   197.2  893.25   200.8  891.76   204.8  891.19
   212.2  892.49  215.06893.3426   224.4  896.93   228.4  897.61   307.1   897.8
   322.9  899.99   354.4  901.23  371.83903.2546  403.18905.2725   409.5  905.72
#Mann= 12 ,-1 , 0
       0     .06       0   58.29     .12       0   78.16     .06       0
   89.65    .016       0     121     .12       0  152.35    .016       0
  183.71     .08       0   197.2    .045       0   212.2     .08       0
  215.06     .12       0  371.83     .06       0  403.18     .12       0
Bank Sta=197.2,212.2
XS Rating Curve= 0 ,0
Exp/Cntr=0.3,0.1

Type RM Length L Ch R = 1 ,25116.9 ,108.9,109.5,109.3
XS GIS Cut Line= 2
     1759357.874      401668.635     1759245.894      401271.066
#Sta/Elev= 30
       0  939.28   24.17937.1378   25.72937.0447    39.7  936.45    55.6  934.62
    67.5  929.79   85.54927.7109    95.3  926.56   103.3  923.78   119.2  913.72
  146.91901.2361   154.9   897.3   158.9  896.54   166.8  898.42   178.7  899.88
   190.6  900.42   198.6  899.83   202.6  897.75  208.28892.6508   210.5  891.23
     215  890.42   218.4   889.8     230  891.31   242.3  897.47   246.2  898.64
  269.65899.3043   357.4  901.36   369.4  902.18   397.2  902.28     413  903.72
#Mann= 9 ,-1 , 0
       0    .016       0   24.17     .06       0   25.72    .016       0
   85.54     .12       0  146.91    .016       0  208.28     .12       0
     215    .045       0     230     .12       0  269.65     .06       0
Bank Sta=215,230
XS Rating Curve= 0 ,0
Exp/Cntr=0.3,0.1

Type RM Length L Ch R = 1 ,25007.4 ,58,59.8,61.6
XS GIS Cut Line= 3
     1759471.589      401638.253     1759415.165      401472.455
     1759352.665      401240.684
#Sta/Elev= 30
       0  943.17     7.9943.1205   23.69942.9632    63.7   941.6    79.6  938.89
    91.6  932.24   111.4  918.81   115.4  916.92   131.4  911.15   147.3  906.76
   155.2  902.92   163.2  898.03   167.2  896.99  179.59897.7814   202.7  898.57
   206.6  898.06  210.18896.6281   218.4   891.7     223  890.04   230.2  888.62
     238  890.13  240.77891.1618   249.9  895.08   257.8  897.26   285.3  898.94
     305  900.64  308.54901.4297  332.55901.4792   383.7  901.16   415.2  902.89
#Mann= 10 ,-1 , 0
       0     .12       0     7.9     .08       0   23.69     .12       0
  179.59    .016       0  210.18     .12       0     223    .045       0
     238     .12       0  240.77     .06       0  308.54     .12       0
  332.55     .06       0
Bank Sta=223,238
XS Rating Curve= 0 ,0
Exp/Cntr=0.3,0.1

Type RM Length L Ch R = 1 ,24947.6 ,35,35,35
XS GIS Cut Line= 4
     1759504.575      401629.573     1759478.634      401512.091
     1759442.075      401314.469     1759407.353      401221.587
#Sta/Elev= 30
       0  944.09    11.6  942.87   27.82942.7333   44.32942.6442    69.9  942.32
    85.4  941.19   104.8  933.51   124.2  928.84     144  921.43   151.8  917.21
   155.8  912.81   163.7  900.75     165899.6233   167.6  897.37   171.5  896.78
  195.03  897.73     211  896.87   223.1     890   230.6  887.76   238.1  889.06
   246.4  890.77   270.1  891.15  285.14894.5479   297.6  894.71  328.63 899.343
     349  900.38   388.7  898.04  409.47899.3548  412.99899.6831   420.4  900.32
#Mann= 11 ,-1 , 0
       0     .12       0   27.82     .08       0   44.32     .12       0
     165    .016       0  195.03     .08       0   223.1    .045       0
   238.1     .08       0  285.14    .016       0  328.63     .06       0
  409.47    .016       0  412.99     .12       0
#XS Ineff= 2 , 0
                           251.6          897.77
Permanent Ineff=
       F       F
Bank Sta=223.1,238.1
XS Rating Curve= 0 ,0
Exp/Cntr=0.3,0.1

Type RM Length L Ch R = 1 ,24912.6 ,57,58.3,59.5
XS GIS Cut Line= 4
     1759534.089      401616.552     1759504.676      401460.876
      1759471.69      401282.056     1759442.176      401205.667
#Sta/Elev= 30
       0  956.45    27.7  950.52    55.4  949.78    63.4  947.21    71.3   946.2
    79.2  942.79    83.2  941.87      99  940.65     103  939.15   110.9  934.74
   138.6  923.04   146.6  917.15  151.03911.0694   158.4  898.13   162.4  895.56
  181.07897.0978  192.06897.3237   201.9  896.54   205.9  895.22   217.3  889.49
   221.7  887.83   225.6  887.59   232.3  889.87   237.5  891.16     277  892.94
   301.2895.7475  331.24896.2464  347.63896.3764   379.3     897   422.2  902.49
#Mann= 9 ,-1 , 0
       0     .12       0  151.03    .016       0  181.07     .08       0
  192.06    .016       0   217.3    .045       0   232.3    .016       0
   301.2     .06       0  331.24     .08       0  347.63    .016       0
#XS Ineff= 2 , 0
                          246.47          899.08
Permanent Ineff=
       F       F
Bank Sta=217.3,232.3
XS Rating Curve= 0 ,0
Exp/Cntr=0.3,0.1

Type RM Length L Ch R = 1 ,24854.3 ,74.4,75,75.6
XS GIS Cut Line= 2
      1759577.72      401603.084     1759525.637      401194.013
#Sta/Elev= 30
       0  966.02    35.7  956.45    75.3  943.64    87.2  940.54    99.1  934.27
   134.8  918.31   138.8  915.52   142.7  911.25   150.7   898.1   154.6   894.7
  158.93894.6613   182.4  896.46   190.3  896.01  195.57894.5494   206.2  888.78
   214.1  886.75     222   887.7   225.8   889.1   233.9  890.79  255.12891.2476
   265.7  892.21   281.5  895.85   301.4  896.78  314.67900.0213   348.9  900.95
   360.8  899.28  374.22898.9156  392.81899.9265  403.99900.3101   412.4  901.85
#Mann= 10 ,-1 , 0
       0     .12       0  158.93    .016       0  195.57     .12       0
   206.2    .045       0   225.8     .12       0  255.12     .06       0
  314.67     .08       0  374.22     .06       0  392.81     .08       0
  403.99     .12       0
#XS Ineff= 2 , 0
                           256.1          898.62
Permanent Ineff=
       F       F
Bank Sta=206.2,225.8
XS Rating Curve= 0 ,0
Exp/Cntr=0.3,0.1

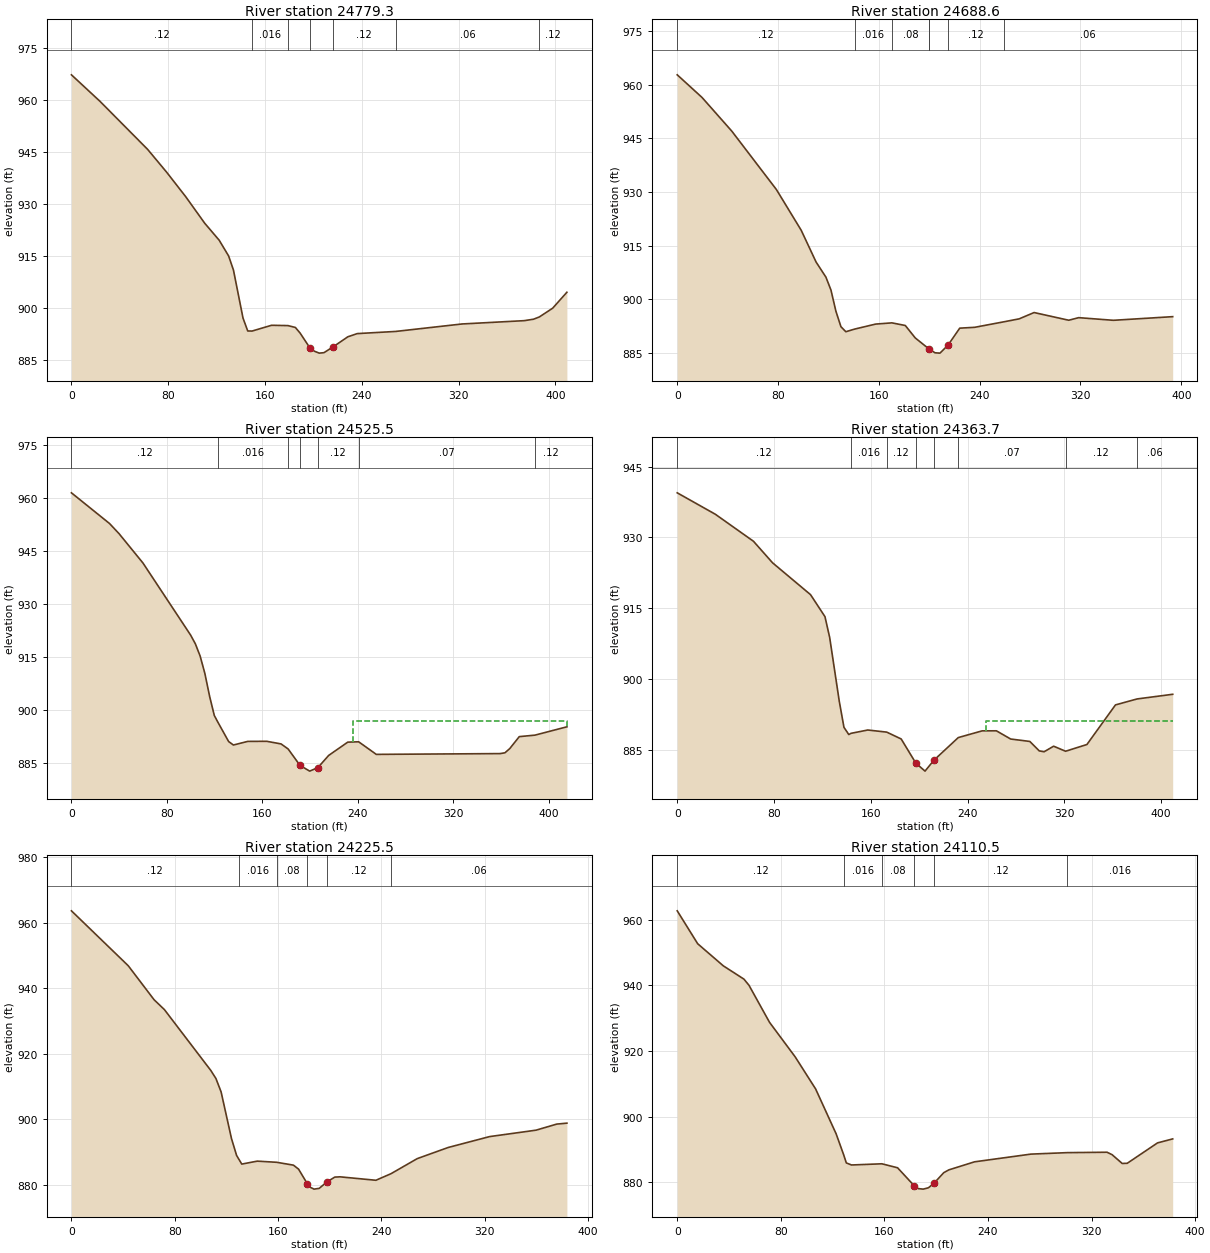
Type RM Length L Ch R = 1 ,24779.3 ,89.8,90.6,91.5
XS GIS Cut Line= 3
     1759645.495      401587.127     1759625.122      401383.393
     1759604.749      401179.659
#Sta/Elev= 30
       0  967.22    23.6  959.58      63  945.71    78.8  939.09    94.5  932.05
   110.2   924.4   122.1  919.53   129.9  914.99   133.9  910.93   141.8  897.08
   145.7  893.35  149.25893.3227   165.4  894.99  178.94894.8987   185.1  894.36
     189  892.74   196.9  888.56   200.8  887.51   204.8  886.96   208.7  887.09
     216   888.7   228.4  891.66   236.2  892.59  267.98893.2147   322.9  895.37
   374.1  896.32   381.9  896.74  386.72897.3951   397.7  899.91   409.5  904.52
#Mann= 7 ,-1 , 0
       0     .12       0  149.25    .016       0  178.94     .12       0
   196.9    .045       0     216     .12       0  267.98     .06       0
  386.72     .12       0
Bank Sta=196.9,216
XS Rating Curve= 0 ,0
Exp/Cntr=0.3,0.1

Type RM Length L Ch R = 1 ,24688.6 ,162.2,163.1,163.7
XS GIS Cut Line= 3
     1759724.193      401579.226     1759716.481      401398.376
      1759703.46       401186.57
#Sta/Elev= 30
       0  962.76    19.7  956.43    43.3  947.03    78.7  930.71    98.4  919.32
   110.2  910.45     118  906.23     122  902.63   125.9  896.74   129.9  892.39
   133.8  890.98  140.74891.7116   157.4  893.11   170.3 893.457     181  892.72
   188.9  889.24  199.88886.1461   199.9  886.14   204.6  885.09   208.5     885
   214.9  887.23   224.2  891.98     236  892.21  259.07893.7393   271.4  894.58
   283.2  896.34   310.7  894.19   318.6  894.91   346.1  894.17   393.2  895.19
#Mann= 7 ,-1 , 0
       0     .12       0  140.74    .016       0   170.3     .08       0
  199.88     .12       0   199.9    .045       0   214.9     .12       0
  259.07     .06       0
Bank Sta=199.9,214.9
XS Rating Curve= 0 ,0
Exp/Cntr=0.3,0.1

Type RM Length L Ch R = 1 ,24525.5 ,161.9,161.8,161.6
XS GIS Cut Line= 2
     1759883.047      401560.997     1759870.894      401146.066
#Sta/Elev= 30
       0  961.39    31.9  952.71    39.9  949.83    59.9  941.54    99.8  921.16
   103.8  918.68   107.8  915.23   111.8  910.26   115.8  903.75   119.7  898.38
  122.44896.6401   131.7  891.01   135.7  890.03   147.7  891.05   163.6  891.08
   175.6  890.34  181.54888.9098   191.5  884.26   199.6  882.64   206.5  883.64
   215.5  887.08   231.5  890.84  240.63890.9411   255.4  887.38   359.2   887.6
   363.2  887.83   367.2  889.01   375.2   892.4  388.37892.8263   415.1  895.18
#Mann= 7 ,-1 , 0
       0     .12       0  122.44    .016       0  181.54     .12       0
   191.5    .045       0   206.5     .12       0  240.63     .07       0
  388.37     .12       0
#XS Ineff= 2 , 0
                           236.2          896.84
Permanent Ineff=
       F       F
Bank Sta=191.5,206.5
XS Rating Curve= 0 ,0
Exp/Cntr=0.3,0.1

Type RM Length L Ch R = 1 ,24363.7 ,137.7,138.2,138.6
XS GIS Cut Line= 3
     1760045.718      401552.602     1760038.323      401347.985
     1760030.928      401143.369
#Sta/Elev= 30
       0  939.44    31.5   934.9      63  929.18    78.8  924.61   110.2  917.86
   122.1  913.21     126  908.79   133.9  895.32   137.8  889.76   141.8  888.23
  143.62888.4866   157.5  889.19  173.18888.7415   185.1  887.29   197.2  882.18
   204.8  880.48   212.2  882.81  232.29887.5876     252  889.01   263.8  889.02
   275.6  887.28   291.4  886.77   299.2  884.77   303.2  884.58   311.1  885.76
  320.95884.6941   338.6  886.12   362.2  894.51  380.06895.7703   409.5  896.76
#Mann= 8 ,-1 , 0
       0     .12       0  143.62    .016       0  173.18     .12       0
   197.2    .045       0   212.2     .12       0  232.29     .07       0
  320.95     .12       0  380.06     .06       0
#XS Ineff= 2 , 0
                          254.81          891.02
Permanent Ineff=
       F       F
Bank Sta=197.2,212.2
XS Rating Curve= 0 ,0
Exp/Cntr=0.3,0.1

Type RM Length L Ch R = 1 ,24225.5 ,114.1,115,115.9
XS GIS Cut Line= 2
     1760179.922      401538.427     1760172.978      401154.747
#Sta/Elev= 30
       0  963.57      44  946.83      64  936.47      72  933.46   107.9  914.93
   111.9  912.46   115.9  908.38   123.9  894.22   127.9  889.01  129.38888.0332
   131.9  886.37   143.9  887.27  158.92886.9216   171.9  886.05   175.9  884.83
   182.7  880.36   183.9   879.5   187.9  878.74   191.9  878.98   197.7  880.88
   203.9   882.4   207.9  882.49   235.8  881.44  247.54883.4563   267.8  888.04
   291.8  891.44   323.8  894.75   359.8  896.71   375.8  898.56   383.7  898.85
#Mann= 6 ,-1 , 0
       0     .12       0  129.38    .016       0  158.92     .08       0
   182.7    .045       0   197.7     .12       0  247.54     .06       0
Bank Sta=182.7,197.7
XS Rating Curve= 0 ,0
Exp/Cntr=0.3,0.1

Type RM Length L Ch R = 1 ,24110.5 ,42.1,42.1,42.1
XS GIS Cut Line= 3
     1760287.561      401537.559     1760293.637      401240.684
     1760339.745      401168.341
#Sta/Elev= 30
       0   962.7    15.8  952.68    35.6  945.95    51.5  941.91    55.4  940.05
    71.3  928.75    91.1  918.24   106.9  908.47   122.7  894.84  128.52888.4673
   130.6  885.95   134.6  885.32  158.06885.6817   170.2  884.47   183.2  878.93
   186.1  878.13     190  877.97     194  878.38   198.2  879.71   205.9  882.99
   209.8  883.83   229.6  886.28   273.2  888.63   301.4889.0807     332   889.2
   335.9  888.45   343.7  885.78   347.6  885.84     371  892.05   382.7  893.26
#Mann= 6 ,-1 , 0
       0     .12       0  128.52    .016       0  158.06     .08       0
   183.2    .045       0   198.2     .12       0   301.4    .016       0
Bank Sta=183.2,198.2
XS Rating Curve= 0 ,0
Exp/Cntr=0.3,0.1

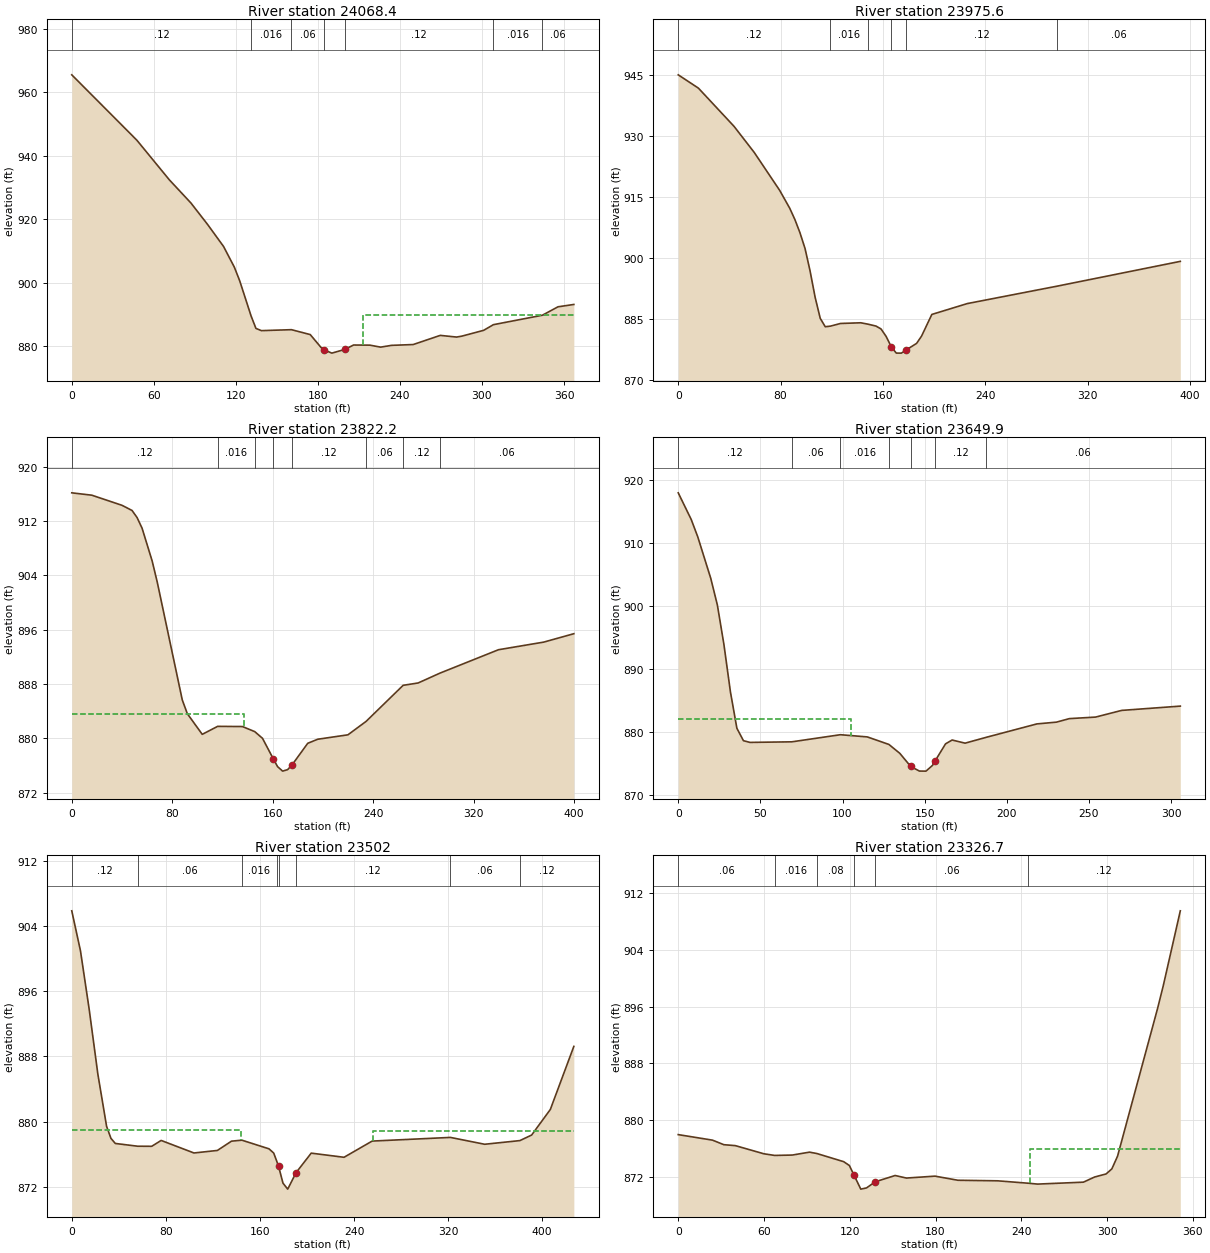
Type RM Length L Ch R = 1 ,24068.4 ,93.1,92.8,92.5
XS GIS Cut Line= 3
     1760329.228      401540.163     1760336.172      401231.135
     1760367.523       401182.23
#Sta/Elev= 30
       0  965.56    47.6  944.93    71.3  932.45    87.2  925.08    99.1  918.47
     111   911.4   118.9  904.86   122.8  900.58  131.13889.4745   134.7  885.52
   138.7  884.82  160.67885.1181   174.4  883.58   182.3  879.51   184.6  878.75
   190.2  877.72   199.6  878.88   206.1  880.28     218  880.24   225.9  879.61
   233.8  880.17   249.7  880.43   269.5  883.32   281.4  882.79   285.3  883.08
   301.2  884.91  308.39886.7017  344.19889.6805   355.6  892.34   367.2  893.08
#Mann= 7 ,-1 , 0
       0     .12       0  131.13    .016       0  160.67     .06       0
   184.6    .045       0   199.6     .12       0  308.39    .016       0
  344.19     .06       0
#XS Ineff= 2 , 0
                          213.09          889.69
Permanent Ineff=
       F       F
Bank Sta=184.6,199.6
XS Rating Curve= 0 ,0
Exp/Cntr=0.3,0.1

Type RM Length L Ch R = 1 ,23975.6 ,153.3,153.4,153.4
XS GIS Cut Line= 2
     1760424.714       401528.01     1760428.186      401135.649
#Sta/Elev= 30
       0  944.96    15.8  941.68    43.6   932.3    59.4  925.88    79.3  916.55
    87.2  912.13    91.2  909.36    95.1  906.17    99.1  902.27     103  896.81
     107  890.26     111  885.08   114.9  883.03  118.95883.1762   126.8  883.83
   142.7     884  148.49 883.644   154.6  883.19   158.5  882.48   162.5  880.64
   166.5   878.1   170.4  876.55   174.4  876.54  178.02877.2911   186.3  878.94
   190.2  880.74   198.2  886.05   225.9  888.72  296.17893.0076   392.4   899.1
#Mann= 6 ,-1 , 0
       0     .12       0  118.95    .016       0  148.49     .06       0
   166.5    .045       0  178.02     .12       0  296.17     .06       0
Bank Sta=166.5,178.02
XS Rating Curve= 0 ,0
Exp/Cntr=0.3,0.1

Type RM Length L Ch R = 1 ,23822.2 ,172.1,172.3,172.2
XS GIS Cut Line= 2
     1760576.922       401525.24     1760582.113       401125.51
#Sta/Elev= 30
       0  916.18      16  915.83      40  914.34      48  913.58      52  912.54
      56  910.96      64  906.15      68  903.08      88  885.66      92  883.64
   103.9  880.59  116.19 881.768   135.9  881.74  145.72880.9908   151.9     880
   160.5  876.97   163.9  875.83   167.9  875.17   171.9  875.39   175.5  876.11
   187.9  879.27   195.9  879.87   219.9  880.52  234.34882.4936  263.88887.8154
   275.8  888.16  293.41889.6289   339.8  893.06   375.8  894.18   399.8  895.42
#Mann= 8 ,-1 , 0
       0     .12       0  116.19    .016       0  145.72     .12       0
   160.5    .045       0   175.5     .12       0  234.34     .06       0
  263.88     .12       0  293.41     .06       0
#XS Ineff= 2 , 0
           137.1  883.65
Permanent Ineff=
       F       F
Bank Sta=160.5,175.5
XS Rating Curve= 0 ,0
Exp/Cntr=0.3,0.1

Type RM Length L Ch R = 1 ,23649.9 ,147.5,147.9,147.9
XS GIS Cut Line= 2
     1760748.599      401507.751      1760752.94      401202.195
#Sta/Elev= 30
       0  917.91     7.9  913.69    11.9  910.93    19.8  904.36    23.8  900.16
    27.8   893.9    31.8  886.33    35.7  880.61    39.7  878.64    43.7  878.37
   69.16878.4626    98.7879.5887   115.1  879.24  128.24878.0471   134.9  876.63
   141.5  874.56   146.8  873.83   150.8  873.82   154.8  874.74   156.5   875.5
   162.7  878.14   166.7  878.75   174.6  878.25  187.31879.1648   218.3   881.3
   230.2  881.58   238.1  882.14     254  882.38   269.9  883.44   305.6  884.12
#Mann= 7 ,-1 , 0
       0     .12       0   69.16     .06       0    98.7    .016       0
  128.24     .12       0   141.5    .045       0   156.5     .12       0
  187.31     .06       0
#XS Ineff= 2 , 0
          105.13  882.12
Permanent Ineff=
       F       F
Bank Sta=141.5,156.5
XS Rating Curve= 0 ,0
Exp/Cntr=0.3,0.1

Type RM Length L Ch R = 1 ,23502   ,174.9,175.3,175
XS GIS Cut Line= 3
     1760871.991      401547.963     1760894.777      401505.645
     1760903.717      401126.938
#Sta/Elev= 30
       0  905.89     7.4  900.98    14.8  893.81    22.2  885.82    29.6  879.43
    33.3  877.95      37  877.32   56.04 876.979      68  876.97      76  877.69
   103.9  876.15   123.8  876.46   135.8   877.6  144.67877.7222   167.7  876.66
   171.7  876.14  174.22875.1635   175.8  874.53   179.6  872.44   183.6  871.71
   190.8  873.75   203.6  876.13   231.5  875.62   255.4  877.61  321.94878.0615
   351.1  877.22  381.03 877.671     391  878.35   406.9  881.49   426.9  889.24
#Mann= 8 ,-1 , 0
       0     .12       0   56.04     .06       0  144.67    .016       0
  174.22     .12       0   175.8    .045       0   190.8     .12       0
  321.94     .06       0  381.03     .12       0
#XS Ineff= 2 , 0
          143.77  878.93   256.1          878.88
Permanent Ineff=
       F       F
Bank Sta=175.8,190.8
XS Rating Curve= 0 ,0
Exp/Cntr=0.3,0.1

Type RM Length L Ch R = 1 ,23326.7 ,166,167.1,167.2
XS GIS Cut Line= 2
     1761067.176      401506.015     1761076.549      401154.939
#Sta/Elev= 30
       0  877.97      24  877.19    31.9  876.55    39.9  876.42    59.9  875.27
   67.45875.0375    79.8  875.09    91.8   875.5   96.99875.3046   115.7  874.16
   119.7  873.62   122.8  872.33   127.7  870.29   131.7  870.46   137.8  871.32
   151.7  872.21   159.6  871.85   179.6  872.12   195.6  871.54   223.5  871.46
  244.72871.1236   251.4     871   283.4  871.27   291.3     872   299.3  872.43
   303.3  873.14   307.3  874.93   335.2  895.67   339.2  898.88   351.2   909.5
#Mann= 6 ,-1 , 0
       0     .06       0   67.45    .016       0   96.99     .08       0
   122.8    .045       0   137.8     .06       0  244.72     .12       0
#XS Ineff= 2 , 0
                          245.96          875.92
Permanent Ineff=
       F       F
Bank Sta=122.8,137.8
XS Rating Curve= 0 ,0
Exp/Cntr=0.3,0.1

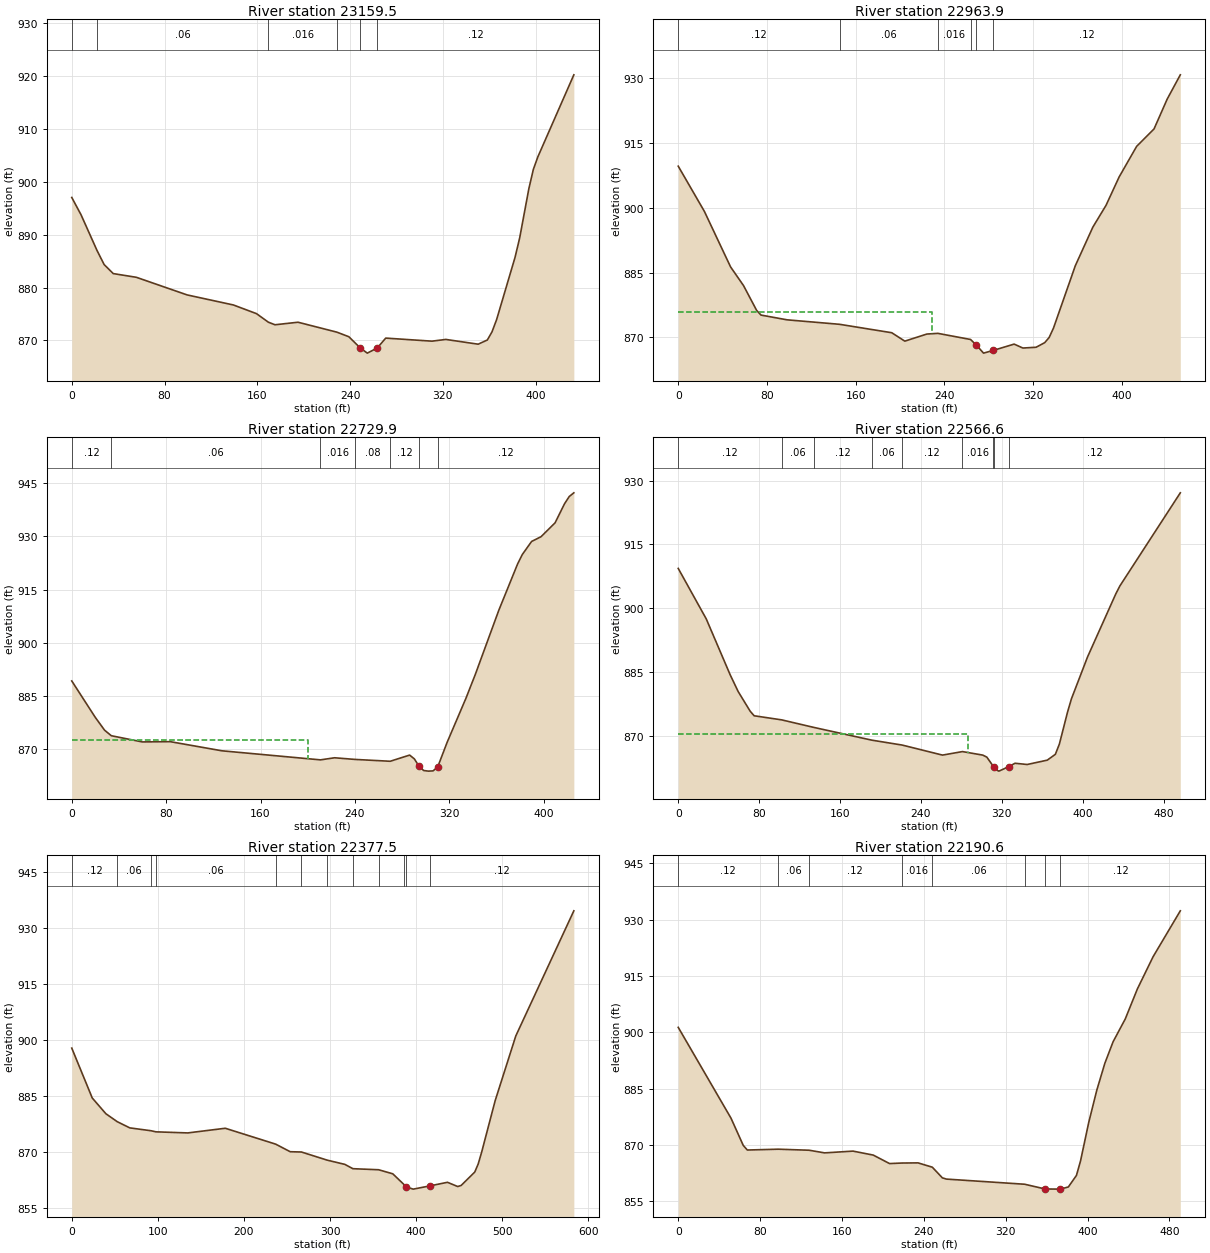
Type RM Length L Ch R = 1 ,23159.5 ,197.8,195.6,194
XS GIS Cut Line= 3
     1761218.985      401607.872     1761237.214      401218.115
     1761251.519      401177.882
#Sta/Elev= 30
       0  897.02       8  893.75   21.63887.0726    27.9  884.34    35.8  882.63
    55.7  881.93    99.5   878.6   139.4   876.7   159.3  875.06  169.47873.4522
   175.2  872.96   195.1  873.44   228.6871.5625   238.9   870.7   248.4  868.65
   254.8   867.6   263.4  868.57   270.7  870.44   310.6  869.86   322.5  870.19
   350.4  869.29   358.3  870.08   362.3   871.6   366.3  873.93   382.2   885.7
   386.2  889.38   394.1  898.67     398  902.34   401.8  904.66   432.9   920.2
#Mann= 6 ,-1 , 0
       0     .12       0   21.63     .06       0  169.47    .016       0
   228.6     .12       0   248.4    .045       0   263.4     .12       0
Bank Sta=248.4,263.4
XS Rating Curve= 0 ,0
Exp/Cntr=0.3,0.1

Type RM Length L Ch R = 1 ,22963.9 ,234.6,234,233.3
XS GIS Cut Line= 4
     1761424.815      401643.167     1761421.242      401466.378
     1761418.738      401253.411     1761456.903      401203.193
#Sta/Elev= 30
       0  909.67    23.6  899.18    47.2  886.32    58.9  881.98    70.7  876.24
    74.7  875.14    98.2  874.04  145.54873.0024   192.6  871.05   204.4   869.1
   224.2  870.74  234.16870.9046  263.69869.4827     269  868.16   275.4  866.32
     284  866.94     303  868.41   310.9   867.5   322.8  867.68   330.6  868.75
   334.6  869.95   338.5  872.13   358.2  886.59     374  895.53   385.9  900.59
   397.7  907.16   413.5  914.26   429.2   918.3   441.1  925.24   452.9  930.85
#Mann= 6 ,-1 , 0
       0     .12       0  145.54     .06       0  234.16    .016       0
  263.69     .12       0     269    .045       0     284     .12       0
#XS Ineff= 2 , 0
           228.5  875.82
Permanent Ineff=
       F       F
Bank Sta=269,284
XS Rating Curve= 0 ,0
Exp/Cntr=0.3,0.1

Type RM Length L Ch R = 1 ,22729.9 ,165.2,163.3,160.8
XS GIS Cut Line= 2
     1761655.717       401619.73     1761640.092      401194.383
#Sta/Elev= 30
       0   889.2    19.9  878.93    27.8   875.3   33.49873.7338    59.7  871.98
    83.5  872.05   127.3  869.47  210.83866.9119   222.8   867.5  240.38867.0295
  269.93866.5143   286.4  868.26   290.4  867.19   294.4  865.08   298.3   863.9
   302.3  863.73   306.3   863.8   310.3  864.99   318.2  871.87   334.1  884.28
   342.1  891.06     362  909.17   377.9  922.22   381.9   924.9   389.8   928.6
   397.8  929.94   409.7  933.86   417.7  939.24   421.7  941.29   425.6  942.33
#Mann= 7 ,-1 , 0
       0     .12       0   33.49     .06       0  210.83    .016       0
  240.38     .08       0  269.93     .12       0   294.4    .045       0
   310.3     .12       0
#XS Ineff= 2 , 0
          200.26  872.63
Permanent Ineff=
       F       F
Bank Sta=294.4,310.3
XS Rating Curve= 0 ,0
Exp/Cntr=0.3,0.1

Type RM Length L Ch R = 1 ,22566.6 ,189.1,189.1,188.5
XS GIS Cut Line= 3
     1761784.957      401658.219     1761813.603      401438.601
     1761776.276      401166.031
#Sta/Elev= 30
       0  909.37    27.7   897.5    51.4  884.34    59.3   880.4    71.2  875.77
    75.1  874.71  102.35873.7458  134.56871.9476  191.71868.9641   221.5  867.82
   261.4  865.46  281.12 866.285   301.2  865.46   305.2  864.99  310.93863.0624
   311.9  862.66   313.2  862.12   317.2  861.69   326.9  862.75   333.1  863.54
   345.1  863.25     365  864.27     373  865.64     377  868.06     385  875.52
   388.9  878.69   404.9  888.58   432.8  903.38   436.8  905.24   496.6  927.15
#Mann= 9 ,-1 , 0
       0     .12       0  102.35     .06       0  134.56     .12       0
  191.71     .06       0   221.5     .12       0  281.12    .016       0
  310.93     .12       0   311.9    .045       0   326.9     .12       0
#XS Ineff= 2 , 0
          286.91  870.54
Permanent Ineff=
       F       F
Bank Sta=311.9,326.9
XS Rating Curve= 0 ,0
Exp/Cntr=0.3,0.1

Type RM Length L Ch R = 1 ,22377.5 ,188,186.9,186.1
XS GIS Cut Line= 3
     1761885.805      401655.593     1762016.013      401506.287
     1761955.249      401126.079
#Sta/Elev= 30
       0  897.83    23.8  884.45    39.6  880.24   52.79878.1061    67.4  876.44
      92875.6772   97.73875.3817   134.7  875.09   178.3  876.34  236.76 872.086
   253.7  870.05  266.67869.9758  296.58867.7951   317.2  866.65  326.49865.4997
   356.4 865.215   372.8  864.13  386.32861.1429   388.6  860.57   396.6  860.02
   416.4  860.91   436.3  861.85   448.2  860.72   452.2     861     468  864.59
     472  866.74     476  869.91   491.8   883.8   515.7   901.1   583.1  934.64
#Mann= 12 ,-1 , 0
       0     .12       0   52.79     .06       0      92    .016       0
   97.73     .06       0  236.76    .016       0  266.67     .06       0
  296.58     .12       0  326.49    .016       0   356.4     .08       0
  386.32     .12       0   388.6    .045       0   416.4     .12       0
Bank Sta=388.6,416.4
XS Rating Curve= 0 ,0
Exp/Cntr=0.3,0.1

Type RM Length L Ch R = 1 ,22190.6 ,187.9,188.7,188.9
XS GIS Cut Line= 3
     1762213.877      401564.174      1762127.94       401119.73
     1762120.503      401082.547
#Sta/Elev= 30
       0  901.29    51.6  877.09    63.5  869.88    67.5  868.63   97.84 868.851
  127.92868.5748     143  867.87   170.8  868.34   190.6  867.28   206.5  865.02
  218.17865.1625   234.3  865.21  248.25864.0638   258.1  861.22   262.1  860.89
   338.5859.5225   358.5  858.26   373.3  858.22   373.5  858.22   381.2   858.8
   389.1  861.86   393.1  865.72   401.1  875.95     409  884.56   416.9  891.75
   424.9  897.44   436.8  903.52   448.7  911.54     464  920.09   490.6  932.31
#Mann= 8 ,-1 , 0
       0     .12       0   97.84     .06       0  127.92     .12       0
  218.17    .016       0  248.25     .06       0   338.5     .12       0
   358.5    .045       0   373.5     .12       0
Bank Sta=358.5,373.5
XS Rating Curve= 0 ,0
Exp/Cntr=0.3,0.1

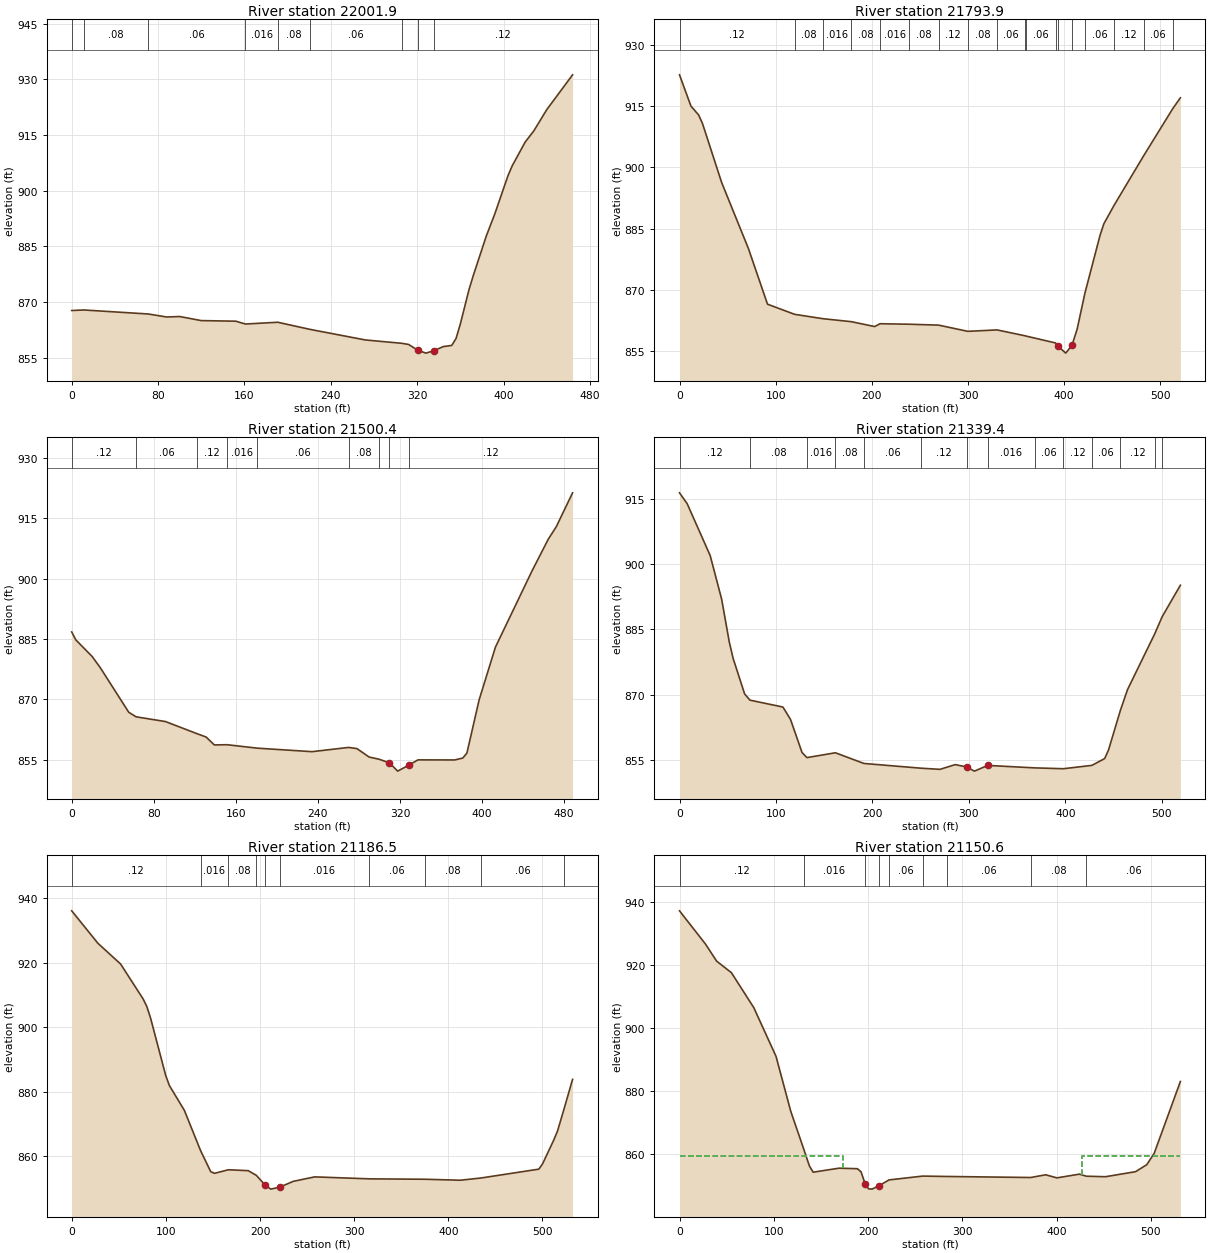
Type RM Length L Ch R = 1 ,22001.9 ,209.5,208.1,206.2
XS GIS Cut Line= 2
     1762384.884      401508.619     1762307.627      401051.154
#Sta/Elev= 30
       0  867.67   11.13867.8157   71.04 866.728      88  865.92     100  866.05
     120  864.95     152  864.79   160.9864.0248  190.85864.5057  220.81862.5775
     272  859.73  305.58858.8323     312  858.52   320.7  856.94     328  856.18
   335.7  856.85     344  857.93     352  858.26     356  860.14     360   864.1
     368  873.33     372  877.15     384  887.77     392  893.82     404  903.97
     408  906.69     420  913.09     428   916.1     440  921.84   463.9  931.22
#Mann= 9 ,-1 , 0
       0     .12       0   11.13     .08       0   71.04     .06       0
   160.9    .016       0  190.85     .08       0  220.81     .06       0
  305.58     .12       0   320.7    .045       0   335.7     .12       0
Bank Sta=320.7,335.7
XS Rating Curve= 0 ,0
Exp/Cntr=0.3,0.1

Type RM Length L Ch R = 1 ,21793.9 ,289.2,293.5,297.3
XS GIS Cut Line= 3
     1762583.362      401528.649     1762579.328      401329.799
     1762502.072      401017.299
#Sta/Elev= 30
       0  922.77    11.9  915.09    19.9   912.9    23.9  910.82    43.8  896.32
    71.6  880.12    91.5  866.41  119.64863.9186  149.18862.8404  178.72862.1056
   202.9  860.91  208.54861.6053  238.97861.4807  269.39861.2627  299.82 859.736
  330.24860.0842  359.64858.6251  360.67858.5511  391.09856.8792   393.1  856.19
   401.6  854.38   408.1   856.3   413.5  860.31  421.52869.0923   437.3  883.35
   441.3  886.19  451.94890.7334  482.72902.9153  512.79914.4258   520.8  917.12
#Mann= 18 ,-1 , 0
       0     .12       0  119.64     .08       0  149.18    .016       0
  178.72     .08       0  208.54    .016       0  238.97     .08       0
  269.39     .12       0  299.82     .08       0  330.24     .06       0
  359.64     .12       0  360.67     .06       0  391.09     .12       0
   393.1    .045       0   408.1     .12       0  421.52     .06       0
  451.94     .12       0  482.72     .06       0  512.79     .12       0
Bank Sta=393.1,408.1
XS Rating Curve= 0 ,0
Exp/Cntr=0.3,0.1

Type RM Length L Ch R = 1 ,21500.4 ,160.3,161,162.5
XS GIS Cut Line= 3
     1762838.776      401442.073     1762812.835      401033.792
     1762783.221      400960.302
#Sta/Elev= 30
       0  886.76       4  884.79    19.9  880.66    27.8  877.89    55.6  866.79
    62.7865.6508    91.4  864.47  121.89861.4786   131.1  860.61     139  858.66
  151.49858.7071  181.08857.8481   234.3  856.98  269.87858.0348     278  857.75
     290  855.64  299.46855.1132   309.8   854.2   317.8  852.14   329.1   853.7
   337.6  854.94   373.4  854.92   381.3   855.4   385.3  856.64   397.2  869.86
   413.1  882.98   448.7   901.9   464.6  909.82   472.5  912.97   488.3  921.36
#Mann= 9 ,-1 , 0
       0     .12       0    62.7     .06       0  121.89     .12       0
  151.49    .016       0  181.08     .06       0  269.87     .08       0
  299.46     .12       0   309.8    .045       0   329.1     .12       0
Bank Sta=309.8,329.1
XS Rating Curve= 0 ,0
Exp/Cntr=0.3,0.1

Type RM Length L Ch R = 1 ,21339.4 ,154.3,153,149.8
XS GIS Cut Line= 3
     1762978.533      401422.976     1762978.533      400966.378
     1762943.811      400914.295
#Sta/Elev= 30
       0  916.33     7.9  913.86    31.8  901.92    43.7  891.89    51.6  882.06
    55.6  878.28    67.5  870.14   73.02868.7092   107.2  867.12   115.1  864.27
     127  856.69  132.09855.5064  161.62856.6154  191.16854.1632  250.23853.0742
     270  852.81   285.9   853.9   297.8  853.34   305.7   852.4   319.5  853.71
  368.37853.1443  397.91852.9518  427.45853.7192   440.7  855.28   444.7  857.24
  457.06866.3839   464.4  871.12  492.56883.9109  500.38 887.902   519.2   895.1
#Mann= 14 ,-1 , 0
       0     .12       0   73.02     .08       0  132.09    .016       0
  161.62     .08       0  191.16     .06       0  250.23     .12       0
   297.8    .045       0   319.5    .016       0  368.37     .06       0
  397.91     .12       0  427.45     .06       0  457.06     .12       0
  492.56     .06       0  500.38     .12       0
Bank Sta=297.8,319.5
XS Rating Curve= 0 ,0
Exp/Cntr=0.3,0.1

Type RM Length L Ch R = 1 ,21186.5 ,40,35.8,32.8
XS GIS Cut Line= 4
     1763098.325      401427.316     1763080.096      401188.601
      1763069.78      401160.529     1763066.423      400897.857
#Sta/Elev= 30
       0  936.08    27.9  925.99    51.9  919.59    75.8  908.77    79.8  906.39
    83.8  902.76    99.8  885.04   103.7  881.89   119.7  874.14  136.83861.7101
   147.6  855.17   151.6  854.62  166.45855.7267   187.5  855.45  196.07854.0062
   205.8  850.87   211.5  849.72   220.8  850.32   235.4  852.14   258.1  853.52
  316.18  852.91  375.26852.7853   412.6  852.48  434.33853.1569   496.2  855.92
   500.2  857.61   512.1     865   516.1  867.83  522.95874.6054     532  883.78
#Mann= 10 ,-1 , 0
       0     .12       0  136.83    .016       0  166.45     .08       0
  196.07    .016       0   205.8    .045       0   220.8    .016       0
  316.18     .06       0  375.26     .08       0  434.33     .06       0
  522.95     .12       0
Bank Sta=205.8,220.8
XS Rating Curve= 0 ,0
Exp/Cntr=0.3,0.1

Type RM Length L Ch R = 1 ,21150.6 ,26.2,32.8,39.4
XS GIS Cut Line= 4
     1763139.992      401422.108     1763124.467      401245.598
     1763093.217      401137.959     1763084.736       400895.95
#Sta/Elev= 30
       0  937.09    27.6  926.56    39.4  921.17    55.1  917.51    78.8  906.46
   102.4  891.05   118.1   873.6  131.73861.7667   137.8  856.38   141.8  854.39
   169.3  855.66   188.8  855.49   192.6   854.5   196.9  850.77   200.4  849.16
   204.2  849.03   211.9  850.13   222.3851.9467  258.04853.1553  283.81 853.033
  372.68 852.707   388.5  853.57   400.4  852.59   424.2  853.77  431.79853.1161
     452  852.96   483.8  854.55   495.7  856.75   503.6  860.33   531.4  883.08
#Mann= 9 ,-1 , 0
       0     .12       0  131.73    .016       0   196.9    .045       0
   211.9    .016       0   222.3     .06       0  258.04    .016       0
  283.81     .06       0  372.68     .08       0  431.79     .06       0
#XS Ineff= 2 , 0
       0   173.2  859.52  427.47       0  859.52
Permanent Ineff=
       F       F
Bank Sta=196.9,211.9
XS Rating Curve= 0 ,0
Exp/Cntr=0.3,0.1