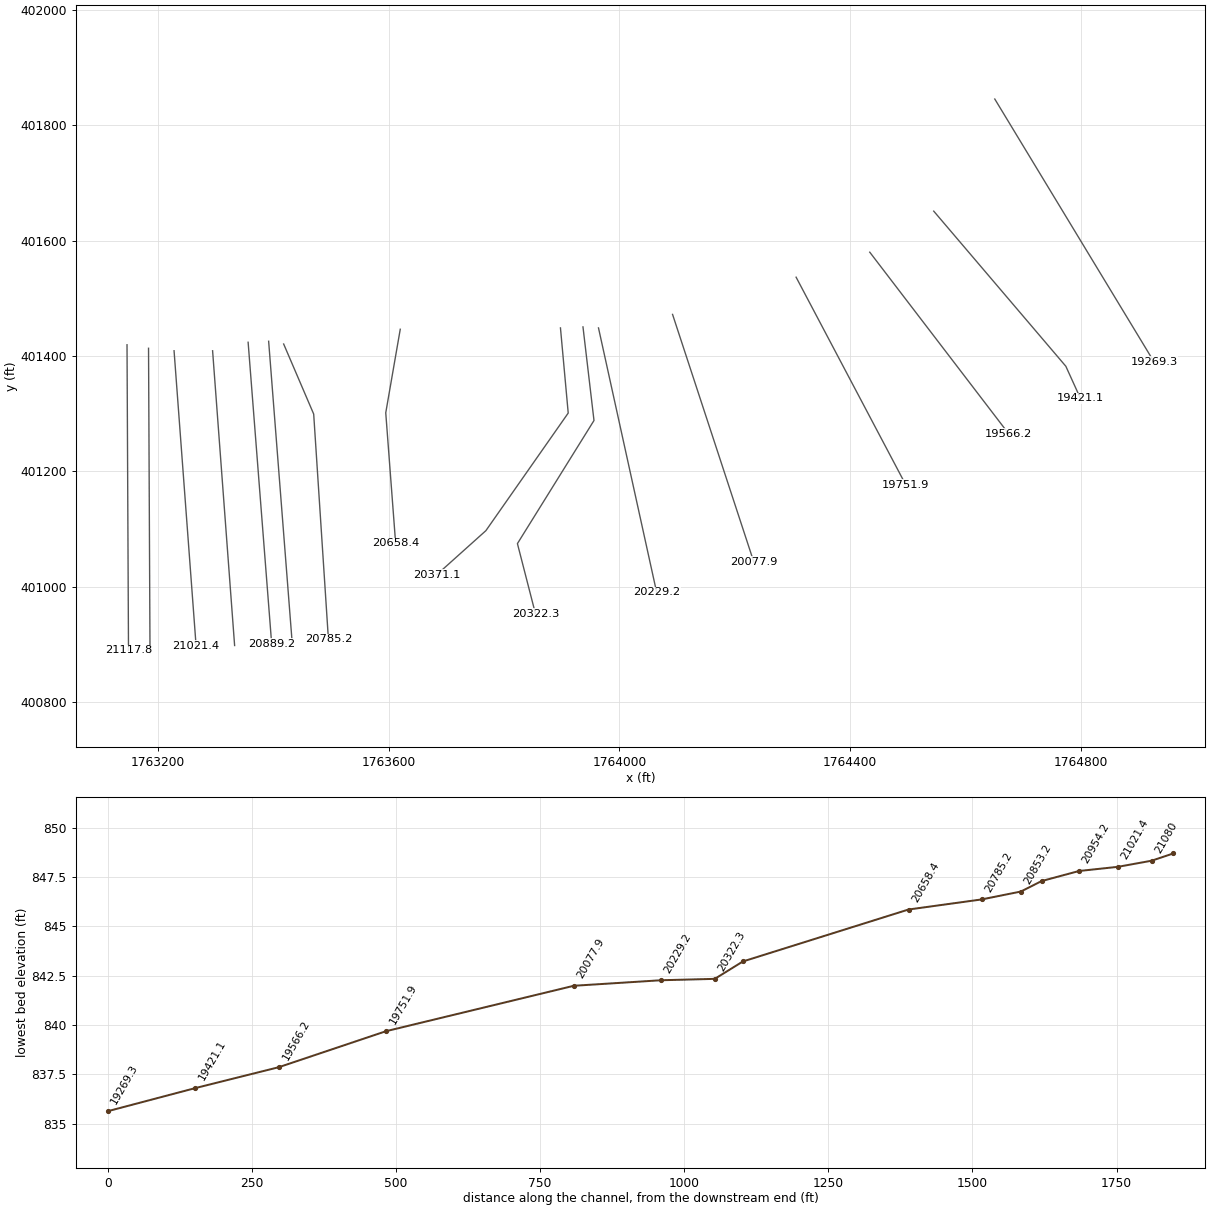
HEC-RAS study DRAWDYCK.prj: DRAWDYCK

--- DRAWDYCK.g01 (geometry) --- (continued)

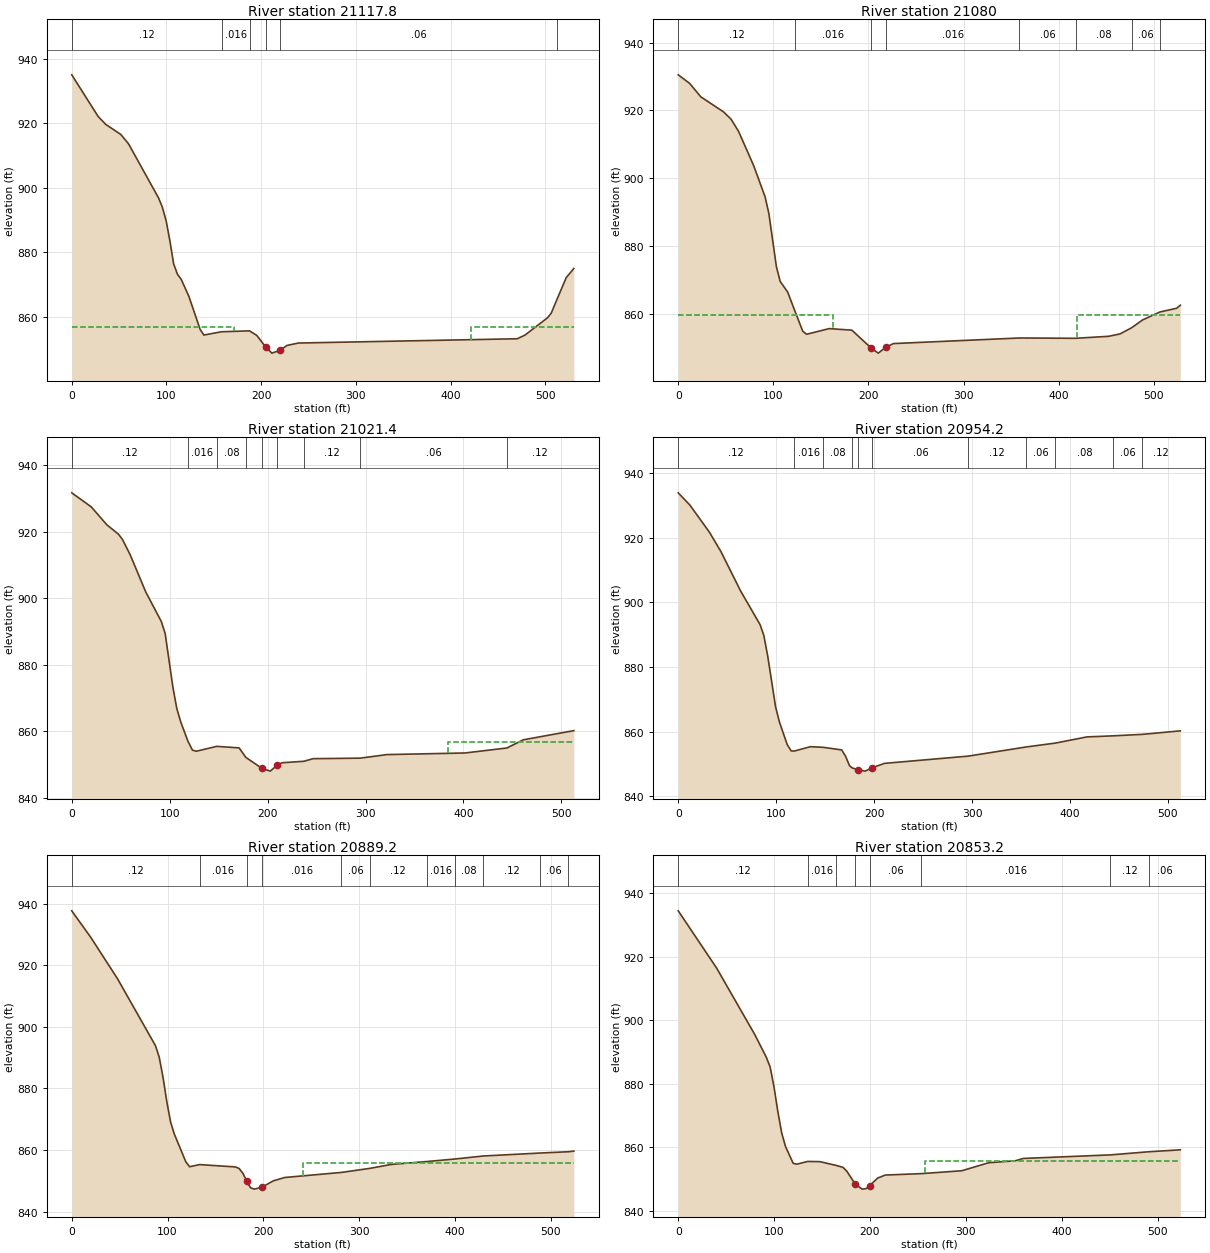
Type RM Length L Ch R = 1 ,21117.8 ,38,37.9,37.8
XS GIS Cut Line= 2
     1763146.068      401419.503     1763148.629      400889.294
#Sta/Elev= 30
       0  935.05    27.9   922.1    35.9  919.67    51.8  916.54    59.8  913.71
    91.7  896.82    95.7  893.94    99.7  889.71   103.6  883.58   107.6  876.36
   111.6  873.18   115.6  871.56   123.6  866.36   135.5   856.1   139.5   854.3
  158.16855.3196  187.69855.6025   195.3  854.21   204.9  850.54   211.3  848.69
   219.9  849.56   227.2  851.07   239.2  851.82   470.4  853.15   478.4  854.25
   502.3  859.63   506.3  861.08  512.59 865.492   522.2  872.14   530.2  874.96
#Mann= 6 ,-1 , 0
       0     .12       0  158.16    .016       0  187.69     .06       0
   204.9    .045       0   219.9     .06       0  512.59     .12       0
#XS Ineff= 2 , 0
       0   171.4  856.84  422.08       0  856.84
Permanent Ineff=
       F       F
Bank Sta=204.9,219.9
XS Rating Curve= 0 ,0
Exp/Cntr=0.3,0.1

Type RM Length L Ch R = 1 ,21080   ,57,58.6,60.2
XS GIS Cut Line= 2
     1763183.394      401413.427     1763185.945      400885.407
#Sta/Elev= 30
       0  930.48    11.9  927.98    23.8  923.97    47.6  919.55    55.6  917.38
    63.5  913.76    79.4  903.62    91.3   894.5    95.3  889.57   103.2  873.92
   107.2   869.5   115.1  866.35  122.54860.8484     131  854.76     135  853.89
   158.8  855.56   182.6   855.1   203.2  849.74   210.4  848.32   218.2  850.04
   226.3  851.14  358.83852.7879   417.9852.6979   452.6  853.29   464.5  853.98
  476.98855.8357   488.3  858.12  506.51860.4617   524.1  861.56     528  862.47
#Mann= 8 ,-1 , 0
       0     .12       0  122.54    .016       0   203.2    .045       0
   218.2    .016       0  358.83     .06       0   417.9     .08       0
  476.98     .06       0  506.51     .12       0
#XS Ineff= 2 , 0
       0     163  859.64  419.77       0  859.64
Permanent Ineff=
       F       F
Bank Sta=203.2,218.2
XS Rating Curve= 0 ,0
Exp/Cntr=0.3,0.1

Type RM Length L Ch R = 1 ,21021.4 ,67.7,67.2,66.8
XS GIS Cut Line= 2
     1763227.665      401409.087      1763265.86      400897.802
#Sta/Elev= 30
       0  931.62    19.9   927.4    35.8  922.02    47.7  919.19    51.7  917.65
    59.6  913.05    75.5  901.87    91.4  892.99    95.4  889.33   103.3  873.16
   107.3  866.77   111.3  862.78  118.53857.0602   123.2  854.32   127.2  853.99
  148.15855.4542   170.9  854.99  177.77 852.138   194.4   848.8   202.7  848.01
   209.4  849.72   214.6  850.52     237  850.97   246.4  851.75  294.51851.9082
   321.9  852.98   401.4  853.46  444.33854.9604     461  857.41   512.7  860.18
#Mann= 9 ,-1 , 0
       0     .12       0  118.53    .016       0  148.15     .08       0
  177.77     .06       0   194.4    .045       0   209.4     .06       0
     237     .12       0  294.51     .06       0  444.33     .12       0
#XS Ineff= 2 , 0
                          384.34          856.71
Permanent Ineff=
       F       F
Bank Sta=194.4,209.4
XS Rating Curve= 0 ,0
Exp/Cntr=0.3,0.1

Type RM Length L Ch R = 1 ,20954.2 ,64.4,65,65.6
XS GIS Cut Line= 2
     1763294.505      401409.087       1763332.7      400897.802
#Sta/Elev= 30
       0  933.88    11.9  930.09    31.8  921.73    43.7  915.65    63.6  903.58
    83.5  893.16    87.4  889.79    91.4  883.34    99.4   867.7   103.3  863.04
   111.3  855.99   115.3  854.06  118.53854.0103   135.1  855.36  148.15855.1623
   166.9  854.36   170.9  852.38   174.9  849.48  177.77848.7736   183.2  848.28
   190.8   847.8   198.2  848.86   210.6   850.2  296.24852.4442  355.48855.2789
   385.1856.4733   417.3  858.38  444.33858.7206  473.95  859.17   512.7  860.26
#Mann= 11 ,-1 , 0
       0     .12       0  118.53    .016       0  148.15     .08       0
  177.77     .06       0   183.2    .045       0   198.2     .06       0
  296.24     .12       0  355.48     .06       0   385.1     .08       0
  444.33     .06       0  473.95     .12       0
Bank Sta=183.2,198.2
XS Rating Curve= 0 ,0
Exp/Cntr=0.3,0.1

Type RM Length L Ch R = 1 ,20889.2 ,35.9,35.9,35.9
XS GIS Cut Line= 2
     1763356.137      401423.844     1763396.936      400901.274
#Sta/Elev= 30
       0  937.65    19.8  929.06    47.6  915.69    87.4  893.87    91.3  890.13
    95.3  883.56    99.3  875.58   103.2  869.04   107.2  865.07   119.1  856.15
   123.1  854.56  133.37855.2589   170.8   854.5   174.7  853.99   178.7  852.42
   182.7  849.87   186.6  847.75   190.6  847.29   198.6  847.93   210.5  849.99
   222.4  851.07   281.5852.7108  311.12854.0261   333.6  855.31  370.37856.2414
     400857.0652  429.62858.0477  488.87859.0082   518.5 859.429   524.2  859.64
#Mann= 11 ,-1 , 0
       0     .12       0  133.37    .016       0   182.7    .045       0
   198.6    .016       0   281.5     .06       0  311.12     .12       0
  370.37    .016       0     400     .08       0  429.62     .12       0
  488.87     .06       0   518.5     .12       0
#XS Ineff= 2 , 0
                          241.08          855.82
Permanent Ineff=
       F       F
Bank Sta=182.7,198.6
XS Rating Curve= 0 ,0
Exp/Cntr=0.3,0.1

Type RM Length L Ch R = 1 ,20853.2 ,68.4,68.1,67.8
XS GIS Cut Line= 2
     1763391.728       401425.58     1763432.489      400903.489
#Sta/Elev= 30
       0  934.42      40  916.41      80  895.37    91.9  888.28    95.9   885.2
    99.9  878.94   103.9  871.19   107.9  864.49   111.9  860.18   119.9  854.88
   123.9  854.63  135.11855.4802   147.9  855.41  164.73854.2302   171.9  853.61
   175.9  852.38   184.8  848.26   191.9  846.76   195.9  846.91   199.8  847.86
   207.9  850.22   215.9  851.19  253.61851.6426   295.8  852.55   323.8  855.07
   351.8   855.7   359.8  856.42  450.81857.5433  490.62858.5292   523.7  859.14
#Mann= 8 ,-1 , 0
       0     .12       0  135.11    .016       0  164.73     .06       0
   184.8    .045       0   199.8     .06       0  253.61    .016       0
  450.81     .12       0  490.62     .06       0
#XS Ineff= 2 , 0
                          257.25          855.56
Permanent Ineff=
       F       F
Bank Sta=184.8,199.8
XS Rating Curve= 0 ,0
Exp/Cntr=0.3,0.1

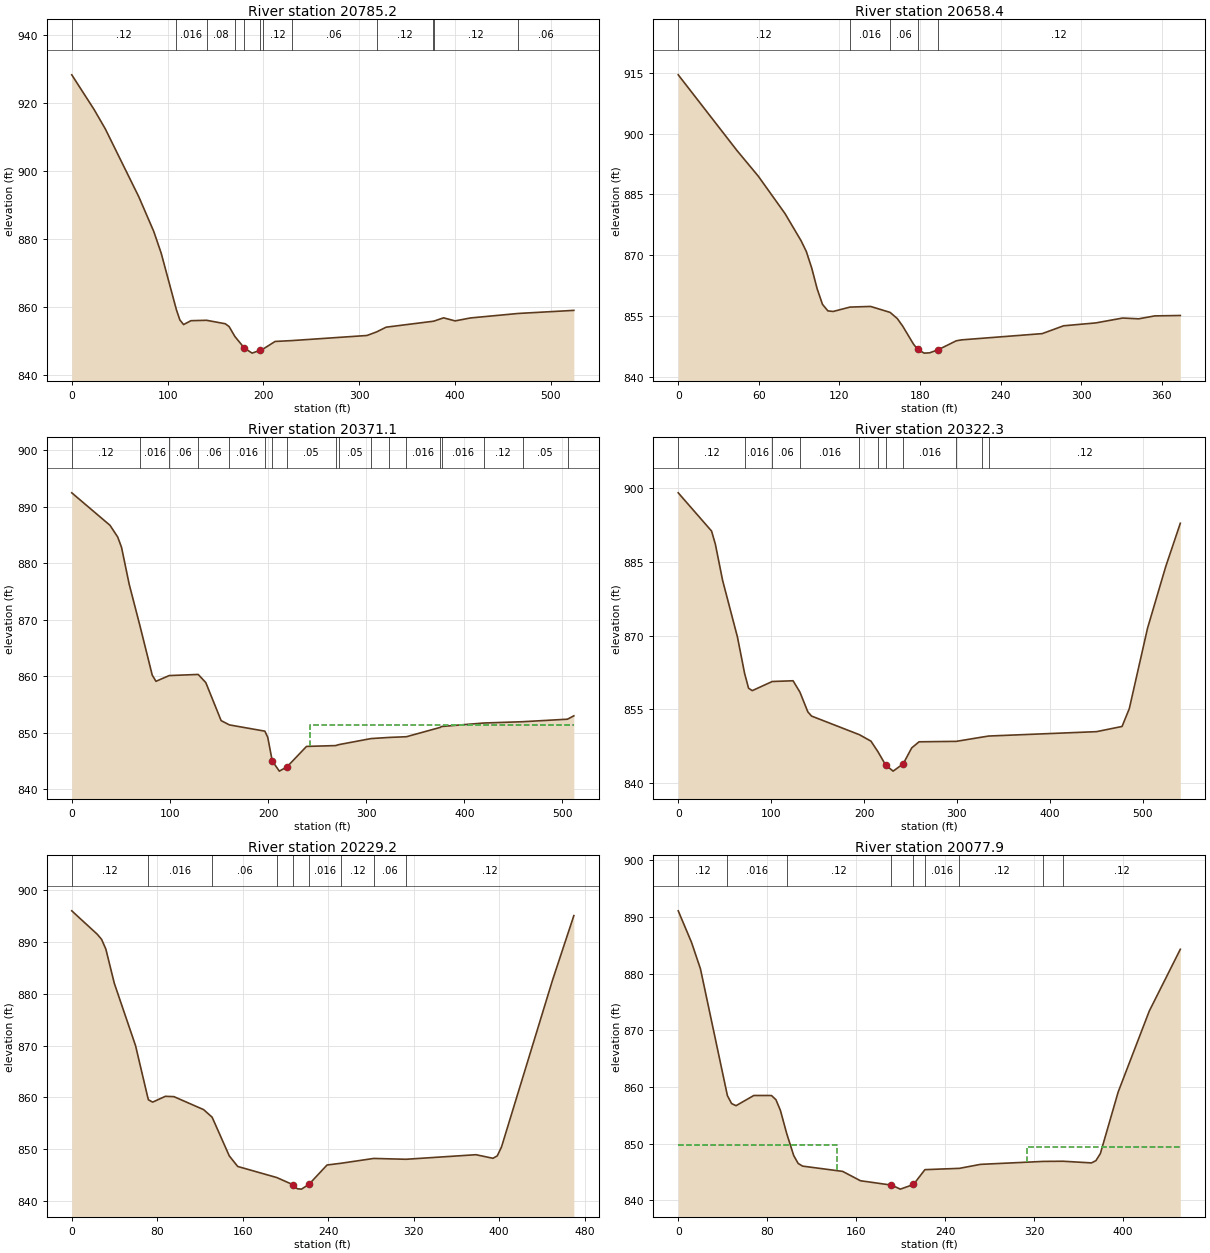
Type RM Length L Ch R = 1 ,20785.2 ,126.2,126.8,126.8
XS GIS Cut Line= 3
     1763417.781      401420.793     1763469.864      401299.265
     1763495.433      400908.273
#Sta/Elev= 30
       0  928.39    23.3  918.17      35  912.46      70  892.42    85.6  882.21
    93.3  875.85  109.21859.1509   112.8  856.15   116.7  854.78   124.4  855.92
  140.62856.0427   160.2  855.02   164.2  854.19  170.22851.2699   180.2  847.83
   188.2  846.36   196.2  847.17  199.82847.5953   212.2   849.8  229.42850.0486
   308.1  851.56  318.21852.6229   328.1  854.01  377.41 855.762   377.8855.7835
   388.1  856.76   400.1  855.86   416.1  856.73  466.21858.0586     524  858.96
#Mann= 12 ,-1 , 0
       0     .12       0  109.21    .016       0  140.62     .08       0
  170.22     .06       0   180.2    .045       0   196.2     .06       0
  199.82     .12       0  229.42     .06       0  318.21     .12       0
  377.41     .08       0   377.8     .12       0  466.21     .06       0
Bank Sta=180.2,196.2
XS Rating Curve= 0 ,0
Exp/Cntr=0.3,0.1

Type RM Length L Ch R = 1 ,20658.4 ,302.8,287.3,271.3
XS GIS Cut Line= 4
     1763620.026      401446.413     1763594.853      401301.448
     1763611.447      401082.404     1763611.447      401075.459
#Sta/Elev= 30
       0  914.47    43.7  895.82    59.6  889.48    79.5  880.26    91.5  873.54
    95.4  870.88    99.4  866.81   103.4  861.74   107.4  857.88   111.4  856.27
   115.3  856.12  127.88857.2038   143.2  857.36  157.73855.8963   163.1  854.37
   167.1  852.52   175.1   848.1   178.3  846.76   183.1  845.85   187.1  845.92
   193.3  846.65     207  848.89     211  849.12     271  850.66   286.9  852.59
   310.9   853.3   330.9   854.5   342.8  854.31   354.8  855.03   373.8  855.13
#Mann= 5 ,-1 , 0
       0     .12       0  127.88    .016       0  157.73     .06       0
   178.3    .045       0   193.3     .12       0
Bank Sta=178.3,193.3
XS Rating Curve= 0 ,0
Exp/Cntr=0.3,0.1

Type RM Length L Ch R = 1 ,20371.1 ,48.5,48.8,50
XS GIS Cut Line= 4
     1763897.905      401448.723      1763911.36      401301.045
     1763768.565      401097.052     1763683.495      401020.772
#Sta/Elev= 30
       0  892.43      39  886.68    46.8  884.62    50.7   882.8    58.5  876.28
   69.53868.8834      82   860.2    85.8   859.1   99.19860.1142  128.84860.3153
   136.6  858.87   152.2  852.15   160.7851.3923  196.76850.2878   199.7   849.2
   204.3  845.02   211.5  843.22   219.3  843.97   239.2  847.59  268.86847.7356
  272.17847.9082  304.92848.9745  323.67849.1816  340.97849.3026  375.18850.9399
  377.02851.1144  419.93851.7298   459.6851.9567  505.14 852.403   511.6     853
#Mann= 18 ,-1 , 0
       0     .12       0   69.53    .016       0   99.19     .06       0
  128.84     .06       0   160.7    .016       0  196.76     .05       0
   204.3    .045       0   219.3     .05       0  268.86    .016       0
  272.17     .05       0  304.92    .016       0  323.67     .06       0
  340.97    .016       0  375.18      .1       0  377.02    .016       0
  419.93     .12       0   459.6     .05       0  505.14      .1       0
#XS Ineff= 2 , 0
       0                   243.2       0   851.4
Permanent Ineff=
       F       F
Bank Sta=204.3,219.3
XS Rating Curve= 0 ,0
Exp/Cntr=0.3,0.1

Type RM Length L Ch R = 1 ,20322.3 ,74.6,93.1,110.7
XS GIS Cut Line= 4
     1763936.967      401450.459     1763956.065      401288.133
     1763823.252      401074.591     1763854.502      400953.063
#Sta/Elev= 30
       0   899.1    35.9   891.3    39.9  888.67    47.8  881.22    63.8  869.64
   71.47862.2465    75.7  859.25    79.7  858.76  101.21860.6188   123.6  860.77
  130.95858.4628   139.5  854.43   143.5  853.57     195  849.77   207.4  848.46
  214.83846.3403   223.3  843.57   231.3  842.34   242.1  843.82   251.3  847.08
   259.2  848.32  299.35848.4141  326.68  849.27  334.13849.4961   450.2  850.39
   477.7  851.45   485.5  855.09   505.1  871.47   524.7  884.06   540.4  892.89
#Mann= 11 ,-1 , 0
       0     .12       0   71.47    .016       0  101.21     .06       0
  130.95    .016       0     195     .06       0  214.83    .016       0
   223.3    .045       0   242.1    .016       0  299.35     .12       0
  326.68    .016       0  334.13     .12       0
Bank Sta=223.3,242.1
XS Rating Curve= 0 ,0
Exp/Cntr=0.3,0.1

Type RM Length L Ch R = 1 ,20229.2 ,149.1,151.3,153.6
XS GIS Cut Line= 2
     1763963.877      401448.723     1764064.827      400989.783
#Sta/Elev= 30
       0  896.04    23.9  891.51    27.9  890.53    31.9  888.65    39.8  882.05
    59.7  869.99    70.9 860.194    71.7  859.54    75.7  859.08    87.6   860.2
    95.6  860.14   123.4  857.63  131.38856.1647   147.4   848.7   155.3  846.65
  191.87844.5076   207.1  843.12   211.1  842.34     215  842.27  222.11843.2187
   238.9  846.93  252.35847.2762  282.59848.1997  312.83848.0379   378.3  848.92
   394.2  848.23   398.2  848.69   402.2  850.42     450  882.68   469.9  895.11
#Mann= 9 ,-1 , 0
       0     .12       0    70.9    .016       0  131.38     .06       0
  191.87     .12       0   207.1    .045       0  222.11    .016       0
  252.35     .12       0  282.59     .06       0  312.83     .12       0
Bank Sta=207.1,222.11
XS Rating Curve= 0 ,0
Exp/Cntr=0.3,0.1

Type RM Length L Ch R = 1 ,20077.9 ,321.8,325.9,330
XS GIS Cut Line= 2
     1764092.349      401472.161     1764233.181      401043.038
#Sta/Elev= 30
       0  891.11      12  885.52      20  880.86   44.24858.4906      48  857.09
      52  856.72      68  858.52    83.9  858.51    87.9  857.77    91.9  855.89
   97.55851.8137   103.9   847.9   107.9  846.52   111.9  846.05   147.9  845.12
   163.9  843.47   191.8   842.7   199.8  841.99   211.6  842.81  221.89845.4269
  252.97845.6585   271.8  846.36  328.39846.8835  346.23846.9114   371.7  846.62
   375.7  847.02   379.7  848.27   395.7  859.13   423.7  873.43   451.6  884.32
#Mann= 9 ,-1 , 0
       0     .12       0   44.24    .016       0   97.55     .12       0
   191.8    .045       0   211.6     .12       0  221.89    .016       0
  252.97     .12       0  328.39    .016       0  346.23     .12       0
#XS Ineff= 2 , 0
          142.49  849.72  313.86          849.41
Permanent Ineff=
       F       F
Bank Sta=191.8,211.6
XS Rating Curve= 0 ,0
Exp/Cntr=0.3,0.1

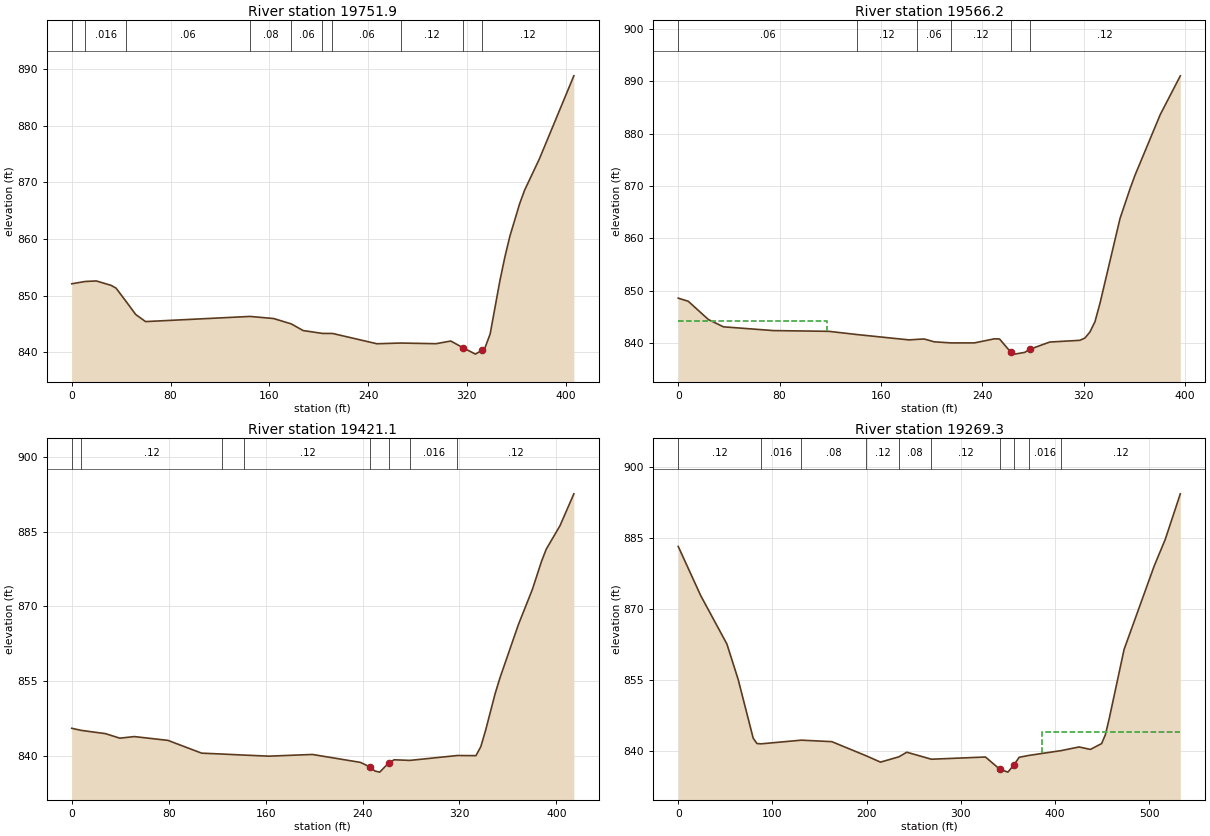
Type RM Length L Ch R = 1 ,19751.9 ,181.6,185.7,189.2
XS GIS Cut Line= 2
     1764306.658      401536.691     1764496.603      401177.061
#Sta/Elev= 30
       0   852.1   10.79852.5049    19.9   852.6    31.9  851.82    35.9  851.33
   44.19848.9293    51.8  846.68    59.8  845.43   144.4 846.342   163.5  845.97
   177.8 845.026   187.4  843.85  203.08843.3432   211.2843.3395   247.2  841.52
  266.32841.6468   295.1  841.53     307     842     317  840.81     327  839.69
     332  840.35   334.9  840.91   338.9  843.24   346.9  852.76   350.9  856.89
   354.9  860.51   362.8  866.23   366.8  868.61   378.8  874.14   406.7  888.79
#Mann= 10 ,-1 , 0
       0     .06       0   10.79    .016       0   44.19     .06       0
   144.4     .08       0   177.8     .06       0  203.08     .08       0
   211.2     .06       0  266.32     .12       0     317    .045       0
     332     .12       0
Bank Sta=317,332
XS Rating Curve= 0 ,0
Exp/Cntr=0.3,0.1

Type RM Length L Ch R = 1 ,19566.2 ,144.1,145.1,146.5
XS GIS Cut Line= 2
     1764434.416      401580.072     1764675.287      401265.249
#Sta/Elev= 30
       0  848.57     7.9  847.98    23.8  844.49    35.7  843.09    75.3  842.37
   118.9  842.23  141.01841.6169   182.3  840.59  188.87840.6978   194.2  840.76
   202.2  840.22  215.39840.0167   233.9  840.02   249.7   840.8   253.7  840.76
   262.5  838.26   265.6  837.87   273.5   838.2   277.5  838.79   293.3  840.18
   317.1  840.51   321.1  840.95     325  842.09     329  844.05     333  847.61
   348.8   863.8   356.8  869.55   360.7  872.11   380.5  883.64   396.4  891.08
#Mann= 6 ,-1 , 0
       0     .06       0  141.01     .12       0  188.87     .06       0
  215.39     .12       0   262.5    .045       0   277.5     .12       0
#XS Ineff= 2 , 0
          117.59  844.11
Permanent Ineff=
       F       F
Bank Sta=262.5,277.5
XS Rating Curve= 0 ,0
Exp/Cntr=0.3,0.1

Type RM Length L Ch R = 1 ,19421.1 ,155.4,151.9,148.1
XS GIS Cut Line= 3
     1764545.374      401651.274      1764774.54      401382.177
     1764799.769      401326.674
#Sta/Elev= 30
       0  845.59    7.85845.1722    27.8  844.52    39.7  843.61    51.6  843.93
    79.4  843.17   107.2  840.61  124.24840.4301  142.54840.2169   162.8  840.01
   198.6  840.35   238.3  838.76   246.5   837.8   250.2  837.03   254.2  836.81
   261.5  838.64   266.1  839.28   279.2 839.161  318.22840.1387   333.6  840.11
   337.6   841.9   341.5  845.13   349.5  852.59   353.5  855.75   368.7  866.41
   380.1  873.36   387.8  879.09   391.6  881.46     403  886.19   414.4  892.56
#Mann= 8 ,-1 , 0
       0    .016       0    7.85     .12       0  124.24     .06       0
  142.54     .12       0   246.5    .045       0   261.5     .12       0
   279.2    .016       0  318.22     .12       0
Bank Sta=246.5,261.5
XS Rating Curve= 0 ,0
Exp/Cntr=0.3,0.1

Type RM Length L Ch R = 1 ,19269.3 ,223.4,223.6,203.7
XS GIS Cut Line= 2
     1764651.276      401845.719     1764927.557      401389.729
#Sta/Elev= 30
       0  883.25    23.9  872.87    51.7  862.66    63.7  855.16    79.6  842.81
    83.6  841.67   87.98841.6088  130.74 842.383   163.1  842.07  199.81839.0667
   214.8  837.75  234.35 838.868   242.7  839.84  268.88 838.363   326.3  838.83
   341.3  836.28   350.1  835.64   356.3  837.12   362.1  838.77  372.48839.1668
  407.02840.1891   425.7  840.95   437.7  840.43   449.6  841.66   453.6  843.52
   457.6  846.84   473.5  861.53   505.3  879.04   517.2  884.74   533.2  894.35
#Mann= 10 ,-1 , 0
       0     .12       0   87.98    .016       0  130.74     .08       0
  199.81     .12       0  234.35     .08       0  268.88     .12       0
   341.3    .045       0   356.3     .12       0  372.48    .016       0
  407.02     .12       0
#XS Ineff= 2 , 0
                          386.65          844.11
Permanent Ineff=
       F       F
Bank Sta=341.3,356.3
XS Rating Curve= 0 ,0
Exp/Cntr=0.3,0.1