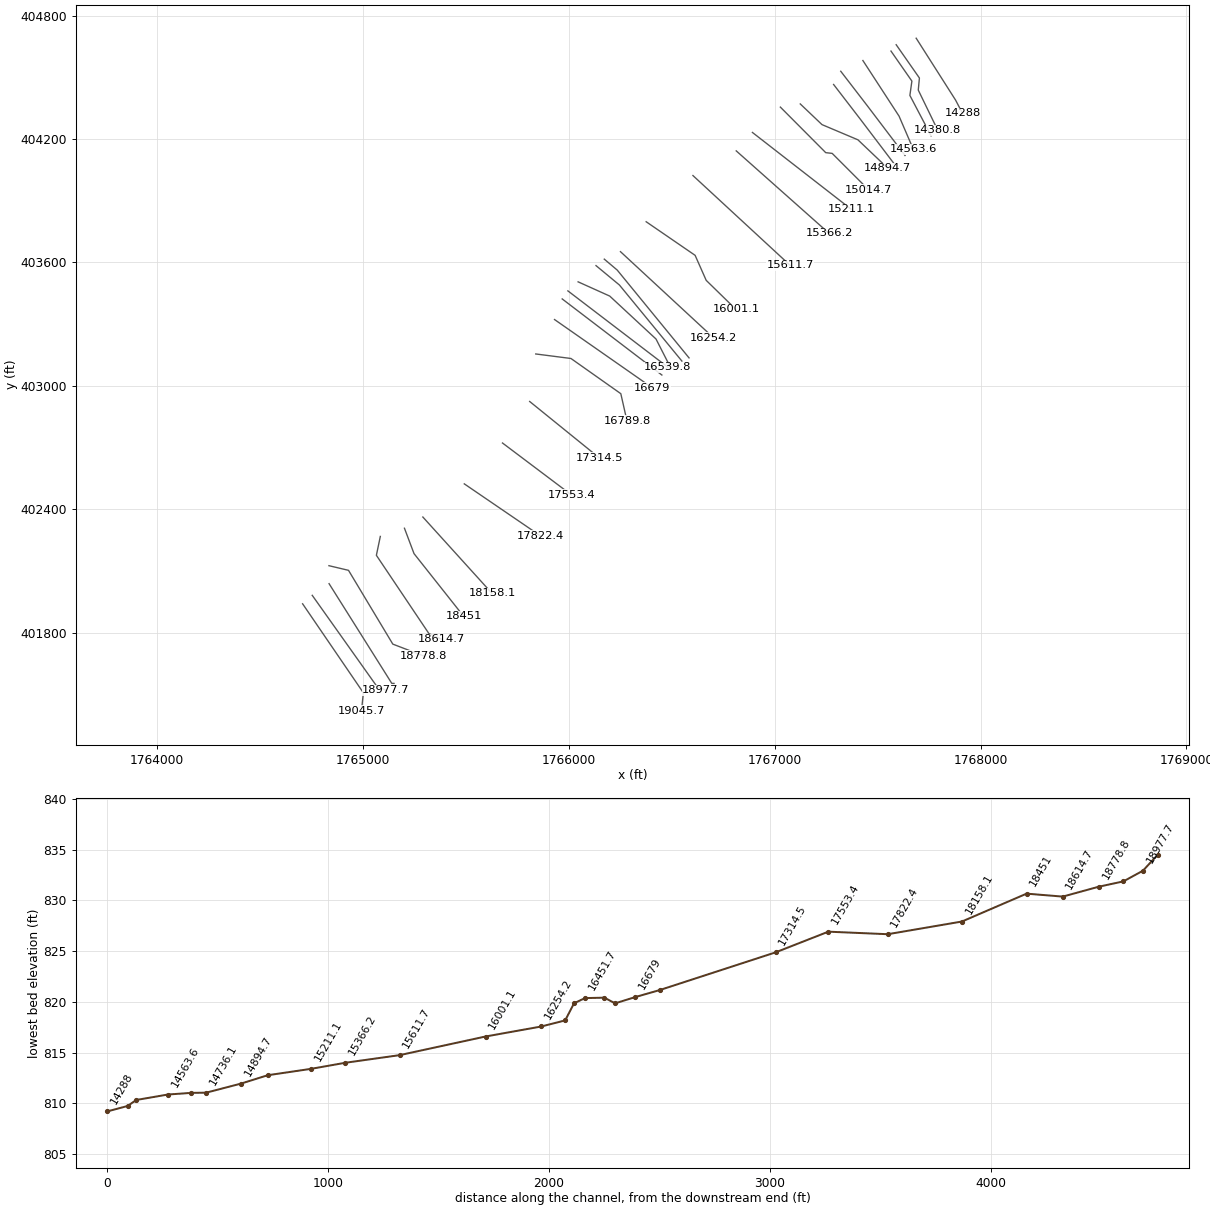
HEC-RAS study DRAWDYCK.prj: DRAWDYCK

--- DRAWDYCK.g01 (geometry) --- (continued)

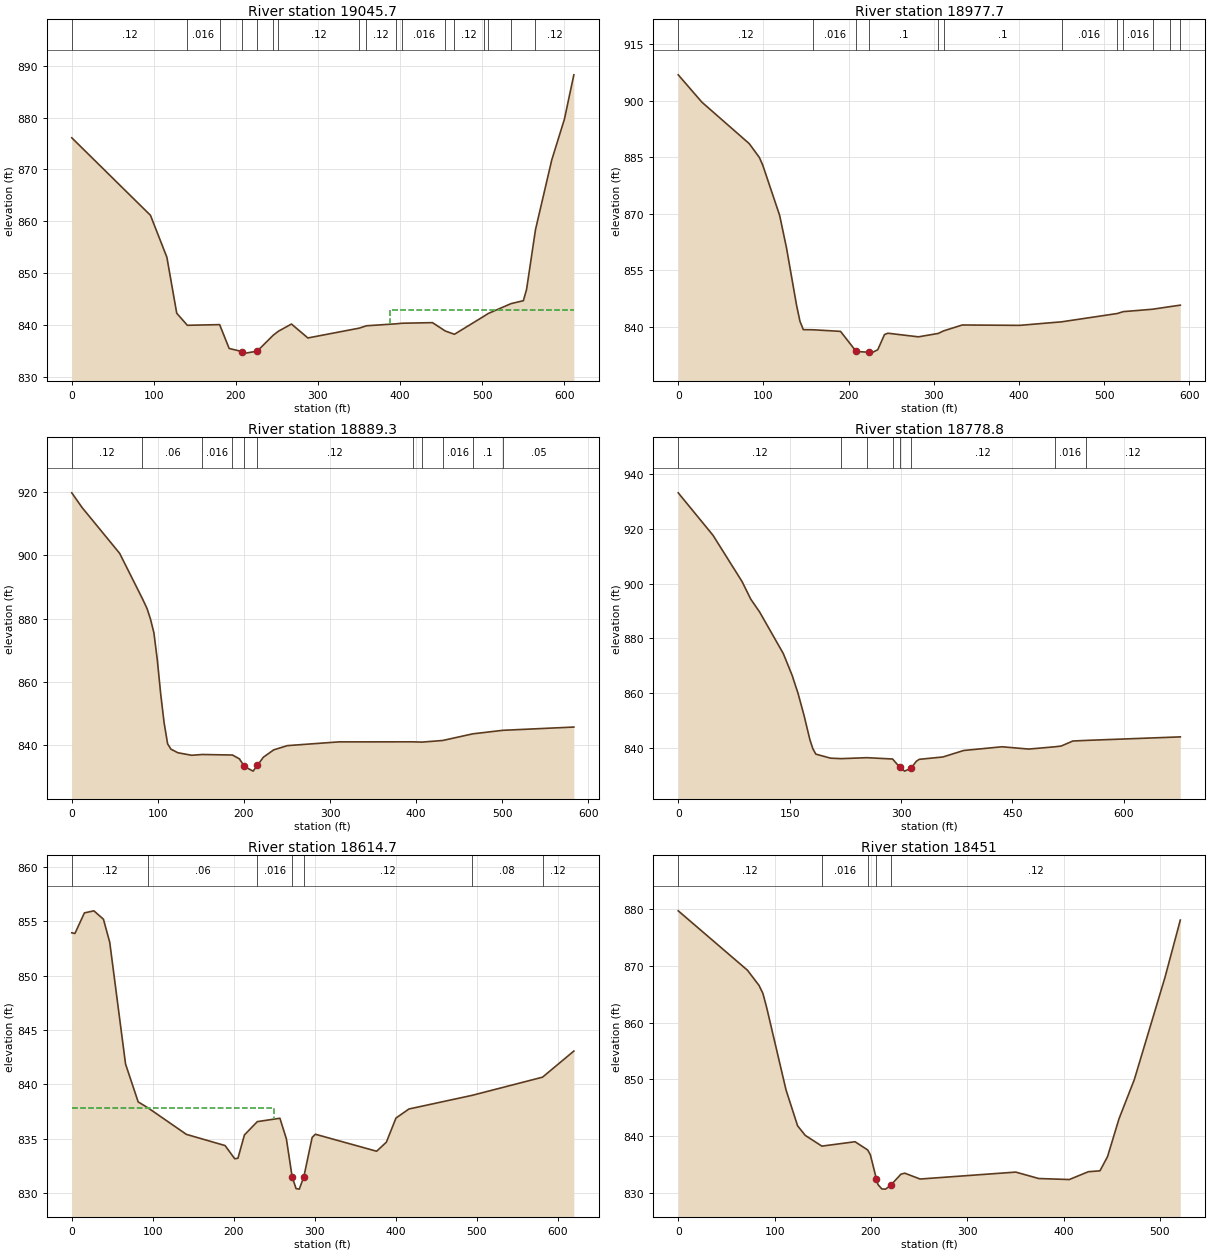
Type RM Length L Ch R = 1 ,19045.7 ,66.3,68,89.6
XS GIS Cut Line= 3
     1764706.065      401941.779     1765001.203      401509.487
     1764992.102      401421.578
#Sta/Elev= 30
       0  876.12    95.9  861.15   115.9  853.05   127.9  842.24  140.83839.9058
  180.18840.0349   191.8  835.43   207.8  834.82   211.8  834.53   225.9  834.91
   245.6838.0035  251.71 838.751   267.7  840.15   287.7  837.46  350.36839.3573
     359839.8125  394.76840.1854  402.74840.3036   439.5  840.42  455.12838.8052
  466.29  838.17  502.05841.6357   507.5842.1875  535.38844.0941   550.3  844.66
   554.2  846.84  565.07858.3845   584.9  871.85   600.3  879.71   611.8  888.28
#Mann= 17 ,-1 , 0
       0     .12       0  140.83    .016       0  180.18     .12       0
   207.8    .045       0   225.9     .12       0   245.6    .016       0
  251.71     .12       0  350.36    .016       0     359     .12       0
  394.76     .06       0  402.74    .016       0  455.12     .06       0
  466.29     .12       0  502.05     .06       0   507.5     .12       0
  535.38     .06       0  565.07     .12       0
#XS Ineff= 2 , 0
                          388.19          842.86
Permanent Ineff=
       F       F
Bank Sta=207.8,225.9
XS Rating Curve= 0 ,0
Exp/Cntr=0.3,0.1

Type RM Length L Ch R = 1 ,18977.7 ,89.7,88.4,87.1
XS GIS Cut Line= 3
     1764752.839      401982.872      1765065.44      401542.473
     1765110.591      401522.082
#Sta/Elev= 30
       0  906.89    27.8  899.62    83.4   888.6    95.3  884.92    99.3  882.87
   119.1  869.53   127.1  860.95     139   845.6     143  841.35   146.9  839.17
  158.44839.1378   190.6  838.71     209  833.37     224  833.16   226.4  832.93
   234.3  833.83   242.2  837.86   246.2  838.22     282  837.26  305.32838.1616
  311.52838.8366   333.6  840.41   401.1  840.31   450.2841.2488  515.62843.4587
  522.64843.9576  556.95844.5933  577.31845.2793  589.36845.6719   589.6  845.67
#Mann= 12 ,-1 , 0
       0     .12       0  158.44    .016       0     209    .045       0
     224      .1       0  305.32    .016       0  311.52      .1       0
   450.2    .016       0  515.62     .05       0  522.64    .016       0
  556.95     .05       0  577.31    .016       0  589.36     .05       0
Bank Sta=209,224
XS Rating Curve= 0 ,0
Exp/Cntr=0.3,0.1

Type RM Length L Ch R = 1 ,18889.3 ,110.9,110.4,109.9
XS GIS Cut Line= 3
     1764834.653      402039.556     1765139.341      401555.181
     1765150.189      401554.902
#Sta/Elev= 30
       0  919.64    11.9  915.03    55.6  900.56   81.96886.3065    87.4  883.18
    91.4  879.85    95.4  875.49    99.4  866.83   103.3  856.15   107.3  847.04
   111.3   840.5   115.2  838.81   123.2  837.68   139.1  836.88  151.74837.1237
  186.64836.9576   194.7  835.75   200.5  833.35   210.6  831.88   215.5  833.67
   222.5  836.26   234.5  838.58   250.4  839.92     310   841.1     396 841.119
  406.87 841.031  430.89841.5483  465.78843.6404  500.68844.7502   583.1  845.78
#Mann= 11 ,-1 , 0
       0     .12       0   81.96     .06       0  151.74    .016       0
  186.64     .12       0   200.5    .045       0   215.5     .12       0
     396      .1       0  406.87     .12       0  430.89    .016       0
  465.78      .1       0  500.68     .05       0
Bank Sta=200.5,215.5
XS Rating Curve= 0 ,0
Exp/Cntr=0.3,0.1

Type RM Length L Ch R = 1 ,18778.8 ,163,164.1,165.3
XS GIS Cut Line= 4
     1764834.016      402126.908     1764929.054      402104.399
     1765144.332      401745.892     1765294.052      401688.424
#Sta/Elev= 30
       0  933.18    46.9  917.62      86   900.7    97.7  894.27   109.6  889.59
   141.5  874.38   153.4  866.42   161.4  859.77   169.4  851.77   177.3  842.88
   181.3  839.57   185.3  837.58   205.2   836.1  219.77835.9293  254.22836.2797
  288.68835.7953   298.5  832.74   304.8  831.36   313.5  832.41   320.7  834.98
   324.7  835.68   356.5  836.54   384.4  838.91   436.2  840.27     472  839.43
  507.24840.2623   515.8  840.54   531.5  842.38  549.33   842.6   676.2  843.89
#Mann= 8 ,-1 , 0
       0     .12       0  219.77     .06       0  254.22    .016       0
  288.68     .12       0   298.5    .045       0   313.5     .12       0
  507.24    .016       0  549.33     .12       0
Bank Sta=298.5,313.5
XS Rating Curve= 0 ,0
Exp/Cntr=0.3,0.1

Type RM Length L Ch R = 1 ,18614.7 ,161.8,163.7,166
XS GIS Cut Line= 4
     1765083.588      402269.079     1765064.471      402177.316
     1765319.679      401797.108     1765381.979      401769.221
#Sta/Elev= 30
       0  853.92     3.9  853.86    15.6  855.75    27.3  855.94    39.1  855.17
    46.9  853.04    66.4  841.87      82  838.39    94.2837.8425   141.5  835.41
   189.3  834.38   201.2  833.17   205.2  833.22   213.2  835.36  229.09836.5794
     257  836.89     265  834.99  272.06831.5238   276.9  830.43   280.9  830.38
  286.49   831.5   296.8  835.13   300.8  835.42   376.4  833.86   388.4  834.69
   400.3  836.91   416.3  837.74  494.06838.9892   581.2  840.66   619.9  843.06
#Mann= 7 ,-1 , 0
       0     .12       0    94.2     .06       0  229.09    .016       0
  272.06    .045       0  286.49     .12       0  494.06     .08       0
   581.2     .12       0
#XS Ineff= 2 , 0
          249.81  837.84
Permanent Ineff=
       F       F
Bank Sta=272.06,286.49
XS Rating Curve= 0 ,0
Exp/Cntr=0.3,0.1

Type RM Length L Ch R = 1 ,18451   ,288.1,292.9,294.9
XS GIS Cut Line= 3
     1765200.856      402308.966     1765247.352      402185.583
      1765488.95      401880.441
#Sta/Elev= 30
       0  879.69    71.9  869.22    83.9  866.54    87.9  865.14    91.9  862.58
   111.9  848.13   123.9  841.82   131.8  840.14  149.09838.2457   183.5  839.02
  196.67837.5663   199.4  836.72   205.7  832.46   207.3  831.48   211.3   830.7
   215.2  830.67   220.7  831.38   231.1   833.3   235.1  833.48     251  832.45
   350.3  833.67   374.1  832.54   405.9  832.36   425.7  833.74   437.7  833.89
   445.6  836.41   457.5  843.07   473.4  849.98   505.2  867.98   521.1  878.06
#Mann= 5 ,-1 , 0
       0     .12       0  149.09    .016       0  196.67     .12       0
   205.7    .045       0   220.7     .12       0
Bank Sta=205.7,220.7
XS Rating Curve= 0 ,0
Exp/Cntr=0.3,0.1

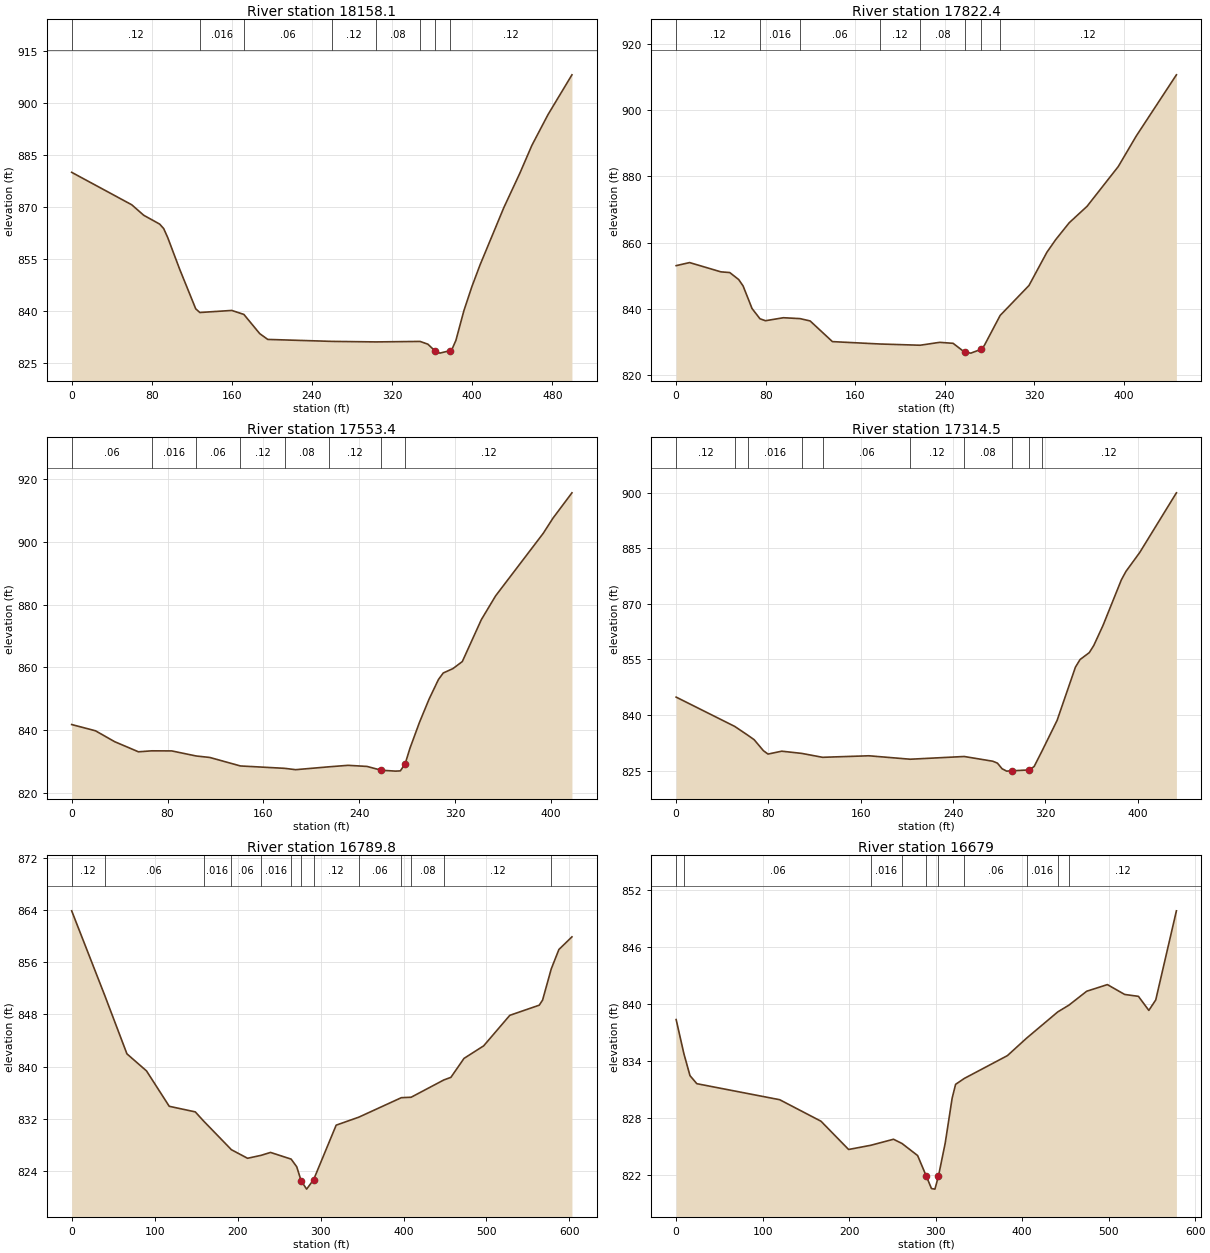
Type RM Length L Ch R = 1 ,18158.1 ,329.8,335.6,340.9
XS GIS Cut Line= 2
     1765290.243      402363.398       1765625.7      401993.181
#Sta/Elev= 30
       0  880.01      60  870.66    71.9  867.65    87.9  865.09    91.9   863.8
    95.9  861.23   107.9  852.06   123.9  840.68  128.01839.6224   159.9  840.22
  171.99839.0655   187.8  833.54   195.8  831.87  259.97831.3017  303.95831.1523
  347.94831.2904   355.7   830.5   362.5  828.66   367.7  827.92   377.5  828.61
   379.7  828.96   383.7  831.58   391.7  840.15   399.7   847.1   407.7  853.25
   431.6  869.86   447.6  879.77   459.6  887.78   475.6  896.59   499.6   908.1
#Mann= 8 ,-1 , 0
       0     .12       0  128.01    .016       0  171.99     .06       0
  259.97     .12       0  303.95     .08       0  347.94     .12       0
   362.5    .045       0   377.5     .12       0
Bank Sta=362.5,377.5
XS Rating Curve= 0 ,0
Exp/Cntr=0.3,0.1

Type RM Length L Ch R = 1 ,17822.4 ,269.9,269,267.7
XS GIS Cut Line= 2
     1765491.554      402524.538     1765860.635      402272.614
#Sta/Elev= 30
       0  853.04      12  853.97    39.9  851.18    47.9  850.96    55.9  848.84
    59.8  846.93    67.8  840.12   74.89837.0234    79.8  836.44    95.8  837.34
  110.65837.0736   119.7  836.37   139.6  830.14  182.17  829.42  217.93829.0484
   235.4  829.92   247.4  829.63   257.7  826.96   263.3  826.67   272.7  827.87
   275.3  828.98  289.45 838.035   315.2  847.06   331.2  857.08   339.1   860.9
   351.1  865.96   367.1  870.94     395  882.94     411  892.11   446.9  910.57
#Mann= 8 ,-1 , 0
       0     .12       0   74.89    .016       0  110.65     .06       0
  182.17     .12       0  217.93     .08       0   257.7    .045       0
   272.7     .08       0  289.45     .12       0
Bank Sta=257.7,272.7
XS Rating Curve= 0 ,0
Exp/Cntr=0.3,0.1

Type RM Length L Ch R = 1 ,17553.4 ,240.1,238.8,237
XS GIS Cut Line= 2
     1765677.182      402723.012     1766010.677       402471.91
#Sta/Elev= 30
       0  841.79    19.9  839.79    35.8  836.33    55.7  833.09    66.9833.3975
    83.5  833.37  103.87831.7553   115.3  831.28  140.85828.5696  177.82827.8086
   186.9  827.38  214.79828.2984   230.6  828.77   246.5  828.42   258.4   827.2
   270.4  826.92   274.3     827   278.3  829.28   282.3   834.2   290.2  842.43
   298.2  849.84   306.1  856.16   310.1  858.24   318.1  859.62     326  861.88
   341.9  875.27   353.8  882.85   393.6  902.84   401.6  907.61   417.5  915.73
#Mann= 8 ,-1 , 0
       0     .06       0    66.9    .016       0  103.87     .06       0
  140.85     .12       0  177.82     .08       0  214.79     .12       0
   258.4    .045       0   278.3     .12       0
Bank Sta=258.4,278.3
XS Rating Curve= 0 ,0
Exp/Cntr=0.3,0.1

Type RM Length L Ch R = 1 ,17314.5 ,522,524.8,518.8
XS GIS Cut Line= 2
     1765809.262      402924.712     1766146.178      402651.892
#Sta/Elev= 30
       0  844.85   50.84836.9277   61.87834.6182    67.6  833.36    75.6   830.4
    79.6  829.48    91.5  830.26   108.8 829.665  126.85828.6078     167  829.02
  202.86828.0905  249.61828.8276   274.4  827.55   278.4  827.04   282.4  825.53
   286.4  824.88   290.7  824.96   305.7   825.2   310.2  826.12  316.87830.2022
   330.1  838.56     346  852.94     350  854.98     358  856.85   361.9  858.78
   369.9  864.19   385.8  876.49   389.8  878.77   401.7  883.86   433.5  899.96
#Mann= 10 ,-1 , 0
       0     .12       0   50.84     .06       0   61.87    .016       0
   108.8     .08       0  126.85     .06       0  202.86     .12       0
  249.61     .08       0   290.7    .045       0   305.7     .08       0
  316.87     .12       0
Bank Sta=290.7,305.7
XS Rating Curve= 0 ,0
Exp/Cntr=0.3,0.1

Type RM Length L Ch R = 1 ,16789.8 ,110.6,110.7,110.8
XS GIS Cut Line= 4
     1765838.776      403155.615     1766009.884      403133.619
     1766252.072      402962.612     1766281.685      402831.881
#Sta/Elev= 30
       0  863.93   39.86850.9285    66.6  841.95    90.2  839.33   117.6  833.89
     149  833.03  158.98831.6313  192.55827.2163     212   825.9  228.39826.3552
   239.7   826.8  264.55825.7711   271.3  824.59   276.6  822.43   283.2  821.16
   291.6  822.61   318.8  830.99  346.17832.2229  397.38835.2138  409.17  835.28
  448.59837.9387   457.1  838.34   472.9  841.25   496.6  843.18   528.1  847.87
   563.6  849.43   567.6  850.21  578.06855.0072   587.3  857.99     603  859.93
#Mann= 13 ,-1 , 0
       0     .12       0   39.86     .06       0  158.98    .016       0
  192.55     .06       0  228.39    .016       0  264.55     .12       0
   276.6    .045       0   291.6     .12       0  346.17     .06       0
  397.38     .12       0  409.17     .08       0  448.59     .12       0
  578.06     .06       0
Bank Sta=276.6,291.6
XS Rating Curve= 0 ,0
Exp/Cntr=0.3,0.1

Type RM Length L Ch R = 1 ,16679   ,92.2,91.4,90.3
XS GIS Cut Line= 2
     1765930.023      403322.855     1766404.292      402991.757
#Sta/Elev= 30
       0  838.35    8.98834.7431      16  832.44    23.9  831.59   119.7   829.9
   167.5  827.63   199.4  824.65  225.11825.0954   251.3  825.73  261.13825.2839
   279.2  824.01  289.32  821.82   295.2  820.53   299.2  820.47   303.2  821.81
   311.1  825.33   319.1  830.06   323.1  831.52  333.17832.1442     383  834.55
  405.21836.3941  441.23839.1608  453.98839.8649   474.7  841.34   498.6  842.04
   518.6     841   534.5   840.8   546.5  839.32   554.5  840.42   578.4  849.82
#Mann= 10 ,-1 , 0
       0     .12       0    8.98     .06       0  225.11    .016       0
  261.13     .12       0  289.32    .045       0   303.2     .12       0
  333.17     .06       0  405.21    .016       0  441.23     .06       0
  453.98     .12       0
Bank Sta=289.32,303.2
XS Rating Curve= 0 ,0
Exp/Cntr=0.3,0.1

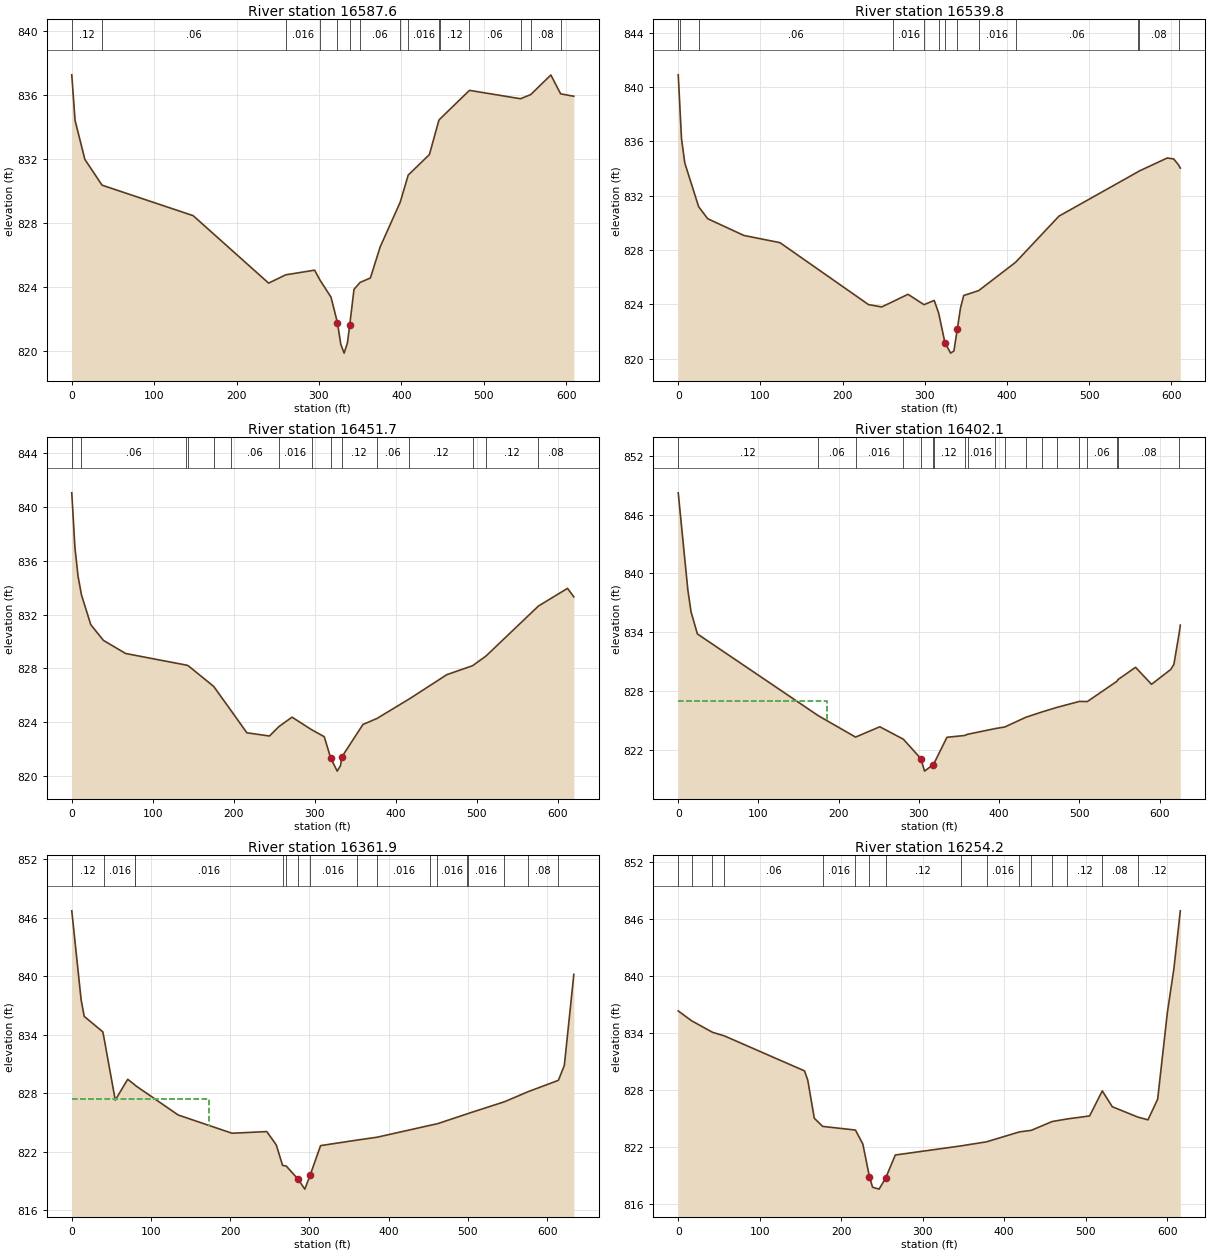
Type RM Length L Ch R = 1 ,16587.6 ,47.9,47.9,47.9
XS GIS Cut Line= 2
     1765967.249      403422.976     1766451.538      403053.302
#Sta/Elev= 30
       0  837.26       4  834.41    15.9  831.97   36.75830.3581   147.3  828.45
   238.9  824.23  259.69824.7489   294.7  825.04  301.23824.4221   314.6  823.35
   322.4  821.76   326.5   820.4   330.5  819.85   334.5  820.48   337.4  821.64
   342.5  823.84  349.91824.2737   362.4  824.55   374.3   826.5  398.58829.2922
  408.32 830.991     434  832.27  445.48834.4124  447.26834.5209  482.63836.2891
  544.62835.7645  556.95836.0231   581.4  837.25   593.3  836.07   609.3  835.92
#Mann= 15 ,-1 , 0
       0     .12       0   36.75     .06       0  259.69    .016       0
  301.23     .12       0   322.4    .045       0   337.4    .016       0
  349.91     .06       0  398.58     .12       0  408.32    .016       0
  445.48     .06       0  447.26     .12       0  482.63     .06       0
  544.62     .12       0  556.95     .08       0   593.3     .12       0
Bank Sta=322.4,337.4
XS Rating Curve= 0 ,0
Exp/Cntr=0.3,0.1

Type RM Length L Ch R = 1 ,16539.8 ,90.2,88,85.9
XS GIS Cut Line= 2
     1765994.982      403462.026     1766480.686      403091.271
#Sta/Elev= 30
       0  840.89    1.86838.7045       4  836.19       8   834.4   24.84831.1855
    35.9   830.3    79.9  829.07   123.8  828.54   231.6  823.98   247.6  823.81
  261.96824.2223   279.6  824.74  299.12823.9752   311.5  824.29  316.91823.3618
   324.6  821.17   331.5  820.41   335.5  820.57   339.6  822.18   343.5  823.73
   347.4  824.65  365.59825.0093  410.59827.0971   463.3  830.49  559.22833.7451
   560.3 833.791   595.1  834.77     603   834.7  608.98834.2472     611  834.03
#Mann= 13 ,-1 , 0
       0     .06       0    1.86     .12       0   24.84     .06       0
  261.96    .016       0  299.12     .12       0  316.91    .016       0
   324.6    .045       0   339.6     .12       0  365.59    .016       0
  410.59     .06       0  559.22     .12       0   560.3     .08       0
  608.98     .12       0
Bank Sta=324.6,339.6
XS Rating Curve= 0 ,0
Exp/Cntr=0.3,0.1

Type RM Length L Ch R = 1 ,16451.7 ,52.7,49.7,46.5
XS GIS Cut Line= 4
     1766044.606      403506.015     1766198.151      403436.865
     1766423.078      403228.237      1766488.87      403099.251
#Sta/Elev= 30
       0  841.05     3.9  836.99     7.8  834.84   11.98833.4717    23.5  831.25
    39.2  830.08    66.6  829.11  141.55828.2488  143.83 828.202   175.3826.6632
     197824.8435   216.2  823.22   244.1  822.98  255.87 823.682     272  824.38
  296.15823.4488   311.8  822.93   319.8  821.33   327.8  820.37   331.8  820.77
  333.58  821.43   359.6  823.84  376.72824.2784  417.01825.7423   463.2  827.54
  494.91828.2023  511.31 828.912  576.31832.6397   612.2  833.95     620  833.32
#Mann= 15 ,-1 , 0
       0     .12       0   11.98     .06       0  141.55     .12       0
  143.83     .06       0   175.3     .12       0     197     .06       0
  255.87    .016       0  296.15     .08       0   319.8    .045       0
  333.58     .12       0  376.72     .06       0  417.01     .12       0
  494.91     .06       0  511.31     .12       0  576.31     .08       0
Bank Sta=319.8,333.58
XS Rating Curve= 0 ,0
Exp/Cntr=0.3,0.1

Type RM Length L Ch R = 1 ,16402.1 ,40.9,40.2,39.6
XS GIS Cut Line= 3
     1766131.539      403584.855     1766245.255      403490.671
     1766548.807      403121.092
#Sta/Elev= 30
       0  848.22      12  838.31      16  836.08    23.9  833.84  174.48825.5164
  221.02823.3284   251.3  824.38  280.67823.1106   302.4  821.14   307.1  819.86
   317.4   820.5  318.89 820.649     335  823.31  357.12823.4921  360.62823.6145
  395.34 824.197  407.15824.3593  433.56825.3562  453.69825.8968  471.78 826.348
  500.22826.9664     510  826.95  546.76829.0086  548.22829.1874   570.1  830.44
     590  828.71     614  830.22   617.9  830.74  624.67834.0204   625.9  834.74
#Mann= 19 ,-1 , 0
       0     .12       0  174.48     .06       0  221.02    .016       0
  280.67     .12       0   302.4    .045       0   317.4    .016       0
  318.89     .12       0  357.12     .06       0  360.62    .016       0
  395.34     .06       0  407.15    .016       0  433.56     .12       0
  453.69    .016       0  471.78     .12       0  500.22    .016       0
     510     .06       0  546.76    .016       0  548.22     .08       0
  624.67     .12       0
#XS Ineff= 2 , 0
          186.01  827.05
Permanent Ineff=
       F       F
Bank Sta=302.4,317.4
XS Rating Curve= 0 ,0
Exp/Cntr=0.3,0.1

Type RM Length L Ch R = 1 ,16361.9 ,103.8,107.6,111.3
XS GIS Cut Line= 3
     1766171.687      403616.322     1766234.621      403563.154
     1766583.568      403136.517
#Sta/Elev= 30
       0   846.7    11.8  837.59    15.7  835.88    39.2  834.29   41.27833.4154
    54.9   827.3    70.6  829.43   79.38828.8698   79.94828.8123   134.3  825.77
   202.2   823.9   246.1  824.07   258.1   822.7  266.03820.6052  270.66820.5385
   285.7  819.18   294.1  818.17   300.7  819.58     314  822.63  359.34823.1899
  385.14823.4891  452.64 824.719  461.45824.8739  499.29825.8959  499.61825.9079
  545.94827.1242  575.92828.1598  614.08829.3224   621.6  830.85   633.6  840.19
#Mann= 17 ,-1 , 0
       0     .12       0   41.27    .016       0   79.38     .12       0
   79.94    .016       0  266.03     .12       0  270.66    .016       0
   285.7    .045       0   300.7    .016       0  359.34     .12       0
  385.14    .016       0  452.64     .06       0  461.45    .016       0
  499.29     .06       0  499.61    .016       0  545.94     .12       0
  575.92     .08       0  614.08     .12       0
#XS Ineff= 2 , 0
          173.43  827.37
Permanent Ineff=
       F       F
Bank Sta=285.7,300.7
XS Rating Curve= 0 ,0
Exp/Cntr=0.3,0.1

Type RM Length L Ch R = 1 ,16254.2 ,263.1,253.1,242.7
XS GIS Cut Line= 2
     1766250.335      403652.716     1766702.657      403234.213
#Sta/Elev= 30
       0  836.32   16.28835.2892   42.04834.0711   56.52833.6968     155  830.01
     159  829.03     167  825.03  177.23824.1699  217.47823.7862   226.6  822.31
   234.7  818.86   238.5  817.77   246.5  817.57   254.4   818.7   266.4  821.16
  346.47822.1114  378.42 822.549  418.66823.5874  433.46823.7606   458.9 824.681
  476.95824.9478   504.9  825.27  520.44827.9052   532.7  826.24  563.93825.1537
   576.5  824.86   588.4  827.03   600.3  836.14   608.3  840.75   616.2  846.85
#Mann= 16 ,-1 , 0
       0    .016       0   16.28     .06       0   42.04     .12       0
   56.52     .06       0  177.23    .016       0  217.47     .12       0
   234.7    .045       0   254.4     .12       0  346.47     .06       0
  378.42    .016       0  418.66     .06       0  433.46     .12       0
   458.9     .06       0  476.95     .12       0  520.44     .08       0
  563.93     .12       0
Bank Sta=234.7,254.4
XS Rating Curve= 0 ,0
Exp/Cntr=0.3,0.1

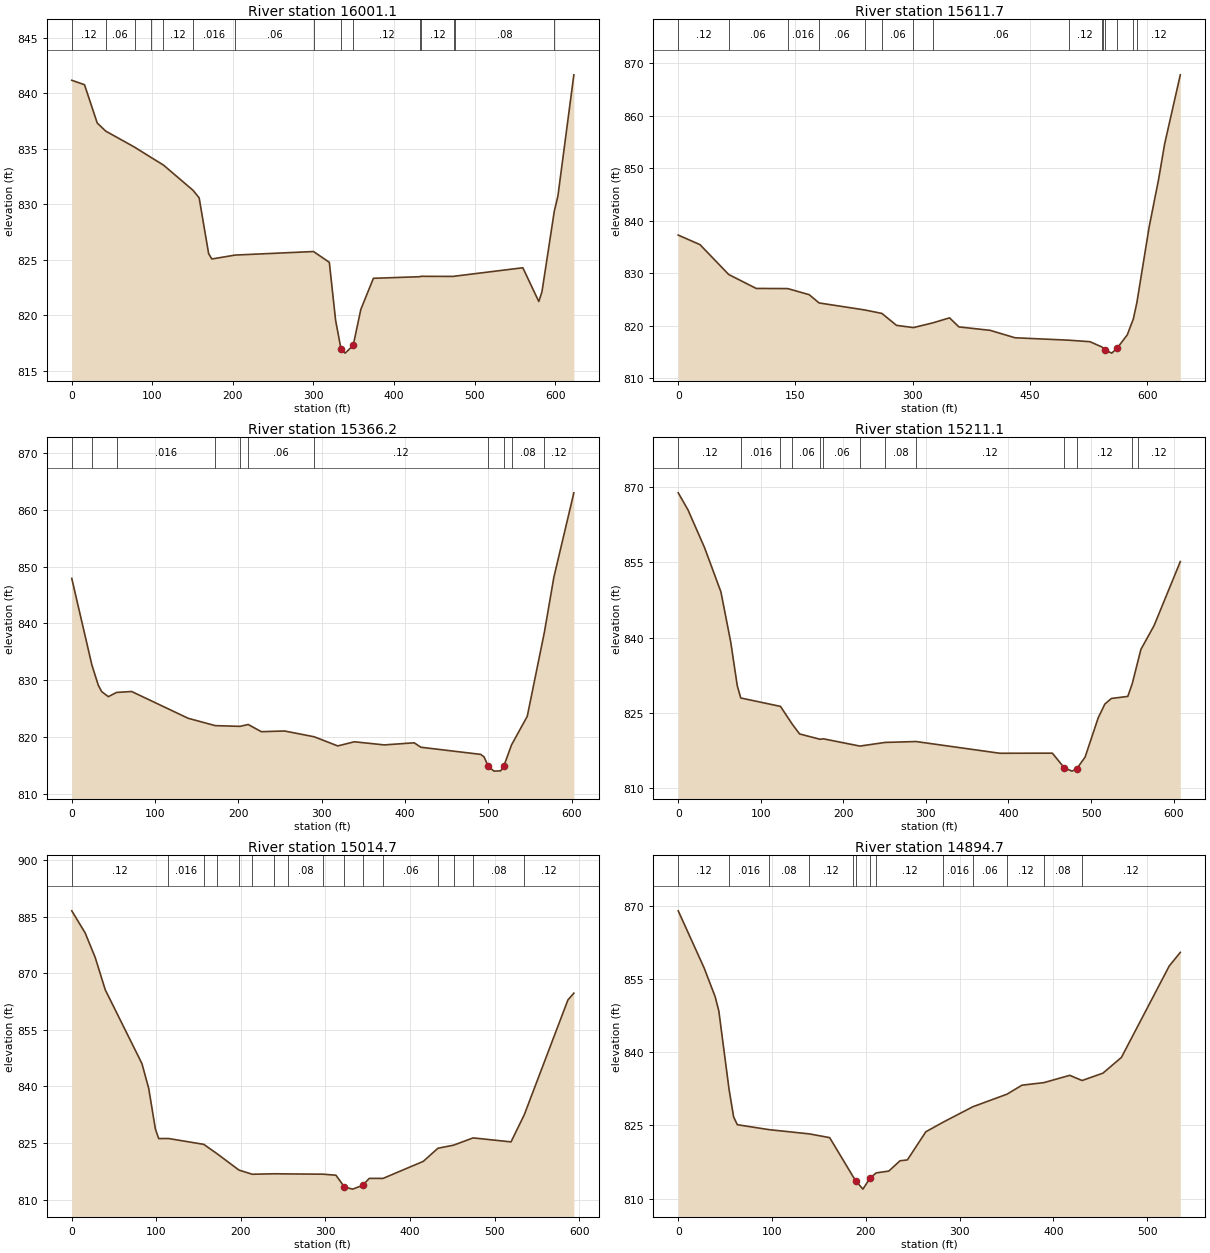
Type RM Length L Ch R = 1 ,16001.1 ,379.3,389.4,399.2
XS GIS Cut Line= 4
     1766375.235      403797.976     1766613.082      403634.781
     1766666.901      403513.253     1766811.307      403372.206
#Sta/Elev= 30
       0  841.16    15.8  840.76    31.6  837.31   42.12836.5814   77.94835.1363
    98.4 834.208  113.76833.5252   150.6831.2436   158.1  830.57   169.9  825.54
   173.9  825.06  202.81 825.413  300.06825.7325   319.7  824.76   327.5  819.53
   334.3  816.92   339.3  816.58   349.3  817.27   358.8  820.52   374.4  823.32
  431.72823.4634  433.78823.4987  473.99823.4908  475.07823.5097   559.9  824.27
   579.7  821.23   583.6  822.09  598.93829.3647   603.4  830.72   623.2  841.65
#Mann= 15 ,-1 , 0
       0     .12       0   42.12     .06       0   77.94     .12       0
    98.4     .06       0  113.76     .12       0   150.6    .016       0
  202.81     .06       0  300.06     .12       0   334.3    .045       0
   349.3     .12       0  431.72     .06       0  433.78     .12       0
  473.99     .06       0  475.07     .08       0  598.93     .12       0
Bank Sta=334.3,349.3
XS Rating Curve= 0 ,0
Exp/Cntr=0.3,0.1

Type RM Length L Ch R = 1 ,15611.7 ,245.5,245.5,245.2
XS GIS Cut Line= 2
      1766602.48      404022.432     1767074.386      403586.432
#Sta/Elev= 30
       0  837.26    27.9  835.43    64.6 829.738    99.8  827.08  140.02827.0536
   167.6  825.89  180.23824.3138   238.7 822.977  260.66822.3114   279.3  820.04
  300.87  819.61  325.75820.5103   347.2  821.47   359.2  819.74   399.1  819.09
     431  817.67  499.85817.2068   526.8  816.92  542.14 815.919  543.37 815.774
   546.4  815.34   554.7  814.74   561.4  815.64   574.6  818.22  582.35821.2419
   586.9 824.358   602.6  838.79   614.6   847.8   622.5  854.69   642.5  867.83
#Mann= 15 ,-1 , 0
       0     .12       0    64.6     .06       0  140.02    .016       0
  180.23     .06       0   238.7     .12       0  260.66     .06       0
  300.87     .12       0  325.75     .06       0  499.85     .12       0
  542.14     .08       0  543.37     .12       0   546.4    .045       0
   561.4     .12       0  582.35     .08       0   586.9     .12       0
Bank Sta=546.4,561.4
XS Rating Curve= 0 ,0
Exp/Cntr=0.3,0.1

Type RM Length L Ch R = 1 ,15366.2 ,154,155.1,156.5
XS GIS Cut Line= 2
     1766812.835      404142.299     1767263.356      403742.126
#Sta/Elev= 30
       0  847.94   24.14832.6982    31.9   829.1    35.9     828    43.9  827.11
   53.73827.8535    71.8  828.02   139.7   823.3  172.24822.0048  202.04821.8787
  211.75822.2062   227.5  820.94   255.4  821.06     291820.0407   319.2  818.43
   339.2  819.16   375.1  818.61     411  818.98     419   818.2   490.8  816.94
   494.8  816.51     500  814.81   506.8  813.99   514.8  814.04   518.8  814.97
  527.78818.5993   546.7  823.65  567.29838.5005   578.6  848.14   602.6  863.02
#Mann= 11 ,-1 , 0
       0     .12       0   24.14     .06       0   53.73    .016       0
  172.24     .06       0  202.04    .016       0  211.75     .06       0
     291     .12       0     500    .045       0   518.8     .12       0
  527.78     .08       0  567.29     .12       0
Bank Sta=500,518.8
XS Rating Curve= 0 ,0
Exp/Cntr=0.3,0.1

Type RM Length L Ch R = 1 ,15211.1 ,186.8,196.3,201.8
XS GIS Cut Line= 2
     1766891.503      404231.818     1767371.538      403858.554
#Sta/Elev= 30
       0  868.85    11.9  865.42    31.8  857.96    51.7  849.11    63.6   839.1
    71.5  830.42   75.72827.9657  123.84 826.292  138.31 822.698     147   820.8
  171.95819.7315  175.72819.8306  220.07818.3822  250.55819.1085  287.96819.2884
   389.5  816.95   453.1  816.97   467.5  814.07   476.9  813.39   482.5  813.82
   492.8  816.19   508.7  824.03   516.7  826.75   524.6  827.87   544.5  828.28
  549.86830.8013  556.89835.3873   560.4  837.66   576.3  842.38   608.1  855.15
#Mann= 13 ,-1 , 0
       0     .12       0   75.72    .016       0  123.84     .08       0
  138.31     .06       0  171.95     .08       0  175.72     .06       0
  220.07     .12       0  250.55     .08       0  287.96     .12       0
   467.5    .045       0   482.5     .12       0  549.86     .08       0
  556.89     .12       0
Bank Sta=467.5,482.5
XS Rating Curve= 0 ,0
Exp/Cntr=0.3,0.1

Type RM Length L Ch R = 1 ,15014.7 ,123,120,120.2
XS GIS Cut Line= 5
     1767027.245      404354.973     1767247.731      404133.619
     1767278.981      404130.147     1767448.252      403960.876
     1767456.261      403954.224
#Sta/Elev= 30
       0   886.6    15.8  880.76    27.7  874.24    39.6  865.65      83  846.06
      91  839.47    98.9   828.7   102.8  826.17  114.37826.1942  156.06 824.639
  171.63 822.188  197.74817.8082  213.48816.7051  239.44816.8329  255.33816.7966
  297.18816.7243   312.4  816.45   322.4  813.33   332.1  812.76   343.9  813.75
   351.8  815.61     368 815.599   415.7  820.13  432.91823.5977  451.54824.4282
  474.68826.3544   519.4  825.29  535.08832.4932   586.7  862.96   593.7  864.76
#Mann= 16 ,-1 , 0
       0     .12       0  114.37    .016       0  156.06     .06       0
  171.63     .08       0  197.74     .12       0  213.48     .08       0
  239.44     .12       0  255.33     .08       0  297.18     .12       0
   322.4    .045       0   343.9     .12       0     368     .06       0
  432.91     .12       0  451.54     .06       0  474.68     .08       0
  535.08     .12       0
Bank Sta=322.4,343.9
XS Rating Curve= 0 ,0
Exp/Cntr=0.3,0.1

Type RM Length L Ch R = 1 ,14894.7 ,170.8,158.6,146.8
XS GIS Cut Line= 4
     1767123.962      404370.343     1767229.502      404269.904
     1767403.981      404196.119     1767549.153       404057.98
#Sta/Elev= 30
       0     869    27.6   857.3    39.4  851.39    43.3  848.47   54.15832.4737
    59.1  826.74      63  825.15   96.99824.1312  139.84823.2653   161.5   822.5
  185.87814.7059   189.7  813.56     197  811.94   204.7  814.24  211.16815.2701
   224.6  815.64   236.5  817.75   244.4  817.93   264.1   823.7  282.08825.6189
  314.15828.8225  350.78831.4176   366.6  833.25  389.99833.7761   417.6  835.27
  430.76834.2072     453  835.72   472.7  838.95   523.7  857.69   535.5  860.48
#Mann= 13 ,-1 , 0
       0     .12       0   54.15    .016       0   96.99     .08       0
  139.84     .12       0  185.87     .06       0   189.7    .045       0
   204.7     .06       0  211.16     .12       0  282.08    .016       0
  314.15     .06       0  350.78     .12       0  389.99     .08       0
  430.76     .12       0
Bank Sta=189.7,204.7
XS Rating Curve= 0 ,0
Exp/Cntr=0.3,0.1

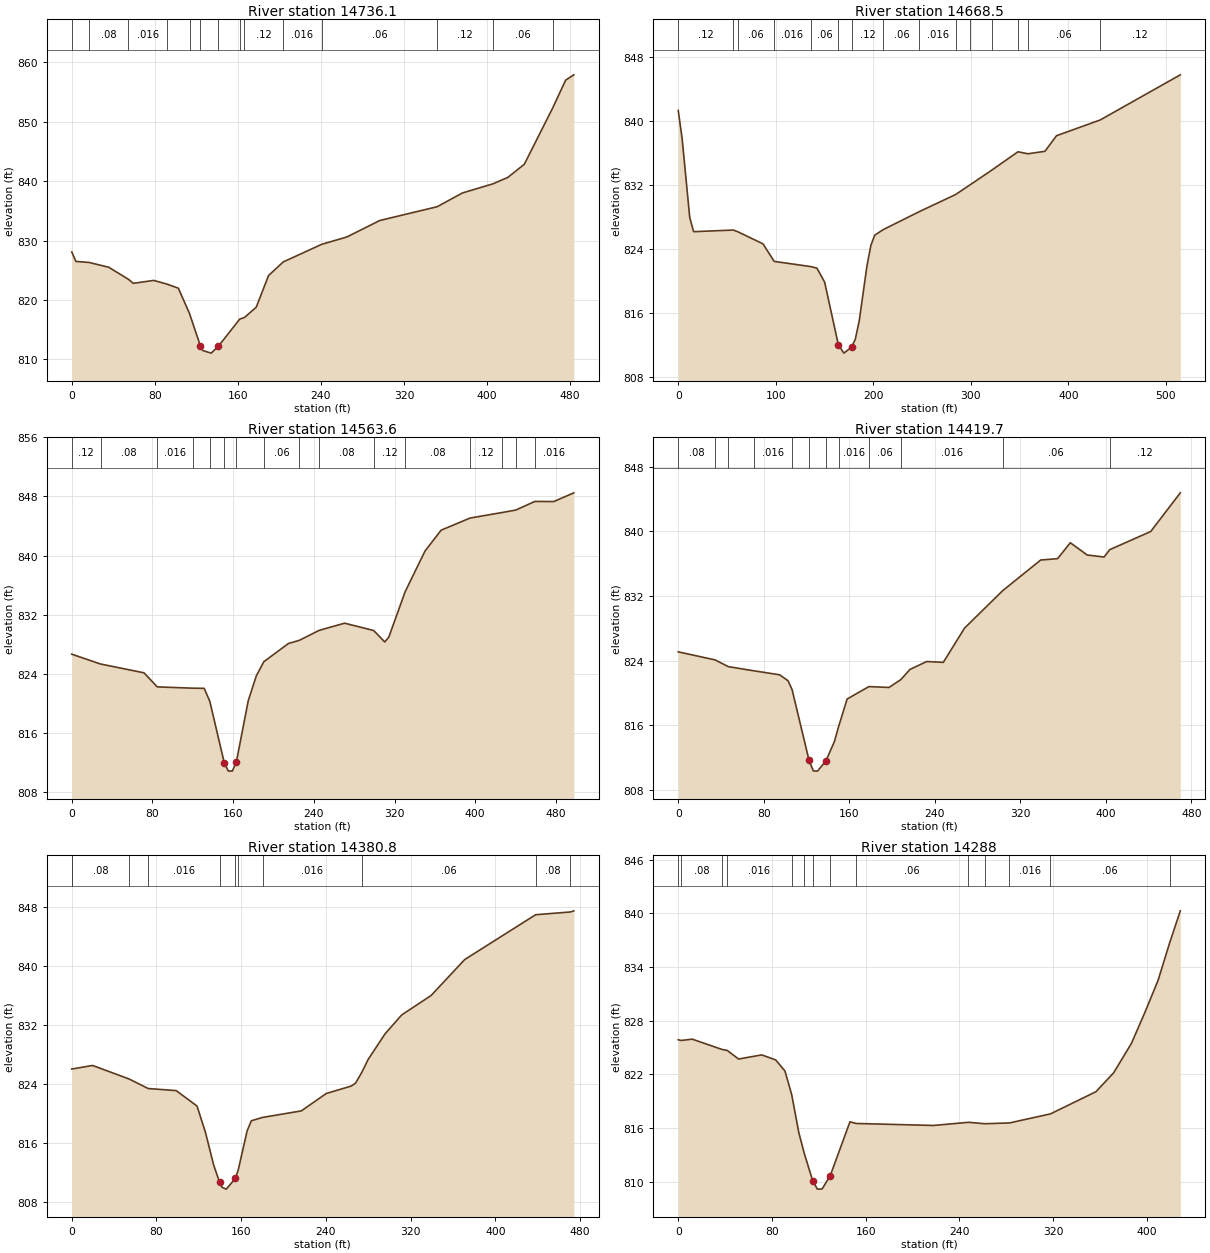
Type RM Length L Ch R = 1 ,14736.1 ,67.7,67.6,67.5
XS GIS Cut Line= 3
     1767285.926      404464.869     1767416.027      404295.863
     1767579.458      404080.408
#Sta/Elev= 30
       0  828.06       4  826.48   16.59826.3044    35.6   825.5   54.58823.4692
    59.2  822.79      79  823.28   91.85822.6501   102.7  821.97  113.43817.7122
   123.8  812.32   126.2  811.48   134.3  811.04   141.2  812.19  161.85816.7733
   166.4817.0392   177.7  818.77   189.6   824.1  203.68826.3866   240.8 829.358
     265  830.59   296.8  833.37  352.02835.6848   376.3     838  405.73839.5386
   420.1  840.62     436  842.84  463.23852.2762   475.8  856.99   483.7  857.89
#Mann= 14 ,-1 , 0
       0     .12       0   16.59     .08       0   54.58    .016       0
   91.85     .12       0  113.43    .016       0   123.8    .045       0
   141.2     .12       0  161.85    .016       0   166.4     .12       0
  203.68    .016       0   240.8     .06       0  352.02     .12       0
  405.73     .06       0  463.23     .12       0
Bank Sta=123.8,141.2
XS Rating Curve= 0 ,0
Exp/Cntr=0.3,0.1

Type RM Length L Ch R = 1 ,14668.5 ,106.7,104.8,103.1
XS GIS Cut Line= 3
     1767320.648      404529.105      1767450.75        404360.1
     1767632.903      404119.962
#Sta/Elev= 30
       0  841.31       4   837.8    11.8  827.94    15.8  826.18   56.51826.3842
    61.1826.1697    86.9  824.66   98.37822.4699  135.65821.8265   142.2  821.63
   150.1  819.88  164.16  812.05   169.8  811.02   177.7  811.76   181.5  812.74
   185.6  815.09   193.5  821.93   197.5  824.47   201.4  825.74  210.19826.4401
  247.28828.6922  284.36830.8181   299.4832.0461  321.43833.8607  348.27836.1536
   358.5 835.905   375.9  836.21   387.8  838.16  432.64840.1292   514.7  845.76
#Mann= 15 ,-1 , 0
       0     .12       0   56.51     .08       0    61.1     .06       0
   98.37    .016       0  135.65     .06       0  164.16    .045       0
   177.7     .12       0  210.19     .06       0  247.28    .016       0
  284.36     .06       0   299.4    .016       0  321.43     .06       0
  348.27    .016       0   358.5     .06       0  432.64     .12       0
Bank Sta=164.16,177.7
XS Rating Curve= 0 ,0
Exp/Cntr=0.3,0.1

Type RM Length L Ch R = 1 ,14563.6 ,143.2,143.9,144.6
XS GIS Cut Line= 3
      1767428.18       404581.28     1767603.875      404311.141
     1767673.273      404149.838
#Sta/Elev= 30
       0  826.67   28.52825.3402    71.6  824.15   84.76822.2485     120822.0731
   131.3  822.05  136.86   820.3   151.2  811.98   155.2  810.88   159.1  810.86
   163.1  812.04     175  820.39     183  823.75  190.46825.6553   214.8  828.11
   225.7828.5433   245.2829.8825   270.5  830.86  299.37829.8672   310.3  828.32
   314.3  828.96   330.6 835.131   350.2   840.6   366.2  843.43   394.9  845.07
  427.06845.8279  440.16846.1494  459.21 847.319   477.9   847.3   497.8  848.48
#Mann= 16 ,-1 , 0
       0     .12       0   28.52     .08       0   84.76    .016       0
     120     .08       0  136.86     .06       0   151.2    .045       0
   163.1     .12       0  190.46     .06       0   225.7     .12       0
   245.2     .08       0  299.37     .12       0   330.6     .08       0
   394.9     .12       0  427.06    .016       0  440.16     .12       0
  459.21    .016       0
Bank Sta=151.2,163.1
XS Rating Curve= 0 ,0
Exp/Cntr=0.3,0.1

Type RM Length L Ch R = 1 ,14419.7 ,38.9,38.9,39
XS GIS Cut Line= 4
     1767564.699      404627.173     1767666.262       404481.34
     1767656.491      404411.722     1767759.537      404215.455
#Sta/Elev= 30
       0  825.09   34.54824.0894   46.73 823.262   70.53822.7472    94.8  822.25
   102.7  821.52  106.52820.4132   122.4  811.64   126.4  810.35   130.3  810.32
   138.2   811.6   146.1  813.98   150.1  815.87     158  819.25  178.37820.7866
   197.2  820.68   208.2 821.648   216.8  822.91   232.4  823.89     248  823.79
   267.8  828.02  303.56  832.67   339.1  836.46   354.9  836.63   366.8   838.6
   382.6  837.08   398.4  836.83  403.64837.7398     442  839.99   469.7  844.78
#Mann= 12 ,-1 , 0
       0     .08       0   34.54     .12       0   46.73     .08       0
   70.53    .016       0  106.52     .12       0   122.4    .045       0
   138.2     .12       0   150.1    .016       0  178.37     .06       0
   208.2    .016       0  303.56     .06       0  403.64     .12       0
Bank Sta=122.4,138.2
XS Rating Curve= 0 ,0
Exp/Cntr=0.3,0.1

Type RM Length L Ch R = 1 ,14380.8 ,93.8,92.8,91.8
XS GIS Cut Line= 4
     1767589.962      404658.011     1767702.809      404496.336
     1767697.273      404437.655     1767792.523      404241.496
#Sta/Elev= 30
       0  826.02     .13826.0211    19.7   826.5   54.13824.6674   72.17 823.372
    98.6  823.09   118.3     821   126.2  817.46   134.1  812.96   139.6  810.67
     142  809.97   145.9  809.73   154.6  811.19  157.34812.4009   165.6  817.62
   169.6     819  180.23819.4542   216.8  820.34   240.4   822.7     264  823.71
     268   824.1  273.94825.5616   279.9  827.31   295.8  830.77   311.6  833.35
   339.4  835.99   371.1  840.86  438.11846.9417  470.94847.3152   474.2  847.47
#Mann= 11 ,-1 , 0
       0     .12       0     .13     .08       0   54.13     .06       0
   72.17    .016       0   139.6    .045       0   154.6    .016       0
  157.34     .12       0  180.23    .016       0  273.94     .06       0
  438.11     .08       0  470.94     .12       0
Bank Sta=139.6,154.6
XS Rating Curve= 0 ,0
Exp/Cntr=0.3,0.1

Type RM Length L Ch R = 1 ,14288   ,147.8,147.1,146.4
XS GIS Cut Line= 3
     1767687.095      404689.673     1767878.591      404388.914
     1767912.104      404325.118
#Sta/Elev= 30
       0  825.87    2.65825.7905    11.9  825.94   37.67824.7779   41.81824.6813
    51.5  823.72    71.3  824.18    83.2  823.62    91.1  822.38    96.8  819.78
     103  815.46   107.7813.1343   114.8  810.12   118.8  809.19   122.8   809.2
   129.8  810.71   146.6  816.71   151.8816.5235   217.9   816.3  247.75816.6523
  261.78816.4935  282.77816.5814  317.78817.5942   356.6  820.07   371.7  822.18
   386.9  825.47   398.3   828.9   409.6   832.5   419.7836.7756   428.6  840.27
#Mann= 14 ,-1 , 0
       0     .12       0    2.65     .08       0   37.67     .06       0
   41.81    .016       0    96.8     .06       0   107.7     .12       0
   114.8    .045       0   129.8     .12       0   151.8     .06       0
  247.75    .016       0  261.78     .06       0  282.77    .016       0
  317.78     .06       0   419.7     .12       0
Bank Sta=114.8,129.8
XS Rating Curve= 0 ,0
Exp/Cntr=0.3,0.1