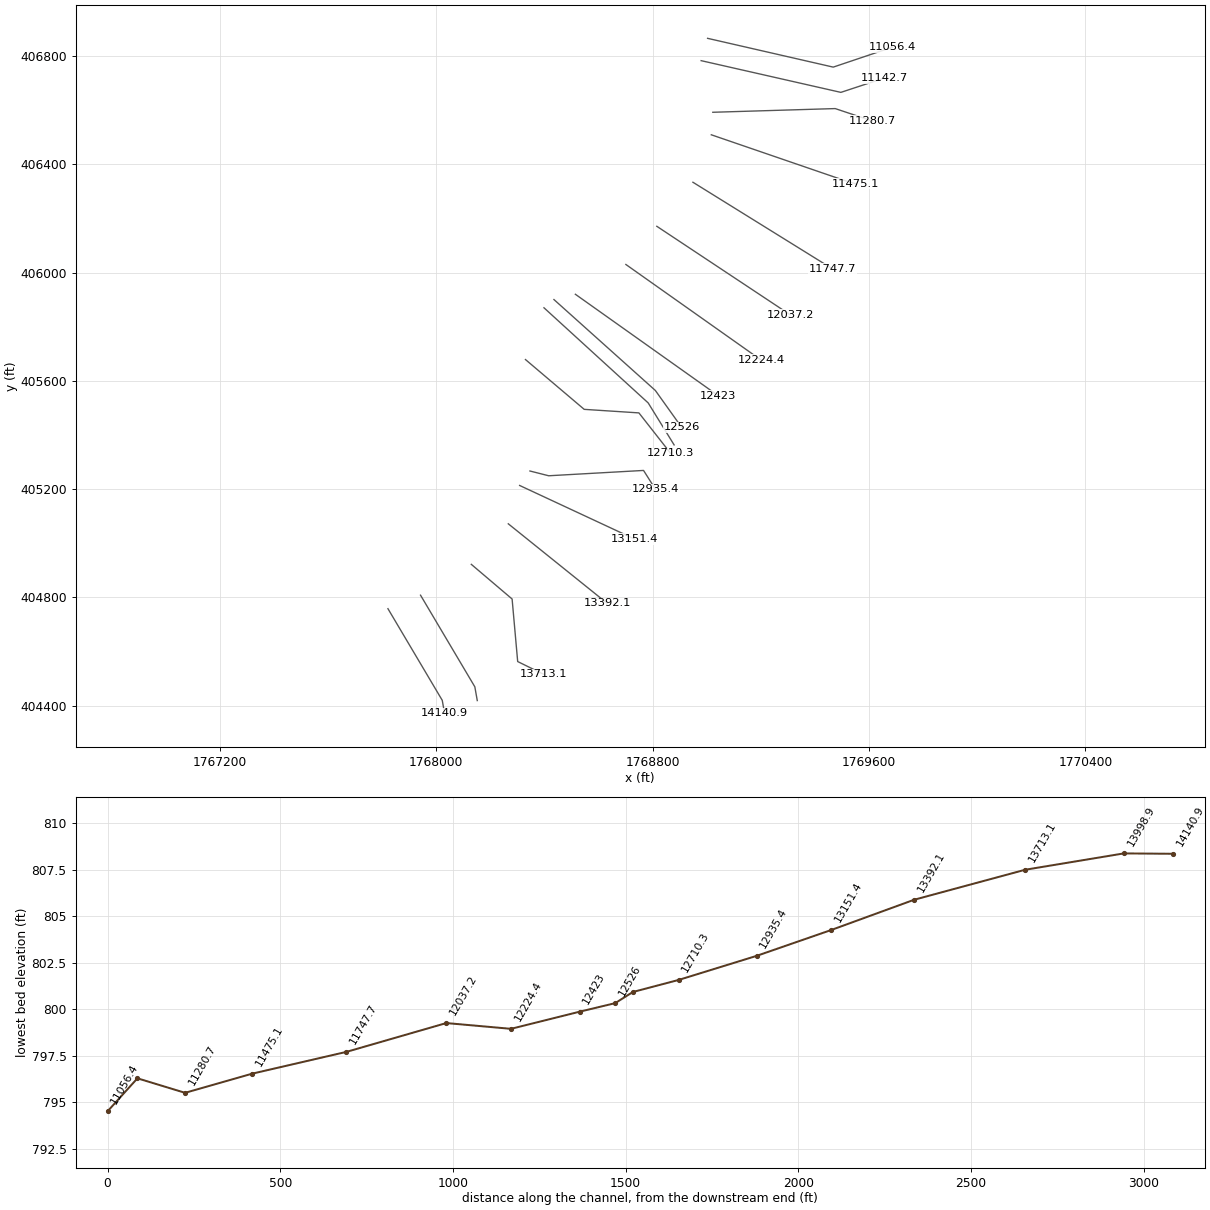
HEC-RAS study DRAWDYCK.prj: DRAWDYCK

--- DRAWDYCK.g01 (geometry) --- (continued)

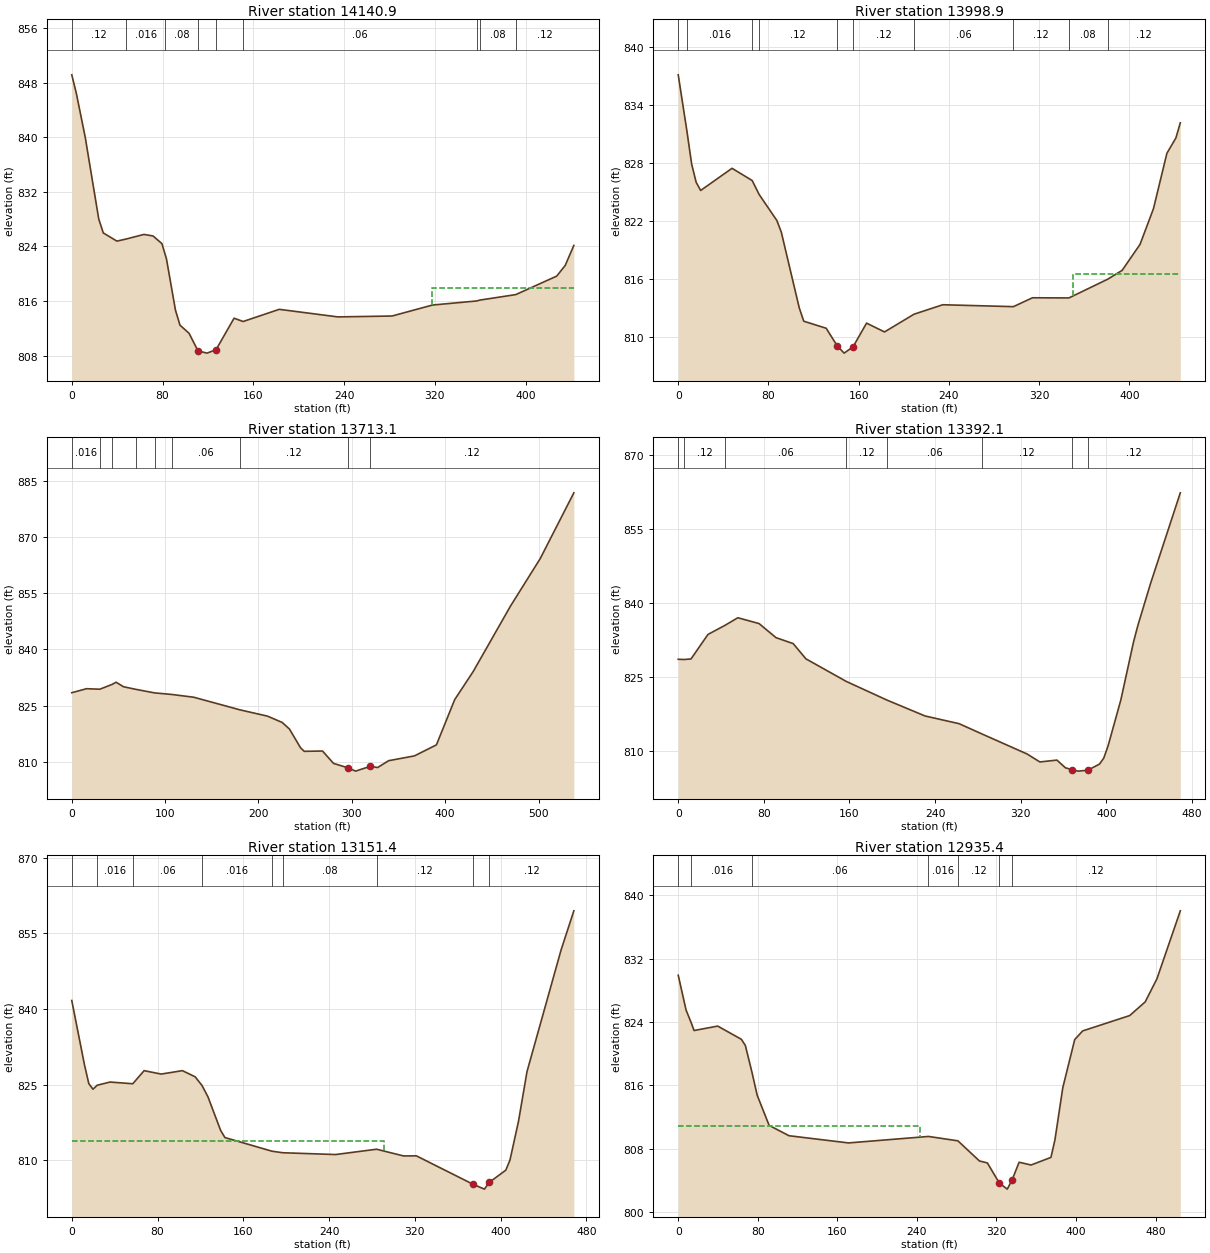
Type RM Length L Ch R = 1 ,14140.9 ,141.3,141.9,142.2
XS GIS Cut Line= 3
     1767821.496      404758.277     1768022.234      404419.735
     1768030.805      404371.525
#Sta/Elev= 30
       0  849.16       4  846.47    11.9  839.98    23.8  828.01    27.8  825.98
    39.8  824.78   48.02825.0908    63.6  825.76    71.6  825.54    79.5  824.41
   82.36822.8012    83.5  822.16    91.4  814.67    95.4  812.46   103.4  811.27
   111.3  808.68   119.3  808.36   127.2  808.87   143.1  813.48  151.04812.9942
   182.9  814.78   234.6  813.67   282.3   813.8     318  815.41  357.06816.0093
  359.61816.1314   391.4816.9405   427.5  819.65     435  821.22   442.6  824.15
#Mann= 9 ,-1 , 0
       0     .12       0   48.02    .016       0   82.36     .08       0
   111.3    .045       0   127.2     .12       0  151.04     .06       0
  357.06     .12       0  359.61     .08       0   391.4     .12       0
#XS Ineff= 2 , 0
                          317.72          817.86
Permanent Ineff=
       F       F
Bank Sta=111.3,127.2
XS Rating Curve= 0 ,0
Exp/Cntr=0.3,0.1

Type RM Length L Ch R = 1 ,13998.9 ,296.5,285.9,275.2
XS GIS Cut Line= 3
     1767941.939       404808.19     1768142.677      404469.648
     1768151.717      404418.797
#Sta/Elev= 30
       0  837.14    7.65831.3686    11.9  827.92    15.9  826.03    19.9  825.19
    47.7  827.48   65.56826.2174   71.71824.7823    87.5  822.08    91.4  820.88
   107.3  813.06   111.3  811.68   131.2  810.95  141.04  809.12   147.1  808.38
     155  809.03     167  811.48   182.9  810.57  209.07812.4022   234.6  813.38
  297.19813.1825   314.1   814.1  346.42814.0833  380.75 816.015   393.6  816.93
   409.5  819.62   421.4  823.31   433.3  829.03   441.3  830.62   445.2  832.18
#Mann= 10 ,-1 , 0
       0     .12       0    7.65    .016       0   65.56     .08       0
   71.71     .12       0  141.04    .045       0     155     .12       0
  209.07     .06       0  297.19     .12       0  346.42     .08       0
  380.75     .12       0
#XS Ineff= 2 , 0
                          349.81          816.56
Permanent Ineff=
       F       F
Bank Sta=141.04,155
XS Rating Curve= 0 ,0
Exp/Cntr=0.3,0.1

Type RM Length L Ch R = 1 ,13713.1 ,302.8,321,339.3
XS GIS Cut Line= 4
     1768129.656      404922.122     1768280.481      404794.084
     1768301.097      404562.964     1768398.012      404515.483
#Sta/Elev= 30
       0  828.41    15.8  829.48   30.08829.3483   43.17830.6262    47.5  831.21
    55.4  830.01   68.83829.3011   88.81828.3621  107.57 827.935   130.6  827.21
  180.09 823.849   209.6  822.17   225.4  820.48   233.2  818.72     245  813.75
     249  812.78   268.6  812.86   280.4  809.56   296.2  808.36     304   807.5
   319.8  808.79   327.6  808.45   339.4  810.28     367  811.56   390.6   814.5
   410.2  826.58   429.9  834.02   469.8  851.46   501.8  864.19   537.8  881.72
#Mann= 9 ,-1 , 0
       0    .016       0   30.08     .06       0   43.17     .12       0
   68.83     .06       0   88.81     .12       0  107.57     .06       0
  180.09     .12       0   296.2    .045       0   319.8     .12       0
Bank Sta=296.2,319.8
XS Rating Curve= 0 ,0
Exp/Cntr=0.3,0.1

Type RM Length L Ch R = 1 ,13392.1 ,235.3,240.7,246
XS GIS Cut Line= 2
     1768266.375      405071.862     1768632.085      404778.007
#Sta/Elev= 30
       0  828.56     5.6 828.518    11.9  828.62    27.8   833.6   43.48835.4142
    55.7  836.98    75.5   835.8    91.4  832.94   107.4  831.74   119.3  828.65
  157.15824.0572  195.04 820.289   230.6  817.07   262.4  815.51  283.67813.4353
     326  809.36   337.9  807.75   353.8  808.13   361.8  806.56   367.7  806.21
   373.7  805.89   382.7  806.07   393.6  807.32   397.6  808.54   401.6     811
   413.5  820.29   425.4  832.08   429.4  835.38   441.3  843.93   469.1   862.3
#Mann= 8 ,-1 , 0
       0    .016       0     5.6     .12       0   43.48     .06       0
  157.15     .12       0  195.04     .06       0  283.67     .12       0
   367.7    .045       0   382.7     .12       0
Bank Sta=367.7,382.7
XS Rating Curve= 0 ,0
Exp/Cntr=0.3,0.1

Type RM Length L Ch R = 1 ,13151.4 ,204.5,216,227.3
XS GIS Cut Line= 2
     1768308.278      405213.567     1768732.866      405015.794
#Sta/Elev= 30
       0  841.67    11.9  828.88    15.9  825.18    19.8  824.08   23.75  824.87
    35.7   825.5   56.91825.1611    67.5  827.76    83.4  827.08   103.2  827.76
   115.1  826.54   121.5  824.82     127   822.6   138.9   815.9   142.9  814.49
  186.67811.7883  196.82811.4762   246.1  811.12  284.41812.1752   309.6  810.84
   321.5  810.86   374.4  805.22     385  804.26   389.4  805.58   404.9  808.02
   408.8  810.01   416.8  817.75   424.7  827.57   456.5   851.7   468.4  859.46
#Mann= 9 ,-1 , 0
       0     .12       0   23.75    .016       0   56.91     .06       0
   121.5    .016       0  186.67     .12       0  196.82     .08       0
  284.41     .12       0   374.4    .045       0   389.4     .12       0
#XS Ineff= 2 , 0
           291.4  813.85
Permanent Ineff=
       F       F
Bank Sta=374.4,389.4
XS Rating Curve= 0 ,0
Exp/Cntr=0.3,0.1

Type RM Length L Ch R = 1 ,12935.4 ,227.9,225.1,222.4
XS GIS Cut Line= 4
     1768346.453      405266.957       1768415.7      405249.374
     1768766.351      405269.071     1768810.335      405199.599
#Sta/Elev= 30
       0  829.91     7.9   825.5    13.3823.8235    15.9  822.92    39.7  823.48
    63.5  821.81    67.5  821.03   74.17817.6287    79.4  814.74    91.4  810.93
   111.4  809.62   171.2  808.71  251.66809.5299  281.24 808.976   302.9  806.43
   310.9  806.18   322.9  803.64   330.9  802.87  335.78  804.05   342.8  806.27
   354.8  805.92   374.8  806.88   378.8  809.08   386.7  815.68   398.7  821.77
   406.7  822.87     454  824.81   469.6  826.54   481.4  829.46   504.9  838.05
#Mann= 7 ,-1 , 0
       0     .12       0    13.3    .016       0   74.17     .06       0
  251.66    .016       0  281.24     .12       0   322.9    .045       0
  335.78     .12       0
#XS Ineff= 2 , 0
          243.39  810.82
Permanent Ineff=
       F       F
Bank Sta=322.9,335.78
XS Rating Curve= 0 ,0
Exp/Cntr=0.3,0.1

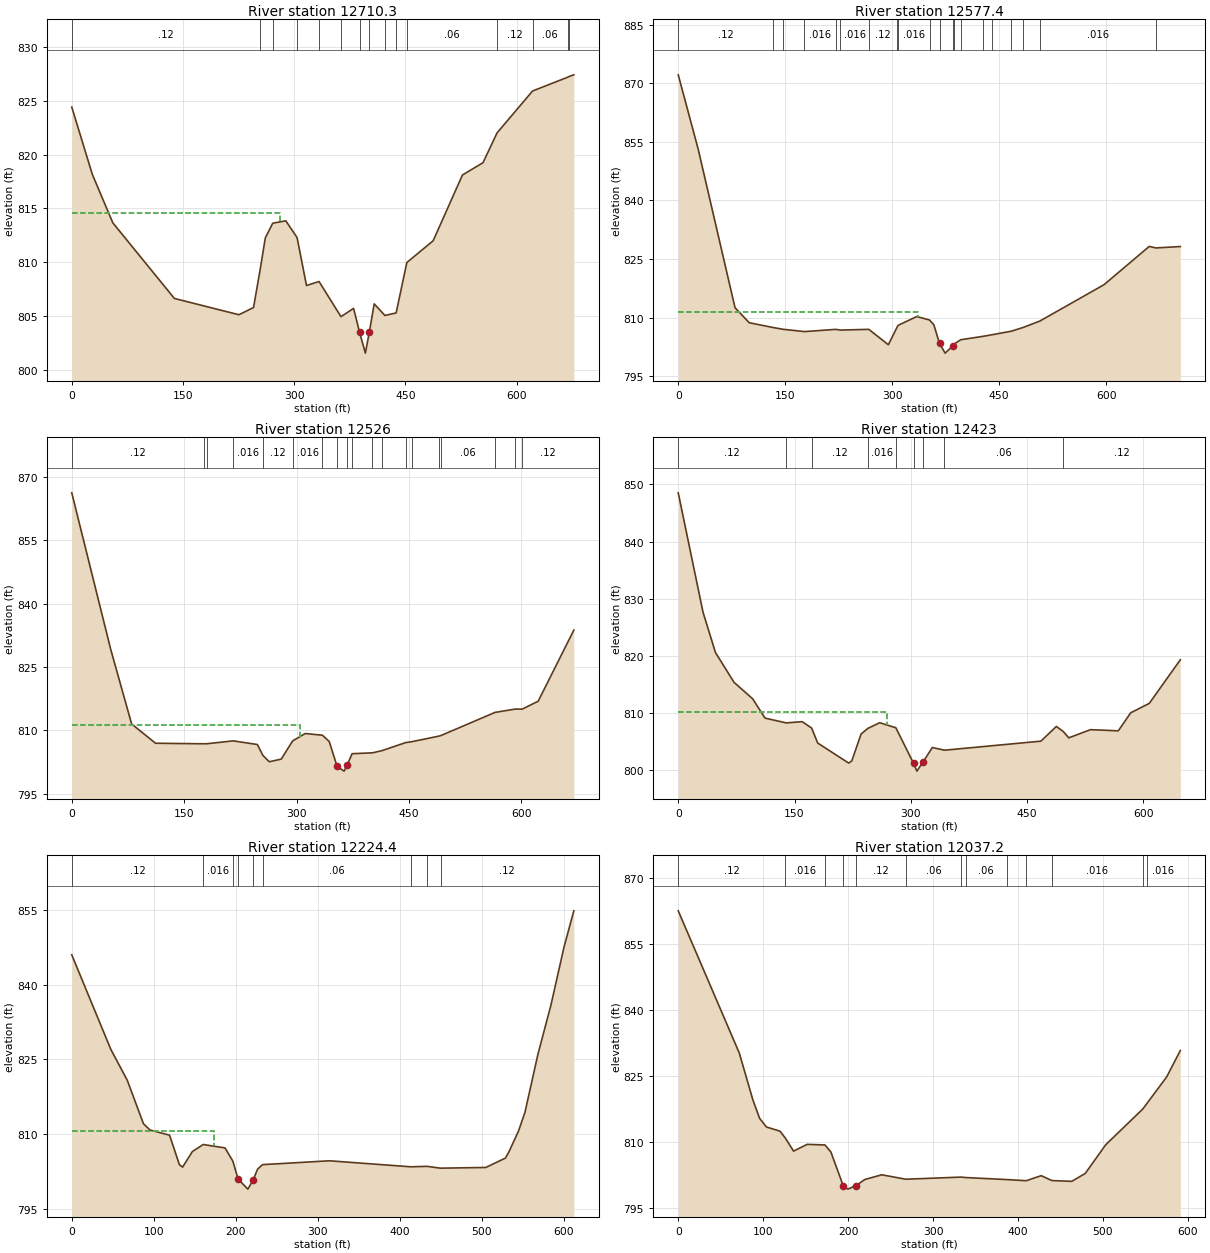
Type RM Length L Ch R = 1 ,12710.3 ,148.3,132.9,117.3
XS GIS Cut Line= 4
     1768329.801      405678.775     1768547.003      405494.746
     1768749.208      405481.669     1768866.326      405332.446
#Sta/Elev= 30
       0   824.4    27.7  818.16    55.4  813.66   138.4  806.65   225.4  805.14
   245.1  805.81  254.23809.4111     261  812.27     271813.6292   288.6  813.85
  303.82812.2963   316.5  807.85  333.41808.2207  363.01804.9615     380  805.73
     388  803.53   395.9  801.58   401.3  803.55   407.8  806.15  422.21805.0735
  437.39805.3083   451.8809.9841   487.3     812   526.8   818.1   554.5  819.24
  573.44822.0034  621.28825.8869  669.11827.1804  670.95827.2465     677  827.39
#Mann= 15 ,-1 , 0
       0     .12       0  254.23     .06       0     271    .016       0
  303.82     .08       0  333.41    .016       0  363.01     .12       0
     388    .045       0   401.3     .12       0  422.21     .06       0
  437.39     .12       0   451.8     .06       0  573.44     .12       0
  621.28     .06       0  669.11    .016       0  670.95     .06       0
#XS Ineff= 2 , 0
          281.26  814.62
Permanent Ineff=
       F       F
Bank Sta=388,401.3
XS Rating Curve= 0 ,0
Exp/Cntr=0.3,0.1

Type RM Length L Ch R = 1 ,12577.4 ,51.2,51.3,51.6
XS GIS Cut Line= 3
      1768398.25      405870.011     1768783.539      405518.471
      1768879.36      405363.371
#Sta/Elev= 30
       0  872.16    27.9  853.19    79.6  812.57    99.5  808.71  133.17 807.478
  147.26807.0214  176.99806.4439  220.82807.0109  227.22806.8312   267.2807.0149
   294.6  803.08  307.18 807.708  308.46808.0568   334.4  810.29  352.28809.4158
   358.3  808.22   366.3  803.42   374.2  800.93   384.7  802.74  387.15803.3052
   396.1804.3585  427.13805.2221  439.92805.6345  467.11806.5452  483.74807.5092
  507.09809.1467   596.9  818.44   660.3  828.24  669.81827.8534   703.9  828.21
#Mann= 20 ,-1 , 0
       0     .12       0  133.17    .016       0  147.26     .12       0
  176.99    .016       0  220.82     .12       0  227.22    .016       0
   267.2     .12       0  307.18     .08       0  308.46    .016       0
  352.28     .12       0   366.3    .045       0   384.7     .12       0
  387.15    .016       0   396.1     .06       0  427.13    .016       0
  439.92     .06       0  467.11    .016       0  483.74     .06       0
  507.09    .016       0  669.81    .016       0
#XS Ineff= 2 , 0
          336.84  811.43
Permanent Ineff=
       F       F
Bank Sta=366.3,384.7
XS Rating Curve= 0 ,0
Exp/Cntr=0.3,0.1

Type RM Length L Ch R = 1 ,12526   ,100.5,103,105.6
XS GIS Cut Line= 3
     1768435.142      405900.393     1768809.995      405564.483
     1768906.927      405428.778
#Sta/Elev= 30
       0   866.3    51.9  829.25    79.9  811.51   111.8  806.94  175.85806.8101
  180.03806.8177  215.51 807.501   247.7  806.64  255.17804.0364   263.6  802.55
   279.6  803.18  294.83807.5009   311.6  809.24  334.49808.8422   343.6  807.36
   354.1  801.47   363.5  800.33   367.5  801.77  374.15804.4583  401.32804.6682
  413.81 805.174  445.57 807.088  453.46807.2921  489.83808.6218  493.12808.7974
  564.86814.2478  591.88 815.037  601.15815.0273   622.5   816.9   670.1  833.76
#Mann= 19 ,-1 , 0
       0     .12       0  175.85     .08       0  180.03     .12       0
  215.51    .016       0  255.17     .12       0  294.83    .016       0
  334.49     .12       0   354.1    .045       0   367.5    .016       0
  374.15     .06       0  401.32    .016       0  413.81     .06       0
  445.57    .016       0  453.46     .06       0  489.83    .016       0
  493.12     .06       0  564.86     .12       0  591.88     .08       0
  601.15     .12       0
#XS Ineff= 2 , 0
          304.62  811.16
Permanent Ineff=
       F       F
Bank Sta=354.1,367.5
XS Rating Curve= 0 ,0
Exp/Cntr=0.3,0.1

Type RM Length L Ch R = 1 ,12423   ,198.5,198.6,198.6
XS GIS Cut Line= 2
     1768514.352      405919.925     1769042.613      405545.136
#Sta/Elev= 30
       0  848.54      32  827.65      48  820.62      72   815.4      96  812.52
     112  809.14   139.3 808.305   159.9  808.52   172.1 807.402   179.9  804.78
   219.9  801.28   223.9  801.66   235.9  806.36  244.52807.3344   259.9  808.34
  280.74 807.454   303.5  801.26   307.9  799.87   315.9  801.49   327.8     804
  343.48803.5296   467.8  805.11   487.8  807.68  496.61 806.818   503.8  805.69
   531.8  807.12   567.7  806.92   583.7  810.07   607.7  811.72   647.7  819.34
#Mann= 9 ,-1 , 0
       0     .12       0   139.3    .016       0   172.1     .12       0
  244.52    .016       0  280.74     .12       0   303.5    .045       0
   315.9     .12       0  343.48     .06       0  496.61     .12       0
#XS Ineff= 2 , 0
          268.68  810.28
Permanent Ineff=
       F       F
Bank Sta=303.5,315.9
XS Rating Curve= 0 ,0
Exp/Cntr=0.3,0.1

Type RM Length L Ch R = 1 ,12224.4 ,186.6,187.3,187.9
XS GIS Cut Line= 2
     1768701.054      406029.978     1769200.956      405676.855
#Sta/Elev= 30
       0  845.99    47.7  826.98    67.6  820.83    87.4  812.08    95.4  810.82
   119.2  809.78   131.2  803.86   135.1  803.37     147  806.49  160.23  807.91
   186.8  807.23  196.39804.5632   202.7  800.99   214.6  798.95     221  800.76
   226.5  802.96  232.55803.8681     314  804.64  413.36803.4318  432.85803.5283
  449.52803.1589   504.7   803.3   528.6  805.18   532.6  806.34   544.5   810.6
   552.4  814.35   568.3  826.08   584.2  835.98   600.1  847.61     612  854.83
#Mann= 9 ,-1 , 0
       0     .12       0  160.23    .016       0  196.39     .12       0
   202.7    .045       0     221     .12       0  232.55     .06       0
  413.36     .12       0  432.85     .06       0  449.52     .12       0
#XS Ineff= 2 , 0
          173.43  810.71
Permanent Ineff=
       F       F
Bank Sta=202.7,221
XS Rating Curve= 0 ,0
Exp/Cntr=0.3,0.1

Type RM Length L Ch R = 1 ,12037.2 ,289,289.4,289.7
XS GIS Cut Line= 2
      1768815.42      406171.037     1769308.041      405844.431
#Sta/Elev= 30
       0  862.54    71.9   830.2    87.9  819.54    95.8  815.36   103.8  813.39
   119.8  812.44  126.12810.8606   135.8   807.9   151.8  809.44  172.71809.2989
   179.7  807.71   194.4  799.96   199.7  799.26   209.4  800.06   219.6  801.44
   239.6  802.52  267.87801.5134  333.06801.9966  338.74801.8871  386.51801.4378
  409.62801.1699   427.3  802.32  439.96801.2084   463.3  801.03   479.2  802.83
   503.2  809.33  546.87 817.466  551.37818.6263   575.1  824.79   591.1  830.78
#Mann= 13 ,-1 , 0
       0     .12       0  126.12    .016       0  172.71     .12       0
   194.4    .045       0   209.4     .12       0  267.87     .06       0
  333.06    .016       0  338.74     .06       0  386.51    .016       0
  409.62     .12       0  439.96    .016       0  546.87     .12       0
  551.37    .016       0
Bank Sta=194.4,209.4
XS Rating Curve= 0 ,0
Exp/Cntr=0.3,0.1

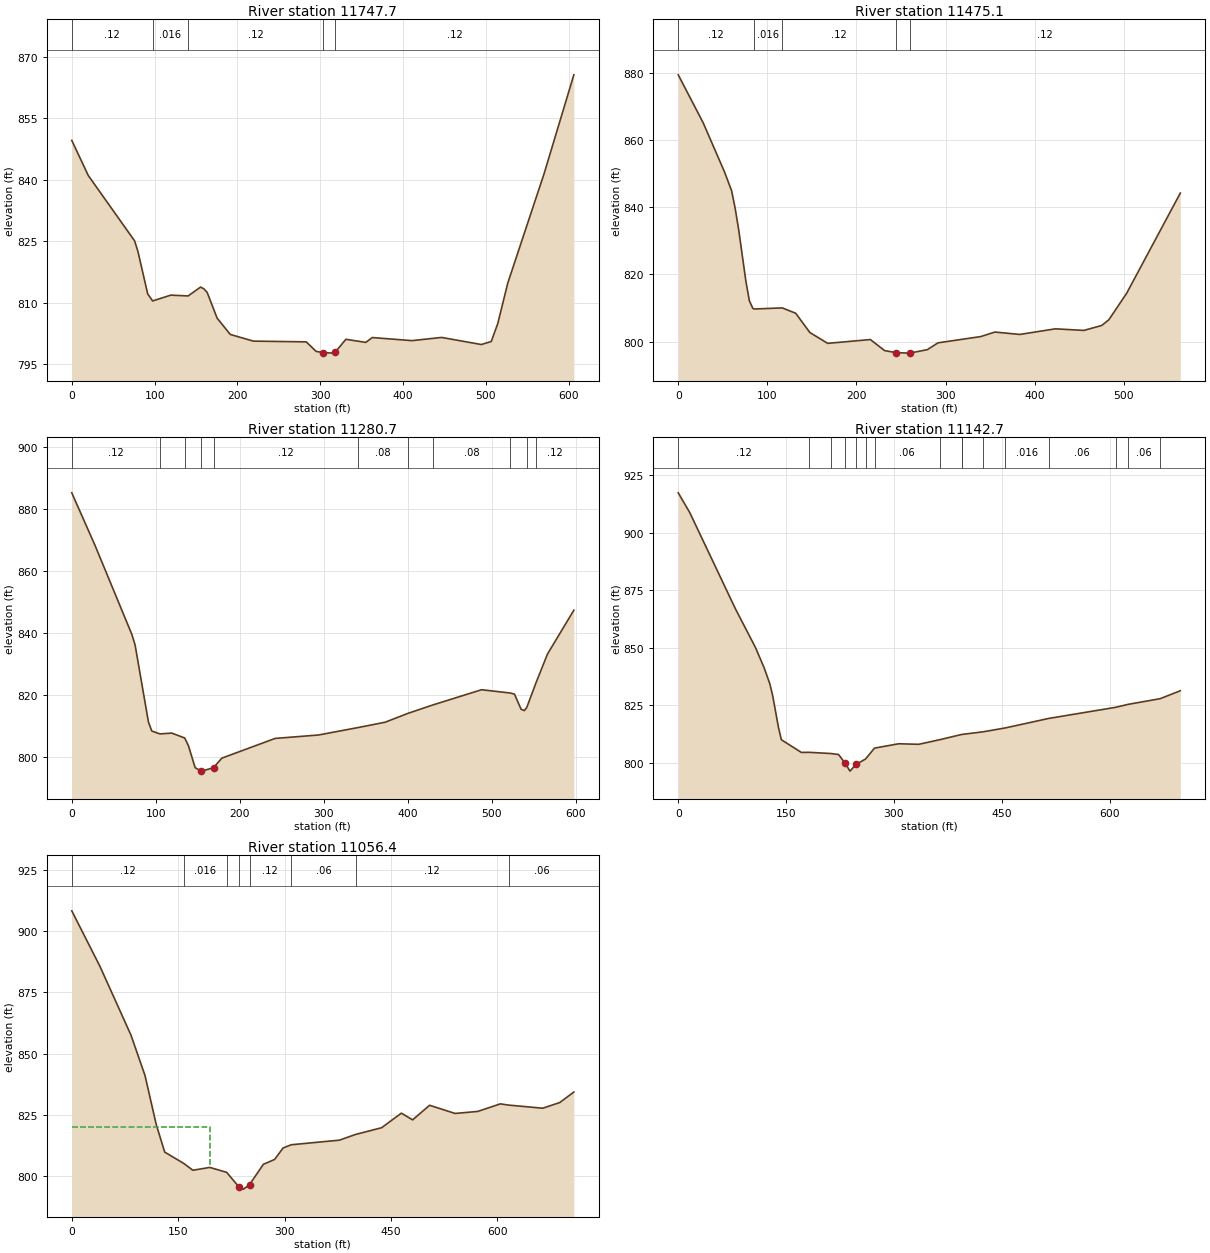
Type RM Length L Ch R = 1 ,11747.7 ,267.7,272.6,277.5
XS GIS Cut Line= 2
     1768948.883      406333.797     1769464.018       406014.31
#Sta/Elev= 30
       0  849.65    19.9  841.08    75.8  825.14    79.8   822.6    91.7  812.16
   97.61810.4474   119.6  811.87  140.42811.6667   155.5  813.83   159.5  813.41
   163.5  812.52   175.5  806.25   191.4  802.27   219.3  800.64   283.1  800.46
   295.1  798.13   303.3  797.86     315  797.71   318.3  798.01     331  801.09
   354.9  800.33   362.9  801.51   410.8  800.76   446.6  801.54   494.5  799.81
   506.5  800.55   514.4  804.97   526.4  814.79   570.3  841.53   606.2  865.65
#Mann= 5 ,-1 , 0
       0     .12       0   97.61    .016       0  140.42     .12       0
   303.3    .045       0   318.3     .12       0
Bank Sta=303.3,318.3
XS Rating Curve= 0 ,0
Exp/Cntr=0.3,0.1

Type RM Length L Ch R = 1 ,11475.1 ,186.4,194.4,202.2
XS GIS Cut Line= 3
     1769016.828       406509.14     1769504.025      406342.039
     1769550.396      406328.226
#Sta/Elev= 30
       0  879.36      28  865.08    51.9  850.48    59.9  844.86    63.9  839.61
    67.9  833.14    75.9  817.98    79.8  812.13    83.8  809.82   85.55809.6713
  116.78809.9973   131.8  808.41   147.7  802.68   167.7  799.45   215.6  800.58
   231.6  797.29   244.6  796.68   259.5  796.54   259.6  796.54   279.5  797.57
   291.5   799.6   339.4  801.46   355.4  802.81   383.3   802.1   423.2  803.77
   455.2   803.3   475.1  804.76   483.1  806.43   503.1  814.31   563.4  844.17
#Mann= 5 ,-1 , 0
       0     .12       0   85.55    .016       0  116.78     .12       0
   244.6    .045       0   259.6     .12       0
Bank Sta=244.6,259.6
XS Rating Curve= 0 ,0
Exp/Cntr=0.3,0.1

Type RM Length L Ch R = 1 ,11280.7 ,144,138,132
XS GIS Cut Line= 3
     1769022.372      406592.315     1769474.806      406605.961
     1769612.557      406559.925
#Sta/Elev= 30
       0  885.19    27.8  868.19    71.5   839.6    75.4  836.19    91.3  811.36
    95.3  808.43  104.97807.5076   119.1  807.76  134.52806.1852     139  803.65
   146.9  796.63   153.8  795.56   154.8  795.51   168.8  796.62   178.7  799.69
   242.2  806.05   293.8  807.15  341.36 809.572   373.2  811.27  400.46814.1387
  430.01816.8331     488  821.74  522.22820.6809   527.2  820.32   535.1  815.44
     539  815.03  541.79815.9958  553.36824.3399   566.5  833.23   597.9  847.37
#Mann= 11 ,-1 , 0
       0     .12       0  104.97    .016       0  134.52     .12       0
   153.8    .045       0   168.8     .12       0  341.36     .08       0
  400.46    .016       0  430.01     .08       0  522.22     .12       0
  541.79     .08       0  553.36     .12       0
Bank Sta=153.8,168.8
XS Rating Curve= 0 ,0
Exp/Cntr=0.3,0.1

Type RM Length L Ch R = 1 ,11142.7 ,86.3,86.3,85.9
XS GIS Cut Line= 3
     1768979.265      406783.016     1769495.758      406665.829
     1769655.811      406718.593
#Sta/Elev= 30
       0  917.44    15.9  908.92    79.6  866.91   107.5  850.04   119.5  841.24
   127.4  834.28   131.4  829.04   139.4   815.3   143.4  809.96   171.2  804.43
  182.08804.4736  212.36803.9532     223  803.51   232.1  799.72   238.9  796.29
   247.1  799.19  260.45801.5624  272.94806.3035   306.6   808.2   334.5  807.97
   363.8809.9775  393.94812.2305  394.08 812.241  424.37813.4279  454.65815.0833
  515.23819.2288  608.14824.0604   625.5825.3477  670.34827.8375   698.2  831.29
#Mann= 16 ,-1 , 0
       0     .12       0  182.08    .016       0  212.36     .08       0
   232.1    .045       0   247.1     .08       0  260.45     .12       0
  272.94     .06       0   363.8     .08       0  393.94     .06       0
  394.08     .12       0  424.37     .08       0  454.65    .016       0
  515.23     .06       0  608.14     .12       0   625.5     .06       0
  670.34     .12       0
Bank Sta=232.1,247.1
XS Rating Curve= 0 ,0
Exp/Cntr=0.3,0.1

Type RM Length L Ch R = 1 ,11056.4 ,185.3,186.5,187.3
XS GIS Cut Line= 3
     1769003.137      406865.482     1769467.547      406759.145
     1769686.673      406832.879
#Sta/Elev= 30
       0  908.41    39.7   885.7    83.4  857.58   103.2  841.04   119.1   820.9
     131  809.67  157.67805.0703   170.7  802.24   194.5  803.41  218.27801.3992
   235.5  795.47   242.2  794.52   250.5  796.36     270  804.67   285.9  806.67
   297.8  811.35  309.17812.6707   377.2  814.56  400.07816.9019   436.7  819.65
   464.5  825.61   480.4  822.87   504.3  828.84   540.2  825.49   572.1  826.31
     604  829.41  616.04828.8989   663.8  827.63   687.7  829.95   707.6  834.25
#Mann= 8 ,-1 , 0
       0     .12       0  157.67    .016       0  218.27     .12       0
   235.5    .045       0   250.5     .12       0  309.17     .06       0
  400.07     .12       0  616.04     .06       0
#XS Ineff= 2 , 0
       0   194.5     820               0
Permanent Ineff=
       F       F
Bank Sta=235.5,250.5
XS Rating Curve= 0 ,0
Exp/Cntr=0.3,0.1