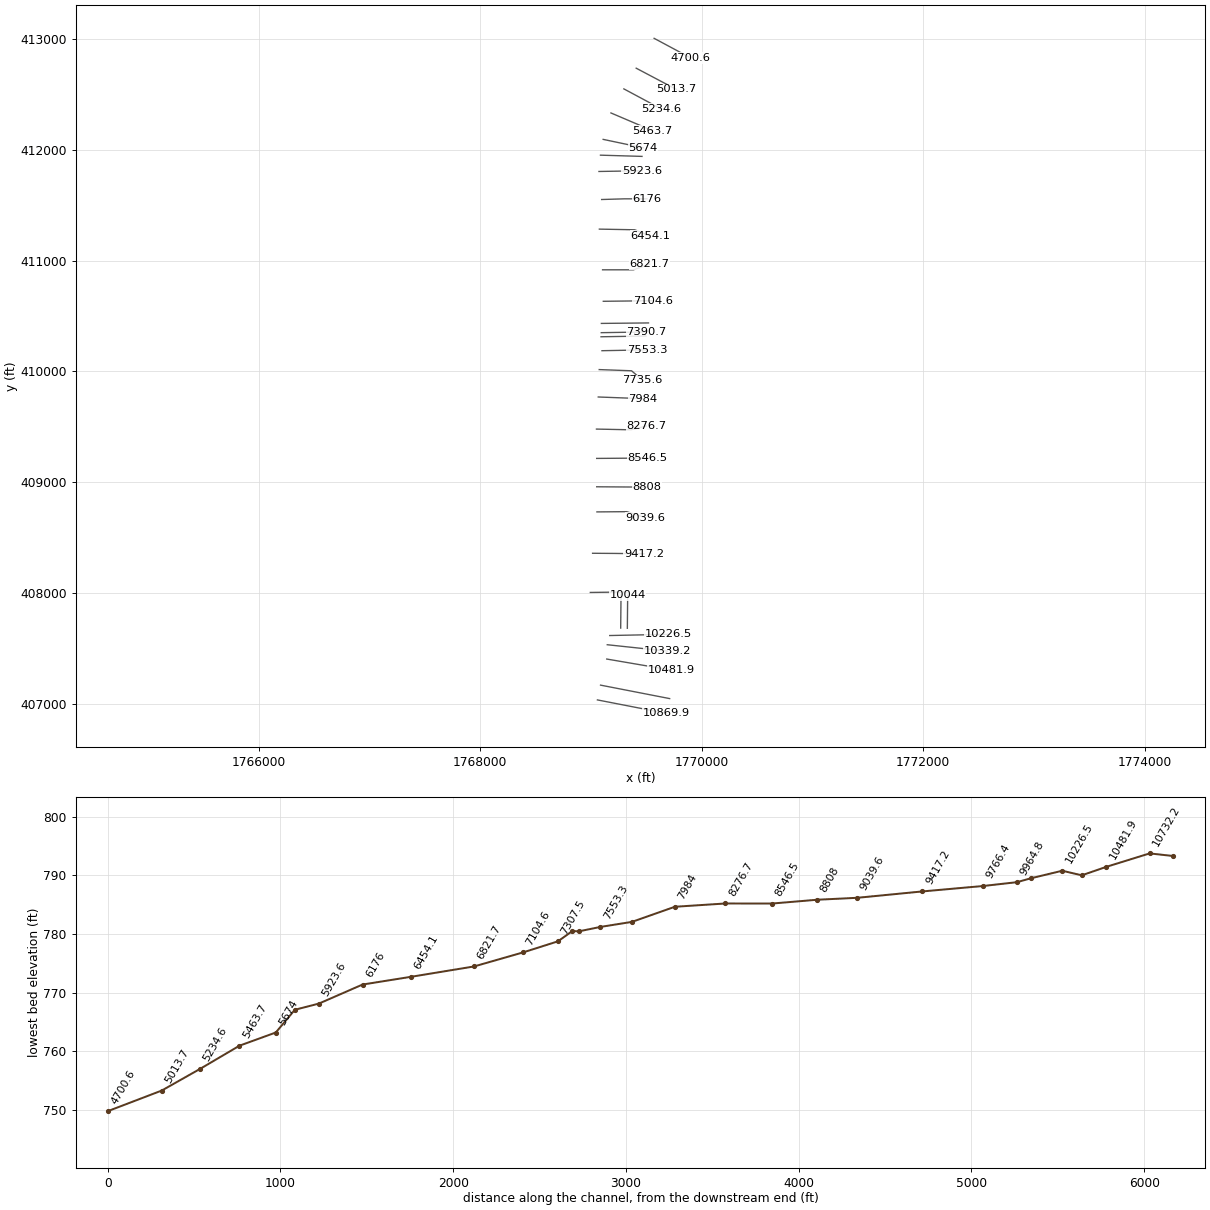
HEC-RAS study DRAWDYCK.prj: DRAWDYCK

--- DRAWDYCK.g01 (geometry) --- (continued)

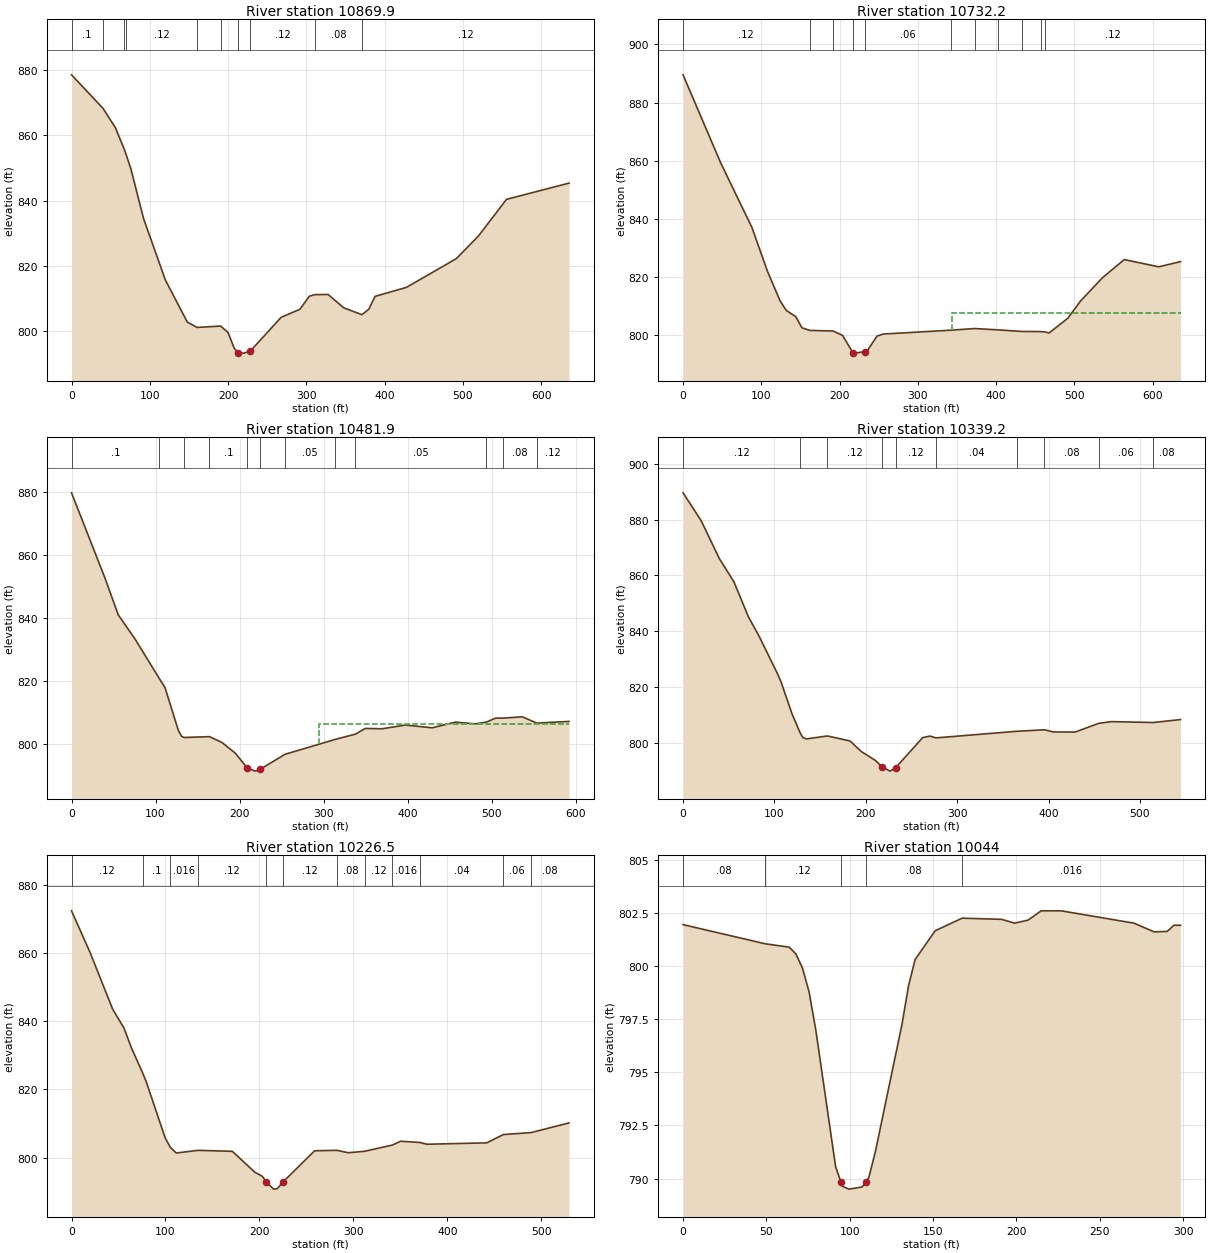
Type RM Length L Ch R = 1 ,10869.9 ,137.4,137.7,137.5
XS GIS Cut Line= 2
     1769058.475      407033.667      1769682.39      406912.139
#Sta/Elev= 30
       0  878.48   40.02868.2725      56  862.32   67.58855.5703   70.12 853.806
      76  849.56      92  834.49   119.9  815.68   147.9   802.8  160.39801.1657
  190.48801.5865   199.9  799.62   207.9  794.78   213.2  793.37   219.9   793.3
   228.2  793.86   267.8  804.26   291.8  806.72   303.8  810.72  310.84 811.196
   327.8  811.25   347.8  807.17  371.02805.0634   379.8  806.74   387.8  810.67
   427.8  813.42   491.7  822.23   519.7   829.1   555.7  840.36   635.6  845.34
#Mann= 10 ,-1 , 0
       0      .1       0   40.02     .12       0   67.58      .1       0
   70.12     .12       0  160.39    .016       0  190.48      .1       0
   213.2    .045       0   228.2     .12       0  310.84     .08       0
  371.02     .12       0
Bank Sta=213.2,228.2
XS Rating Curve= 0 ,0
Exp/Cntr=0.3,0.1

Type RM Length L Ch R = 1 ,10732.2 ,249.7,250.3,251
XS GIS Cut Line= 2
     1769086.687      407167.131     1769710.602      407045.603
#Sta/Elev= 30
       0  889.54      48  859.27      88     837   107.9  821.89   123.9  811.77
   131.9  808.43   143.9  806.35   151.9  802.48  161.74801.5714  191.83801.3559
   203.9  799.83   217.1  793.82   219.9  793.75   232.1  794.29   235.9  794.82
   247.9  799.63   255.9  800.32  342.28 801.642  372.37802.2143  402.46801.7535
  432.56801.2134   456.7801.1625  462.65801.0289   467.7   800.7   491.7  805.78
   507.7  811.64   535.7  819.66   563.7  825.95   607.7  823.46   635.6  825.25
#Mann= 11 ,-1 , 0
       0     .12       0  161.74    .016       0  191.83     .12       0
   217.1    .045       0   232.1     .06       0  342.28     .06       0
  372.37     .08       0  402.46     .12       0  432.56      .1       0
   456.7     .08       0  462.65     .12       0
#XS Ineff= 2 , 0
                          343.26           807.4
Permanent Ineff=
       F       F
Bank Sta=217.1,232.1
XS Rating Curve= 0 ,0
Exp/Cntr=0.3,0.1

Type RM Length L Ch R = 1 ,10481.9 ,141.2,142.7,144.1
XS GIS Cut Line= 2
     1769142.677      407402.591     1769726.444      407302.764
#Sta/Elev= 30
       0  879.84    39.8  852.77    55.6  841.09    75.5  833.46  104.26820.9592
   111.3  817.96   127.2  804.36   131.2  802.47  134.22802.1448  164.19802.4094
   178.9  800.59   194.8   797.2   209.1  792.51   218.6  791.46   224.1  791.98
  254.08796.7996  314.01801.5406  337.89803.2085   349.8  805.02   369.6  804.91
   397.5  806.09   429.3  805.22   457.1  807.02     481  806.47   493.8807.0385
   504.8  808.29  513.13808.2856   536.6  808.71  553.73 806.723   592.2  807.24
#Mann= 12 ,-1 , 0
       0      .1       0  104.26     .05       0  134.22    .016       0
  164.19      .1       0   209.1    .045       0   224.1      .1       0
  254.08     .05       0  314.01      .1       0  337.89     .05       0
   493.8     .06       0  513.13     .08       0  553.73     .12       0
#XS Ineff= 2 , 0
                          294.22           806.4
Permanent Ineff=
       F       F
Bank Sta=209.1,224.1
XS Rating Curve= 0 ,0
Exp/Cntr=0.3,0.1

Type RM Length L Ch R = 1 ,10339.2 ,109.8,112.6,115.5
XS GIS Cut Line= 2
     1769147.451      407531.714     1769688.901      407474.205
#Sta/Elev= 30
       0  889.57    19.9  879.55    39.7  866.05    55.6  857.78    71.5  845.24
    83.5  838.11   103.3  824.88   107.3  821.88   119.2  810.54  128.25803.6125
   131.2  801.99   135.1  801.54  157.95  802.59   182.8   800.8   194.8  797.08
   210.6  793.81   217.6  791.58   226.5  790.01   232.6  791.21   262.3     802
   270.3  802.55  276.76801.8984  365.86804.2759  395.56804.8018   405.4  804.02
   429.2  803.99  454.97807.1035     469  807.72  514.37807.3934   544.5  808.46
#Mann= 10 ,-1 , 0
       0     .12       0  128.25    .016       0  157.95     .12       0
   217.6    .045       0   232.6     .12       0  276.76     .04       0
  365.86    .016       0  395.56     .08       0  454.97     .06       0
  514.37     .08       0
Bank Sta=217.6,232.6
XS Rating Curve= 0 ,0
Exp/Cntr=0.3,0.1

Type RM Length L Ch R = 1 ,10226.5 ,145.5,182.5,218.8
XS GIS Cut Line= 2
     1769169.823      407614.825     1769699.337      407625.676
#Sta/Elev= 30
       0  872.35    19.9  860.04    43.8  843.52    55.8  838.02    63.7  832.23
   75.64824.8842    79.6  822.21    99.6  805.87  105.18 803.027   111.5  801.38
  134.72 802.157   171.2  801.87   195.1  795.76   203.1  794.54   207.1  793.02
     215  790.79     219  790.92   225.4  792.97   258.8  802.03  282.43802.1639
   294.7  801.46  311.98801.8793  341.52 803.703   350.4  804.83  371.06804.4564
   378.3  803.94     442  804.35  459.68806.7817  489.23807.3572   529.6  810.19
#Mann= 12 ,-1 , 0
       0     .12       0   75.64      .1       0  105.18    .016       0
  134.72     .12       0   207.1    .045       0   225.4     .12       0
  282.43     .08       0  311.98     .12       0  341.52    .016       0
  371.06     .04       0  459.68     .06       0  489.23     .08       0
Bank Sta=207.1,225.4
XS Rating Curve= 0 ,0
Exp/Cntr=0.3,0.1

Type RM Length L Ch R = 1 ,10044   ,68.2,79.2,81.6
XS GIS Cut Line= 2
     1769328.658      407680.369     1769331.626      407978.735
#Sta/Elev= 30
       0  801.95   49.24801.0493    63.6  800.89    67.6  800.58    71.6  799.91
    75.6  798.78    79.6     797    91.5  790.56    94.6  789.85    95.5  789.64
    99.5   789.5   107.4   789.6   109.6  789.84   111.4  790.04   115.4  791.28
   131.3  797.25   135.3  799.09   139.2  800.31   151.2  801.66  167.39802.2542
     191   802.2   198.9  802.02   206.9  802.16   214.8   802.6   226.8   802.6
   270.5  802.02   282.5  801.61   290.4  801.63   294.4  801.92   298.4  801.92
#Mann= 5 ,-1 , 0
       0     .08       0   49.24     .12       0    94.6    .045       0
   109.6     .08       0  167.39    .016       0
Bank Sta=94.6,109.6
XS Rating Curve= 0 ,0
Exp/Cntr=0.3,0.1

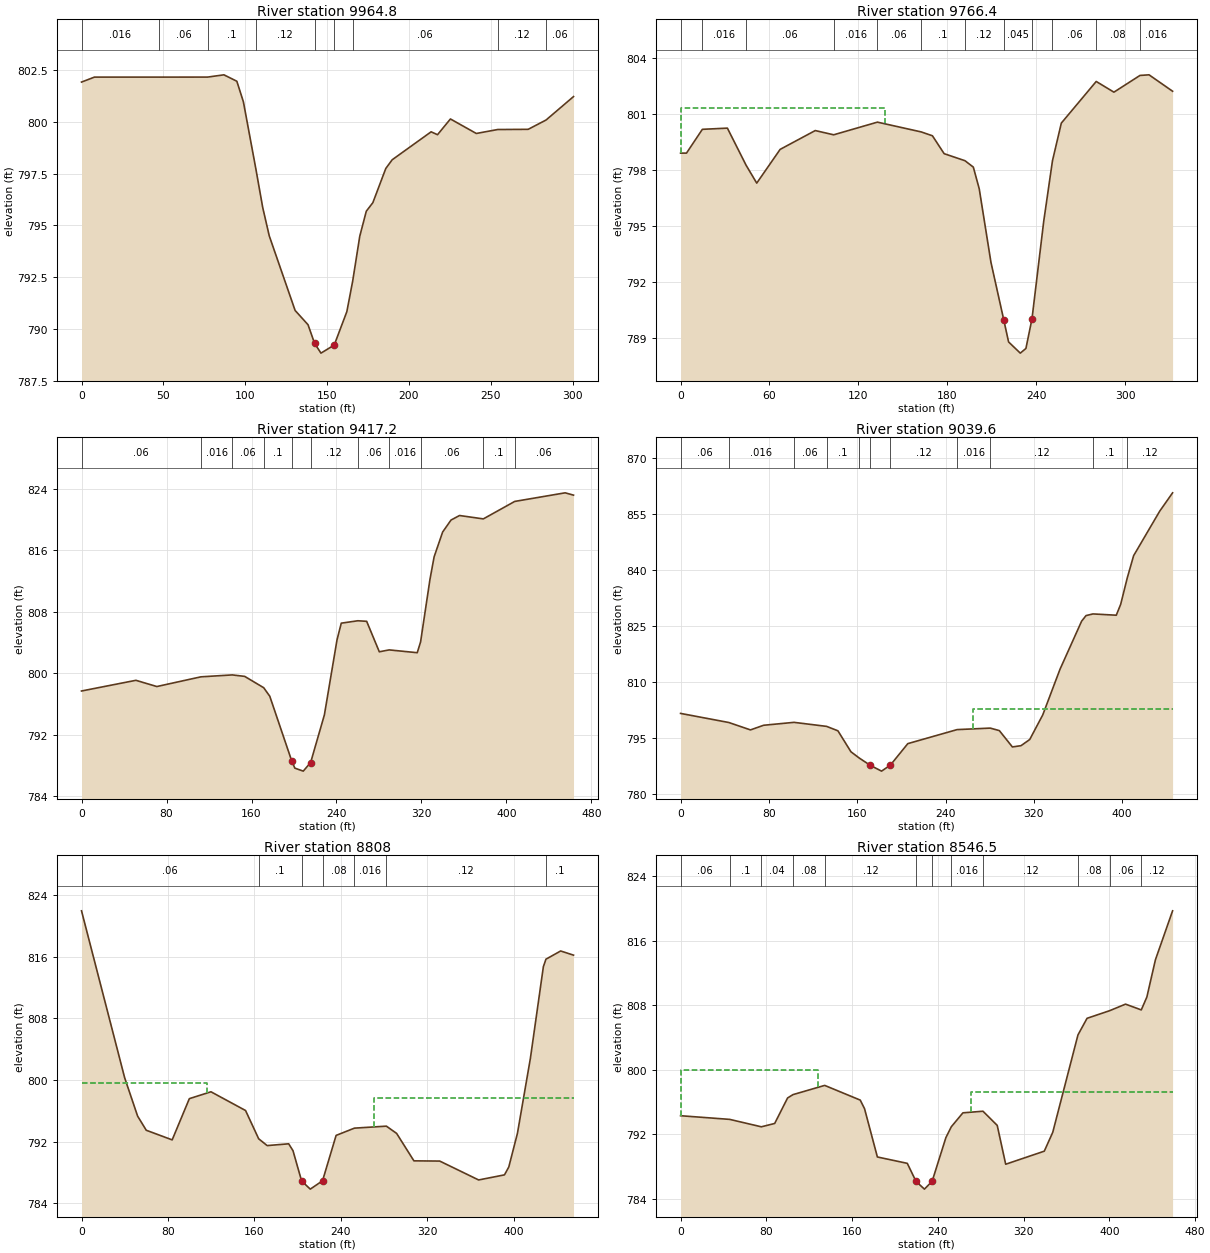
Type RM Length L Ch R = 1 ,9964.8  ,247.1,198.4,158.9
XS GIS Cut Line= 2
     1769268.565        407682.1      1769271.73      407982.642
#Sta/Elev= 30
       0  801.92     7.9  802.16   47.51802.1597   77.05 802.161      87  802.27
    94.9  801.96    98.9  800.97  106.58797.7062   110.7  795.87   114.7   794.5
   130.5   790.9   138.4  790.21   142.4  789.31   146.3  788.84   154.4  789.23
   162.1  790.84  165.66792.3085     170  794.48     174  795.69     178   796.1
   185.9  797.75   189.8  798.17   213.6  799.52   217.5  799.38   225.4  800.14
   241.2  799.44  254.27799.6304   272.9  799.64  283.81800.0884   300.6  801.22
#Mann= 9 ,-1 , 0
       0    .016       0   47.51     .06       0   77.05      .1       0
  106.58     .12       0   142.4    .045       0   154.4     .12       0
  165.66     .06       0  254.27     .12       0  283.81     .06       0
Bank Sta=142.4,154.4
XS Rating Curve= 0 ,0
Exp/Cntr=0.3,0.1

Type RM Length L Ch R = 1 ,9766.4  ,349.6,349.2,348.6
XS GIS Cut Line= 2
     1768994.456      408003.719     1769326.488       408008.06
#Sta/Elev= 30
       0  798.91       4  798.91   14.71800.1866    31.6  800.25   44.25798.2565
    51.4   797.3    67.2  799.11    90.9  800.12  103.32799.8926  132.86800.5716
   162.4800.0477     170  799.84   177.9  798.88  191.94798.5035   197.6  798.16
   201.6  796.99   209.5  793.05   218.1  789.98   221.4  788.78   229.3  788.18
   233.1  788.43   237.2  790.02   245.1  795.24  251.02798.4991     257  800.52
  280.55 802.754   292.5  802.18  310.09803.0771   316.2  803.11   332.1  802.23
#Mann= 12 ,-1 , 0
       0     .05       0   14.71    .016       0   44.25     .06       0
  103.32    .016       0  132.86     .06       0   162.4      .1       0
  191.94     .12       0   218.1    .045       0   237.2     .12       0
  251.02     .06       0  280.55     .08       0  310.09    .016       0
#XS Ineff= 2 , 0
          137.93  801.35
Permanent Ineff=
       F       F
Bank Sta=218.1,237.2
XS Rating Curve= 0 ,0
Exp/Cntr=0.3,0.1

Type RM Length L Ch R = 1 ,9417.2  ,377.2,377.6,377.9
XS GIS Cut Line= 3
     1769014.937      408357.298     1769219.682      408355.866
     1769478.026      408352.751
#Sta/Elev= 30
       0  797.68    51.2  799.07    70.9  798.26  112.38799.5218  141.91799.7711
   153.6  799.58  171.45798.1095   177.2     797   197.9  788.57   200.8  787.65
   208.7  787.26  215.66  788.38   228.6  794.57   240.5  804.34   244.5   806.5
  260.06806.8132   268.4  806.74   280.3  802.78   289.6 803.024     316  802.66
  319.14804.0573     328  812.21   331.9  815.13   339.9  818.35   347.8  819.91
   355.8   820.5  378.21  820.06  407.75822.3309   455.2  823.45   463.1  823.15
#Mann= 11 ,-1 , 0
       0     .06       0  112.38    .016       0  141.91     .06       0
  171.45      .1       0   197.9    .045       0  215.66     .12       0
  260.06     .06       0   289.6    .016       0  319.14     .06       0
  378.21      .1       0  407.75     .06       0
Bank Sta=197.9,215.66
XS Rating Curve= 0 ,0
Exp/Cntr=0.3,0.1

Type RM Length L Ch R = 1 ,9039.6  ,231.5,231.6,230.9
XS GIS Cut Line= 3
     1769054.135      408730.716     1769323.232      408732.886
     1769491.387      408679.182
#Sta/Elev= 30
       0   801.6   43.65799.1714    63.3  797.19    75.2  798.43  102.72799.2105
  132.26798.1321   142.5  796.95   154.3  791.34  161.79789.6752   171.7  787.74
     182  786.17     190  787.77   205.8  793.52   250.4797.2672  280.48797.6716
   288.7     797   300.5  792.64   308.3  792.97   316.2  794.62     328  801.19
   343.6  813.38   363.2  826.25   367.2  827.75   373.5828.1954   394.6  827.85
   398.6  830.77   404.5837.7641   410.3  843.76   433.9  855.65   445.6  860.57
#Mann= 11 ,-1 , 0
       0     .06       0   43.65    .016       0  102.72     .06       0
  132.26      .1       0  161.79     .12       0   171.7    .045       0
     190     .12       0   250.4    .016       0  280.48     .12       0
   373.5      .1       0   404.5     .12       0
#XS Ineff= 2 , 0
                          265.08          802.73
Permanent Ineff=
       F       F
Bank Sta=171.7,190
XS Rating Curve= 0 ,0
Exp/Cntr=0.3,0.1

Type RM Length L Ch R = 1 ,8808    ,261.2,261.5,261.1
XS GIS Cut Line= 2
     1769051.965      408957.495     1769507.284       408954.46
#Sta/Elev= 30
       0  821.95    39.9   800.3    51.9  795.32    59.9  793.48    83.9  792.23
    99.8  797.58   119.8  798.47   151.8  796.04  163.96792.3688   171.8  791.49
   191.7  791.72   195.7  790.83   203.7  786.89   211.7  785.84  223.04786.9234
   235.6  792.81  252.57793.7527  282.11 794.012   291.6  793.07   307.6  789.51
   331.5  789.48   367.5  787.03   391.4  787.69   395.4  788.71   403.4  793.08
   415.4  802.82   427.4   814.7  429.79 815.674   443.4  816.74   455.3   816.2
#Mann= 7 ,-1 , 0
       0     .06       0  163.96      .1       0   203.7    .045       0
  223.04     .08       0  252.57    .016       0  282.11     .12       0
  429.79      .1       0
#XS Ineff= 2 , 0
          116.17  799.64  270.22           797.6
Permanent Ineff=
       F       F
Bank Sta=203.7,223.04
XS Rating Curve= 0 ,0
Exp/Cntr=0.3,0.1

Type RM Length L Ch R = 1 ,8546.5  ,270.2,269.9,269.3
XS GIS Cut Line= 2
     1769051.965      409213.572     1769510.949      409216.827
#Sta/Elev= 30
       0   794.3   45.82 793.846   75.36792.9243    87.8  793.34    99.8   796.5
  104.89796.9199  134.43 798.063   167.6  796.24   171.6  795.18   183.6  789.18
   211.5  788.39   219.7  786.14   227.5  785.19   234.7  786.17   247.5  791.58
  252.58792.9307   263.4  794.66  282.11794.8584   295.4   793.1   303.3  788.28
   339.3   789.9   347.2  792.24  370.72804.3276   379.2  806.39  400.26807.3354
   415.1  808.15   429.8807.4327     435  809.03     443  813.66     459  819.73
#Mann= 12 ,-1 , 0
       0     .06       0   45.82      .1       0   75.36     .04       0
  104.89     .08       0  134.43     .12       0   219.7    .045       0
   234.7     .12       0  252.58    .016       0  282.11     .12       0
  370.72     .08       0  400.26     .06       0   429.8     .12       0
#XS Ineff= 2 , 0
          128.37  799.96  270.86          797.19
Permanent Ineff=
       F       F
Bank Sta=219.7,234.7
XS Rating Curve= 0 ,0
Exp/Cntr=0.3,0.1

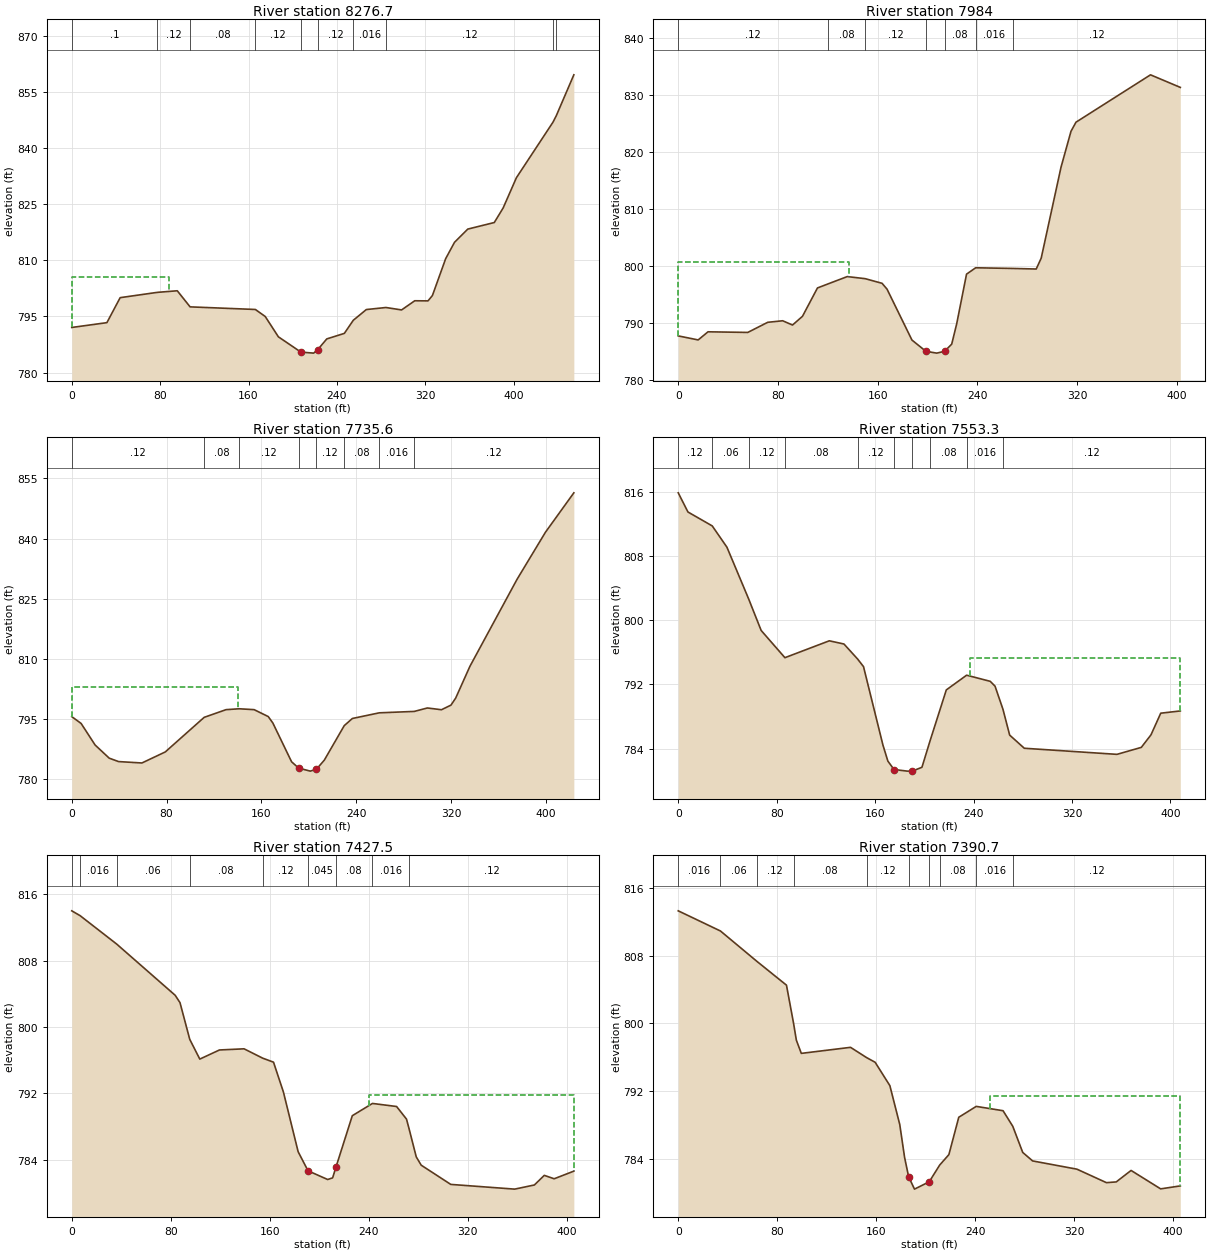
Type RM Length L Ch R = 1 ,8276.7  ,293.5,292.6,291.7
XS GIS Cut Line= 3
     1769049.795      409478.329     1769360.125      409471.818
     1769500.099      409505.455
#Sta/Elev= 30
       0  792.06    31.8  793.35    43.8  800.03   77.55801.4512    95.5  801.87
  107.09797.5693  166.17796.8712   175.1  794.99     187  789.56   207.4  785.47
   218.9   785.2   222.4  786.06   230.8     789   246.7  790.48   254.8793.9858
   266.6  796.85  284.34797.3978   298.5  796.75   310.4   799.2   322.4  799.17
   326.4   800.6   338.4  810.46   346.4  814.83   358.4  818.36   382.4  820.12
   390.4     824   402.4  832.09  435.49 846.934   438.5 848.666   454.4  859.61
#Mann= 10 ,-1 , 0
       0      .1       0   77.55     .12       0  107.09     .08       0
  166.17     .12       0   207.4    .045       0   222.4     .12       0
   254.8    .016       0  284.34     .12       0  435.49      .1       0
   438.5     .12       0
#XS Ineff= 2 , 0
           87.93  805.51
Permanent Ineff=
       F       F
Bank Sta=207.4,222.4
XS Rating Curve= 0 ,0
Exp/Cntr=0.3,0.1

Type RM Length L Ch R = 1 ,7984    ,248.4,248.4,248.4
XS GIS Cut Line= 2
     1769066.071      409768.042     1769468.632      409752.851
#Sta/Elev= 30
       0  787.67      16  786.96    23.9  788.39    55.8  788.28    71.8  790.06
    83.8  790.33    91.7  789.58    99.7  791.12   111.7   796.1  120.41796.8319
   135.6   798.1  149.97797.7337   163.5  796.92   167.5   795.9   187.5  786.94
   198.7  784.96   207.4  784.64   213.7  784.96   219.4  786.22   223.4  789.79
   231.3  798.53  238.64799.6484   268.2799.5325   287.2  799.43   291.2  801.34
   307.1  817.34   315.1  823.65   319.1  825.25   378.9  833.58   402.8  831.37
#Mann= 7 ,-1 , 0
       0     .12       0  120.41     .08       0  149.97     .12       0
   198.7    .045       0   213.7     .08       0  238.64    .016       0
   268.2     .12       0
#XS Ineff= 2 , 0
          137.36  800.74
Permanent Ineff=
       F       F
Bank Sta=198.7,213.7
XS Rating Curve= 0 ,0
Exp/Cntr=0.3,0.1

Type RM Length L Ch R = 1 ,7735.6  ,181,182.3,183.5
XS GIS Cut Line= 3
     1769074.751      410015.438     1769366.635      410004.587
     1769466.462      409918.867
#Sta/Elev= 30
       0  795.64     7.9  793.94    19.7  788.57    31.6  785.29    39.5  784.44
    59.2  784.09    78.9  786.84  111.73795.4637   130.2  797.38  141.28 797.599
   153.9  797.38   165.8  795.66   169.7  794.05   185.5  784.39   191.5  782.81
   201.3  782.06   206.5  782.54   213.1  784.79  229.95 793.399   236.8  795.18
  259.51796.5897  289.06796.9416   300.1   797.8     312  797.36     320  798.51
     324  800.27     336  808.18   375.8  829.88   399.7  841.58   423.7  851.42
#Mann= 8 ,-1 , 0
       0     .12       0  111.73     .08       0  141.28     .12       0
   191.5    .045       0   206.5     .12       0  229.95     .08       0
  259.51    .016       0  289.06     .12       0
#XS Ineff= 2 , 0
          140.56  803.06
Permanent Ineff=
       F       F
Bank Sta=191.5,206.5
XS Rating Curve= 0 ,0
Exp/Cntr=0.3,0.1

Type RM Length L Ch R = 1 ,7553.3  ,125.8,125.8,125.7
XS GIS Cut Line= 2
     1769099.708      410185.794     1769507.694      410193.389
#Sta/Elev= 30
       0  815.88     7.9  813.49   27.63811.7579    39.6   809.1   57.17802.6834
    67.4  798.73   86.71795.3359   122.8  797.44   134.7  797.04  145.79795.1718
   150.6  794.22   166.4  784.44   170.4  782.45   175.4   781.4   186.2   781.2
   190.4  781.21   198.1  781.68  204.87785.0654   217.9  791.32  234.41793.1548
   253.6  792.39   257.5  791.79  263.95 788.906   269.4  785.69   281.3  784.05
   356.6  783.29   376.4  784.16   384.3  785.73   392.2  788.42   408.1   788.7
#Mann= 10 ,-1 , 0
       0     .12       0   27.63     .06       0   57.17     .12       0
   86.71     .08       0  145.79     .12       0   175.4    .045       0
   190.4     .12       0  204.87     .08       0  234.41    .016       0
  263.95     .12       0
#XS Ineff= 2 , 0
                          237.48          795.31
Permanent Ineff=
       F       F
Bank Sta=175.4,190.4
XS Rating Curve= 0 ,0
Exp/Cntr=0.3,0.1

Type RM Length L Ch R = 1 ,7427.5  ,36.9,36.9,36.9
XS GIS Cut Line= 2
     1769091.027      410311.662     1769496.843      410318.172
#Sta/Elev= 30
       0  814.02    6.77813.4338   36.31 810.009    83.6  803.83    87.5  802.94
   95.39798.5093   103.5  796.13   119.4  797.23   139.3  797.37  154.47796.2339
   163.1  795.76   171.1  792.16     183  784.96     191  782.65   206.9   781.6
   210.9   781.8  213.55783.0786   226.8   789.3  243.09790.7776   262.6  790.41
   270.6  788.89  272.63787.7582   278.5  784.33   282.5  783.33   306.4  781.01
   358.1  780.44     374  780.94     382   782.1     390  781.69   405.9  782.61
#Mann= 9 ,-1 , 0
       0     .06       0    6.77    .016       0   36.31     .06       0
   95.39     .08       0  154.47     .12       0     191    .045       0
  213.55     .08       0  243.09    .016       0  272.63     .12       0
#XS Ineff= 2 , 0
                          240.05          791.83
Permanent Ineff=
       F       F
Bank Sta=191,213.55
XS Rating Curve= 0 ,0
Exp/Cntr=0.3,0.1

Type RM Length L Ch R = 1 ,7390.7  ,83.4,83.2,83.2
XS GIS Cut Line= 2
     1769093.198      410348.554     1769499.014      410355.065
#Sta/Elev= 30
       0  813.26   34.14810.8853   63.68807.3023    87.5  804.51   93.22800.0364
    95.5  798.03    99.5  796.48   139.3  797.19   152.3795.9813   159.2  795.43
   171.1  792.68   179.1   788.1     183  784.23  186.26  781.96     191   780.5
   202.9  781.36  211.38783.3348   218.8  784.56   226.8  788.96  240.92 790.239
   262.6  789.73  270.46787.8944   278.5  784.82   286.5  783.82   322.3  782.85
   346.2  781.26   354.1  781.35   366.1   782.7     390  780.53   405.9  780.88
#Mann= 10 ,-1 , 0
       0    .016       0   34.14     .06       0   63.68     .12       0
   93.22     .08       0   152.3     .12       0  186.26    .045       0
   202.9     .12       0  211.38     .08       0  240.92    .016       0
  270.46     .12       0
#XS Ineff= 2 , 0
                          252.25          791.47
Permanent Ineff=
       F       F
Bank Sta=186.26,202.9
XS Rating Curve= 0 ,0
Exp/Cntr=0.3,0.1

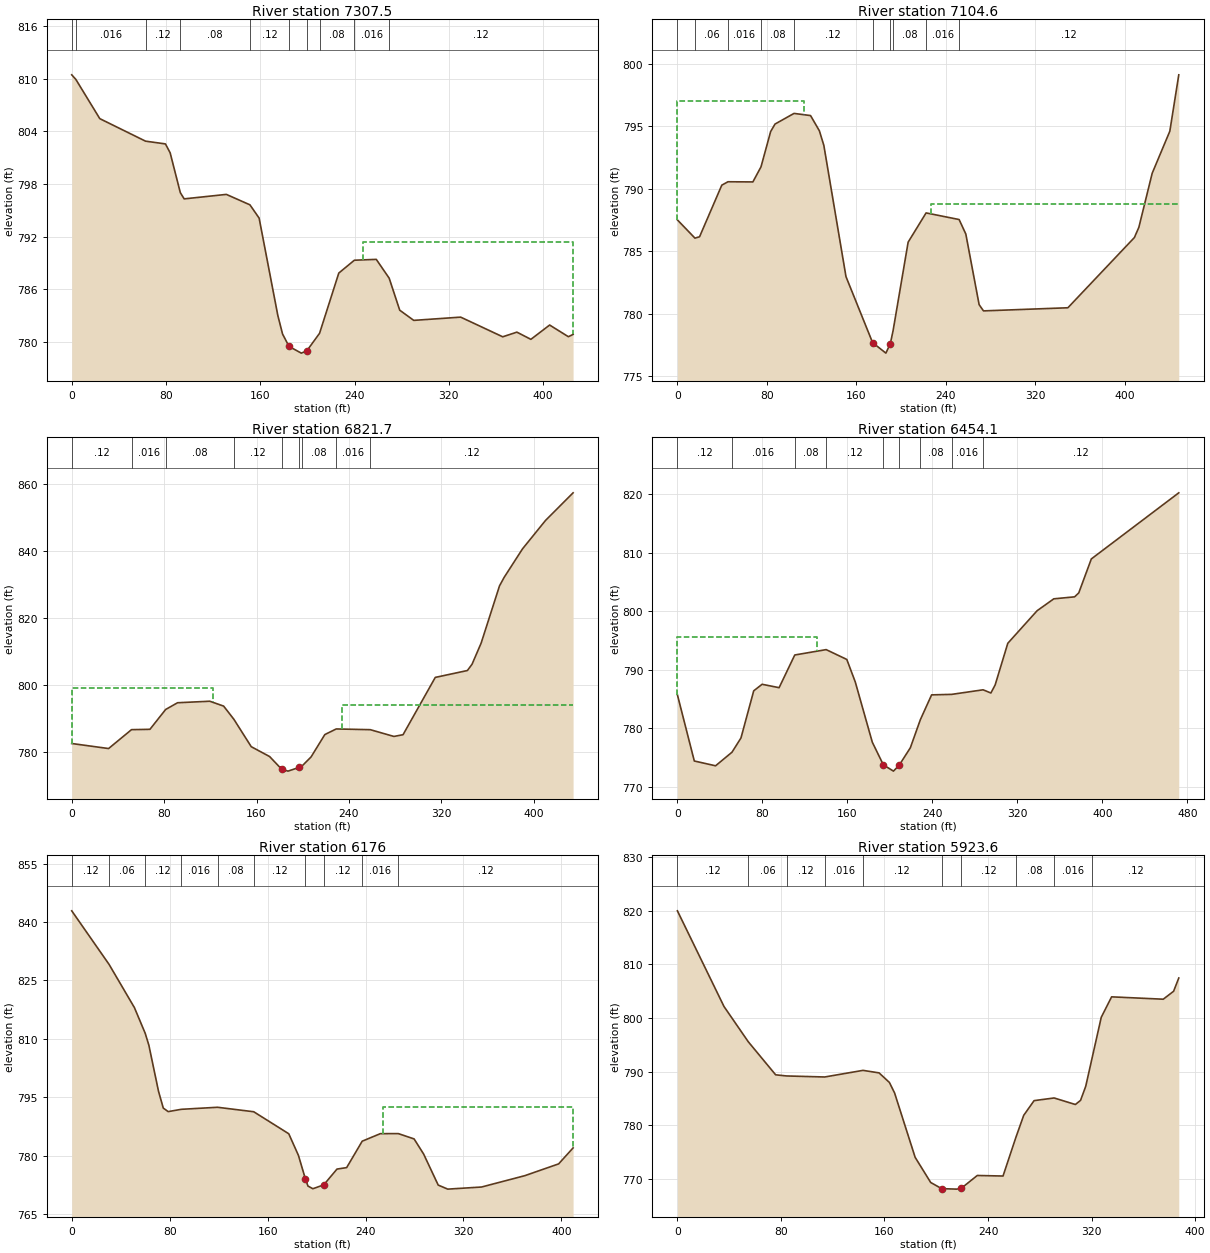
Type RM Length L Ch R = 1 ,7307.5  ,203,202.9,202.6
XS GIS Cut Line= 2
     1769094.283      410432.105      1769519.63      410436.445
#Sta/Elev= 30
       0  810.44    3.51809.9135    23.8  805.45   62.59802.8855    79.5  802.57
    83.5  801.56   92.13797.0212    95.4  796.31   131.2  796.82   151.2795.6318
     159  794.12   174.9  783.01   178.9  780.91   184.4   779.5   194.8  778.74
   199.4  778.99  210.28780.9988   226.6  787.86  239.81789.3218   258.4  789.42
  269.35787.2769   278.3  783.63   290.2  782.47     330  782.84   365.7   780.6
   377.7  781.13   389.6  780.31   405.5  781.94   421.4  780.61   425.4  780.87
#Mann= 10 ,-1 , 0
       0     .12       0    3.51    .016       0   62.59     .12       0
   92.13     .08       0   151.2     .12       0   184.4    .045       0
   199.4     .12       0  210.28     .08       0  239.81    .016       0
  269.35     .12       0
#XS Ineff= 2 , 0
                          247.11          791.38
Permanent Ineff=
       F       F
Bank Sta=184.4,199.4
XS Rating Curve= 0 ,0
Exp/Cntr=0.3,0.1

Type RM Length L Ch R = 1 ,7104.6  ,283,282.8,282.4
XS GIS Cut Line= 2
     1769111.644      410631.758      1769560.09      410637.084
#Sta/Elev= 30
       0   787.5   15.69786.0426    19.8  786.15    39.7  790.28   45.23790.5535
    67.5  790.54   74.77791.7462    83.4  794.57    87.3  795.17  104.31796.0222
   119.1  795.85     127  794.63     131  793.46   150.8  782.96   174.6  777.68
   186.5  776.84   190.5  777.61  192.92778.6324   206.4  785.72  222.46788.0598
     252  787.53     258  786.37   269.9  780.72   273.8  780.22   349.3  780.47
   408.8  786.09   412.8  786.91   424.7  791.23   440.5   794.6   448.5  799.11
#Mann= 10 ,-1 , 0
       0     .12       0   15.69     .06       0   45.23    .016       0
   74.77     .08       0  104.31     .12       0   174.6    .045       0
   190.5     .12       0  192.92     .08       0  222.46    .016       0
     252     .12       0
#XS Ineff= 2 , 0
          112.97  797.03  226.57          788.81
Permanent Ineff=
       F       F
Bank Sta=174.6,190.5
XS Rating Curve= 0 ,0
Exp/Cntr=0.3,0.1

Type RM Length L Ch R = 1 ,6821.7  ,368.1,367.6,367.1
XS GIS Cut Line= 3
     1769105.133      410916.046     1769383.996      410916.046
     1769530.481      410967.044
#Sta/Elev= 30
       0  782.67    31.9  781.17   51.74786.7916    67.7  786.89   81.28792.7899
    91.6   794.8   119.5  795.25   131.5   793.8  140.35789.8799   155.4  781.72
   171.3  778.79   181.6  775.06   187.2  774.45   196.6  775.53  199.42775.9894
   207.2  778.68   219.1  785.33  228.95787.0026  258.49786.7817   278.9  784.77
   286.8  785.29   314.7  802.34   342.5  804.39   346.5  806.24   354.4  812.55
   370.3  829.58   374.3   832.1   390.2  840.59   410.1  849.04     434  857.27
#Mann= 9 ,-1 , 0
       0     .12       0   51.74    .016       0   81.28     .08       0
  140.35     .12       0   181.6    .045       0   196.6     .12       0
  199.42     .08       0  228.95    .016       0  258.49     .12       0
#XS Ineff= 2 , 0
          121.95  799.29  234.27          794.18
Permanent Ineff=
       F       F
Bank Sta=181.6,196.6
XS Rating Curve= 0 ,0
Exp/Cntr=0.3,0.1

Type RM Length L Ch R = 1 ,6454.1  ,276.9,278.1,278.6
XS GIS Cut Line= 3
     1769076.007      411283.272     1769394.847      411277.374
     1769536.991       411220.95
#Sta/Elev= 30
       0   785.7    15.9   774.4    35.9  773.58   51.34775.8957    59.8  778.33
    71.8  786.38    79.7   787.5    95.7  786.92  110.42792.4986  139.96793.4174
   159.4  791.74   167.4  787.88   183.4  777.61   193.8  773.74   203.3  772.67
   208.8  773.71   219.2  776.66  228.59781.4409   239.2  785.69  258.13 785.777
  287.67786.5563     295  786.01     299  787.39   310.9   794.5   338.5  800.06
   354.2  802.09   373.8  802.43   377.7  803.11   389.5   808.9   471.8  820.19
#Mann= 9 ,-1 , 0
       0     .12       0   51.34    .016       0  110.42     .08       0
  139.96     .12       0   193.8    .045       0   208.8     .12       0
  228.59     .08       0  258.13    .016       0  287.67     .12       0
#XS Ineff= 2 , 0
          130.94  795.64
Permanent Ineff=
       F       F
Bank Sta=193.8,208.8
XS Rating Curve= 0 ,0
Exp/Cntr=0.3,0.1

Type RM Length L Ch R = 1 ,6176    ,252.6,252.4,252.6
XS GIS Cut Line= 3
     1769096.871      411550.533     1769301.641      411556.658
     1769506.371      411556.658
#Sta/Elev= 30
       0  842.87   30.49829.1136    51.2  818.01   60.03811.3986      63  808.36
    70.9   796.5    74.8  792.18    78.8  791.28   89.58791.8696  119.13792.3905
  148.68791.2421   177.3  785.59   185.2  780.04   190.9  773.98     193  772.15
     197  771.46   205.9  772.46   216.7  776.51   224.6  776.89  237.31783.6787
   252.1  785.61  266.85785.6246   279.7  784.26   287.5  780.37   299.4   772.4
   307.2  771.36   334.8   771.9   370.2  774.82   397.8  777.85   409.6  781.95
#Mann= 10 ,-1 , 0
       0     .12       0   30.49     .06       0   60.03     .12       0
   89.58    .016       0  119.13     .08       0  148.68     .12       0
   190.9    .045       0   205.9     .12       0  237.31    .016       0
  266.85     .12       0
#XS Ineff= 2 , 0
                          254.17          792.35
Permanent Ineff=
       F       F
Bank Sta=190.9,205.9
XS Rating Curve= 0 ,0
Exp/Cntr=0.3,0.1

Type RM Length L Ch R = 1 ,5923.6  ,140.5,139.6,138.4
XS GIS Cut Line= 2
     1769072.581      411803.633     1769459.951      411810.143
#Sta/Elev= 30
       0  819.94      36  802.12   54.77795.5514    75.9   789.4   84.31789.1866
  113.85788.9954  143.39790.2277   155.8  789.76   163.8  787.98   167.8  786.02
   183.7  774.03   195.7  769.35   204.2   768.2   215.7  768.11   219.2  768.24
   231.7  770.65   251.6  770.55  261.55777.7595   267.6  781.86   275.6  784.59
  291.09785.0868   307.5  783.87   311.5  784.64   315.5  787.26  320.63 792.749
   327.5  800.11   335.5  803.92   375.4  803.48   383.4  804.96   387.4  807.43
#Mann= 10 ,-1 , 0
       0     .12       0   54.77     .06       0   84.31     .12       0
  113.85    .016       0  143.39     .12       0   204.2    .045       0
   219.2     .12       0  261.55     .08       0  291.09    .016       0
  320.63     .12       0
Bank Sta=204.2,219.2
XS Rating Curve= 0 ,0
Exp/Cntr=0.3,0.1

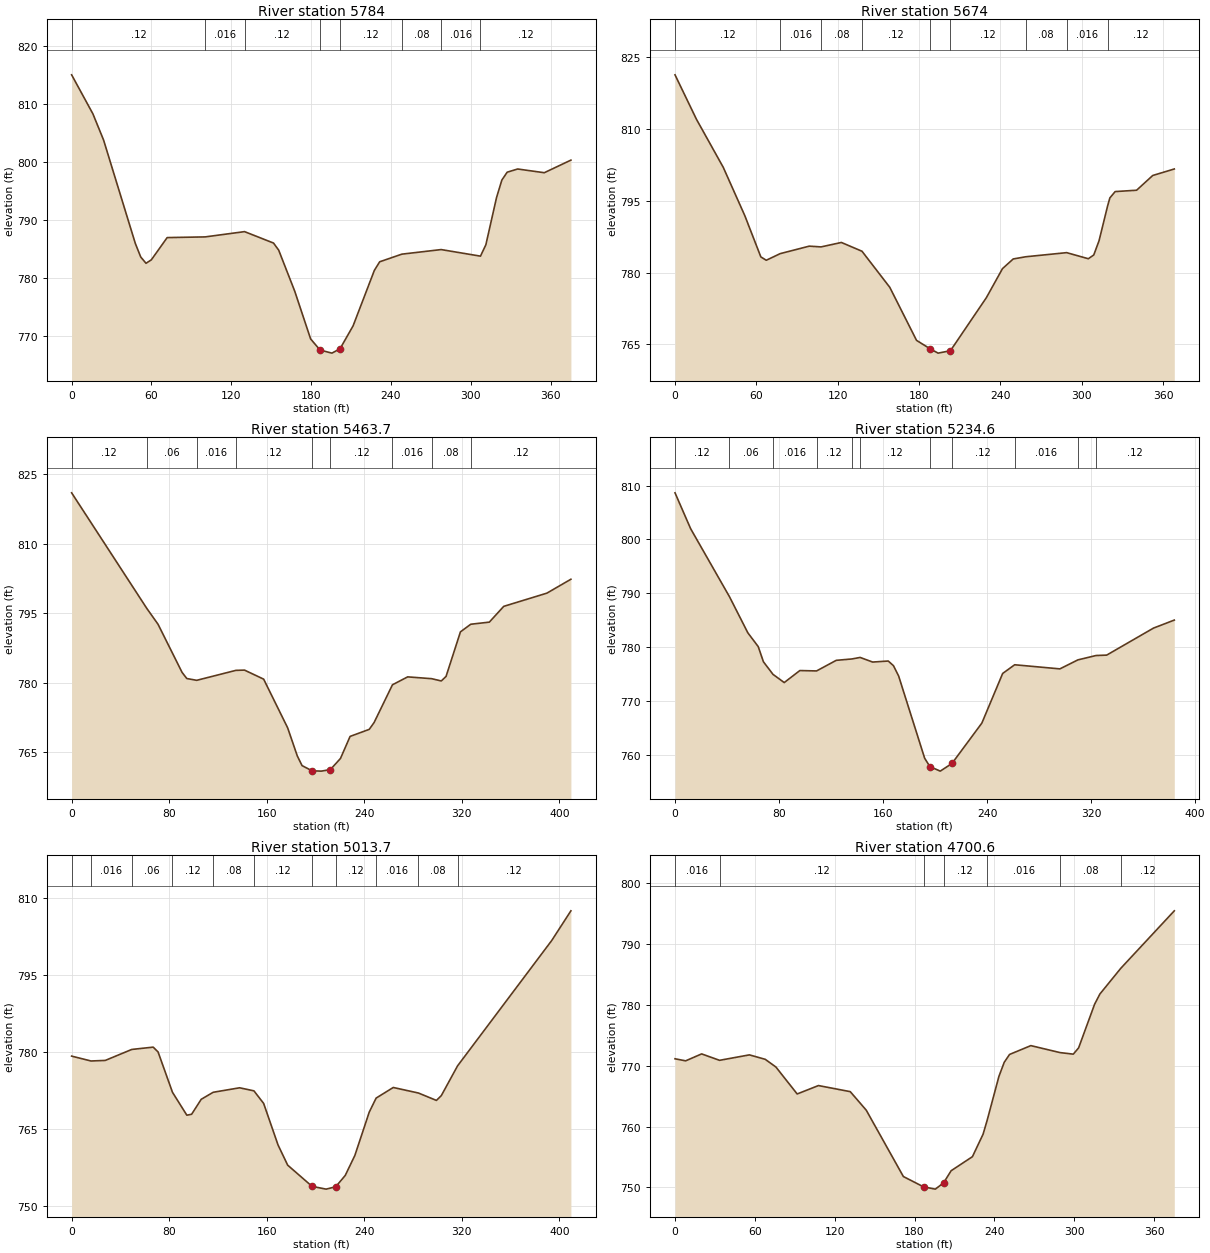
Type RM Length L Ch R = 1 ,5784    ,114.1,110.1,106
XS GIS Cut Line= 2
     1769086.056       411950.85     1769461.056      411939.739
#Sta/Elev= 30
       0  815.01      16  808.28      24  803.78    47.9  785.93    51.9  783.63
    55.9  782.53    59.9  783.13    71.8  786.96  100.41787.0797  129.95787.9881
   151.7  786.02   155.6   784.8   167.6  777.76   179.6   769.5   186.7  767.58
   195.6  767.05   201.7   767.8   211.5  771.74   227.5  781.31   231.5  782.79
  248.15784.1056   277.7784.8953  307.25783.7625   311.3  785.73   319.3  793.85
   323.3  796.87   327.3  798.23   335.2  798.78   355.2  798.14   375.2  800.31
#Mann= 8 ,-1 , 0
       0     .12       0  100.41    .016       0  129.95     .12       0
   186.7    .045       0   201.7     .12       0  248.15     .08       0
   277.7    .016       0  307.25     .12       0
Bank Sta=186.7,201.7
XS Rating Curve= 0 ,0
Exp/Cntr=0.3,0.1

Type RM Length L Ch R = 1 ,5674    ,214.6,210.2,205.7
XS GIS Cut Line= 2
     1769110.559      412093.346     1769470.802      412017.391
#Sta/Elev= 30
       0  821.31    15.8  812.03    35.6  801.97    51.5  791.87    63.3  783.27
    67.3  782.57   77.53783.9528      99  785.52  107.71785.3604   122.7  786.29
   137.9784.4512   158.4  776.91   178.1  765.84   188.1  764.08     194  763.17
   203.1  763.67   229.6  774.75   241.5  780.82   249.4  782.84  258.64783.3001
  288.82784.1622   304.8  782.89   308.8  783.67   312.7  786.64  319.01793.9058
   320.7   795.6   324.6  796.92   340.4   797.2   352.3  800.28   368.2  801.64
#Mann= 9 ,-1 , 0
       0     .12       0   77.53    .016       0  107.71     .08       0
   137.9     .12       0   188.1    .045       0   203.1     .12       0
  258.64     .08       0  288.82    .016       0  319.01     .12       0
Bank Sta=188.1,203.1
XS Rating Curve= 0 ,0
Exp/Cntr=0.3,0.1

Type RM Length L Ch R = 1 ,5463.7  ,231.2,229.2,227.2
XS GIS Cut Line= 3
     1769180.646      412331.872     1769368.992      412251.569
     1769557.337      412171.266
#Sta/Elev= 30
       0  820.95   61.75795.9835    70.9  792.59    90.6  782.21    94.5  780.89
   102.6780.5077  134.71782.6525   141.8  782.71   157.5  780.76   177.2  770.25
   185.1  764.19     189  762.11   197.2  760.99   204.8  760.92   212.2  761.25
   220.5  763.65   228.4  768.41   244.1  769.93   248.1  771.41  263.14779.5414
   275.6  781.25  295.25780.8621   303.2  780.37   307.1  781.35   318.9  790.96
  327.36792.6028   342.6  793.06   354.4  796.46   389.8  799.31   409.5  802.31
#Mann= 9 ,-1 , 0
       0     .12       0   61.75     .06       0   102.6    .016       0
  134.71     .12       0   197.2    .045       0   212.2     .12       0
  263.14    .016       0  295.25     .08       0  327.36     .12       0
Bank Sta=197.2,212.2
XS Rating Curve= 0 ,0
Exp/Cntr=0.3,0.1

Type RM Length L Ch R = 1 ,5234.6  ,220.6,220.8,220.9
XS GIS Cut Line= 2
     1769297.191      412549.075     1769635.732      412367.869
#Sta/Elev= 30
       0  808.66      12     802   41.87789.3613      56  782.65      64  780.08
      68  777.26   75.37774.9213      84   773.4      96  775.63  108.87775.5609
     124  777.53  136.06777.7854  142.37778.0689     152  777.21     164   777.4
     168  776.54     172  774.61     192  759.34     196  757.79     204  756.94
     213  758.36     236  765.87     252  775.09  261.24776.7075     296  775.94
  309.87777.6146  323.83 778.426     332   778.5     368  783.52     384  785.01
#Mann= 11 ,-1 , 0
       0     .12       0   41.87     .06       0   75.37    .016       0
  108.87     .12       0  136.06     .08       0  142.37     .12       0
     196    .045       0     213     .12       0  261.24    .016       0
  309.87     .08       0  323.83     .12       0
Bank Sta=196,213
XS Rating Curve= 0 ,0
Exp/Cntr=0.3,0.1

Type RM Length L Ch R = 1 ,5013.7  ,313.3,313.1,313
XS GIS Cut Line= 3
     1769408.642      412735.873     1769589.681      412640.231
      1769770.72      412544.589
#Sta/Elev= 30
       0  779.17   15.91778.2197    27.6  778.33   49.32780.4679    66.9  780.92
    70.9  779.98   82.72772.1213    94.5  767.66    98.4  767.84   106.3  770.76
  116.12772.1255   137.8     773  149.53772.4019   157.5  769.95   169.3  761.86
   177.2  757.93   197.2   753.8   208.7  753.26   216.6  753.72   224.4  755.92
   232.3  759.82   244.1  768.26  249.74770.9915   263.8  773.06  284.44771.9802
   299.2  770.54   303.2  771.47  316.55777.2739   393.8   801.7   409.5  807.47
#Mann= 11 ,-1 , 0
       0     .12       0   15.91    .016       0   49.32     .06       0
   82.72     .12       0  116.12     .08       0  149.53     .12       0
   197.2    .045       0   216.6     .12       0  249.74    .016       0
  284.44     .08       0  316.55     .12       0
Bank Sta=197.2,216.6
XS Rating Curve= 0 ,0
Exp/Cntr=0.3,0.1

Type RM Length L Ch R = 1 ,4700.6  ,304.7,304.8,304.7
XS GIS Cut Line= 2
     1769570.411      413005.419      1769901.14      412828.336
#Sta/Elev= 30
       0  771.14       8   770.8      20  771.94   33.48770.8858    55.9  771.78
    67.8  771.05    75.8  769.79    91.8  765.36   107.8  766.74   131.7  765.74
   143.7   762.7   171.6   751.8   186.8   750.1   195.6  749.73   201.8  750.75
   207.5  752.75   223.5  755.06   231.5  758.75   234.5760.9775   243.4  768.24
   247.4  770.56   251.4  771.85   267.4   773.3  289.37772.1537   299.3   771.9
   303.3  772.93   315.3  780.09   319.3  781.78  335.01786.0016   375.2  795.44
#Mann= 7 ,-1 , 0
       0    .016       0   33.48     .12       0   186.8    .045       0
   201.8     .12       0   234.5    .016       0  289.37     .08       0
  335.01     .12       0
Bank Sta=186.8,201.8
XS Rating Curve= 0 ,0
Exp/Cntr=0.3,0.1