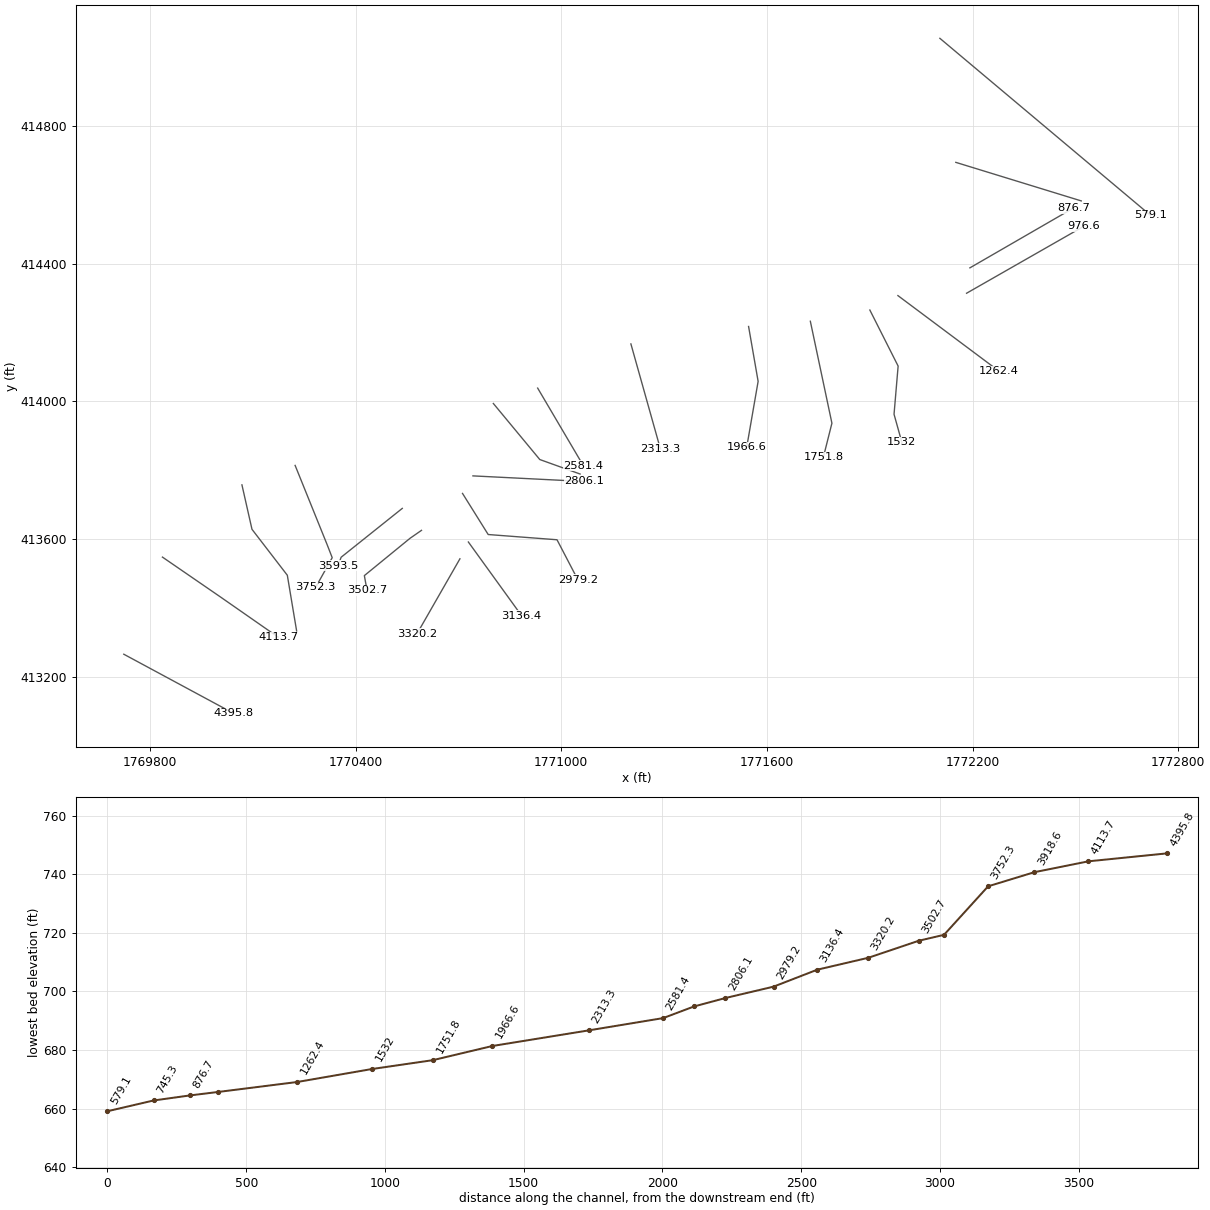
HEC-RAS study DRAWDYCK.prj: DRAWDYCK

--- DRAWDYCK.g01 (geometry) --- (continued)

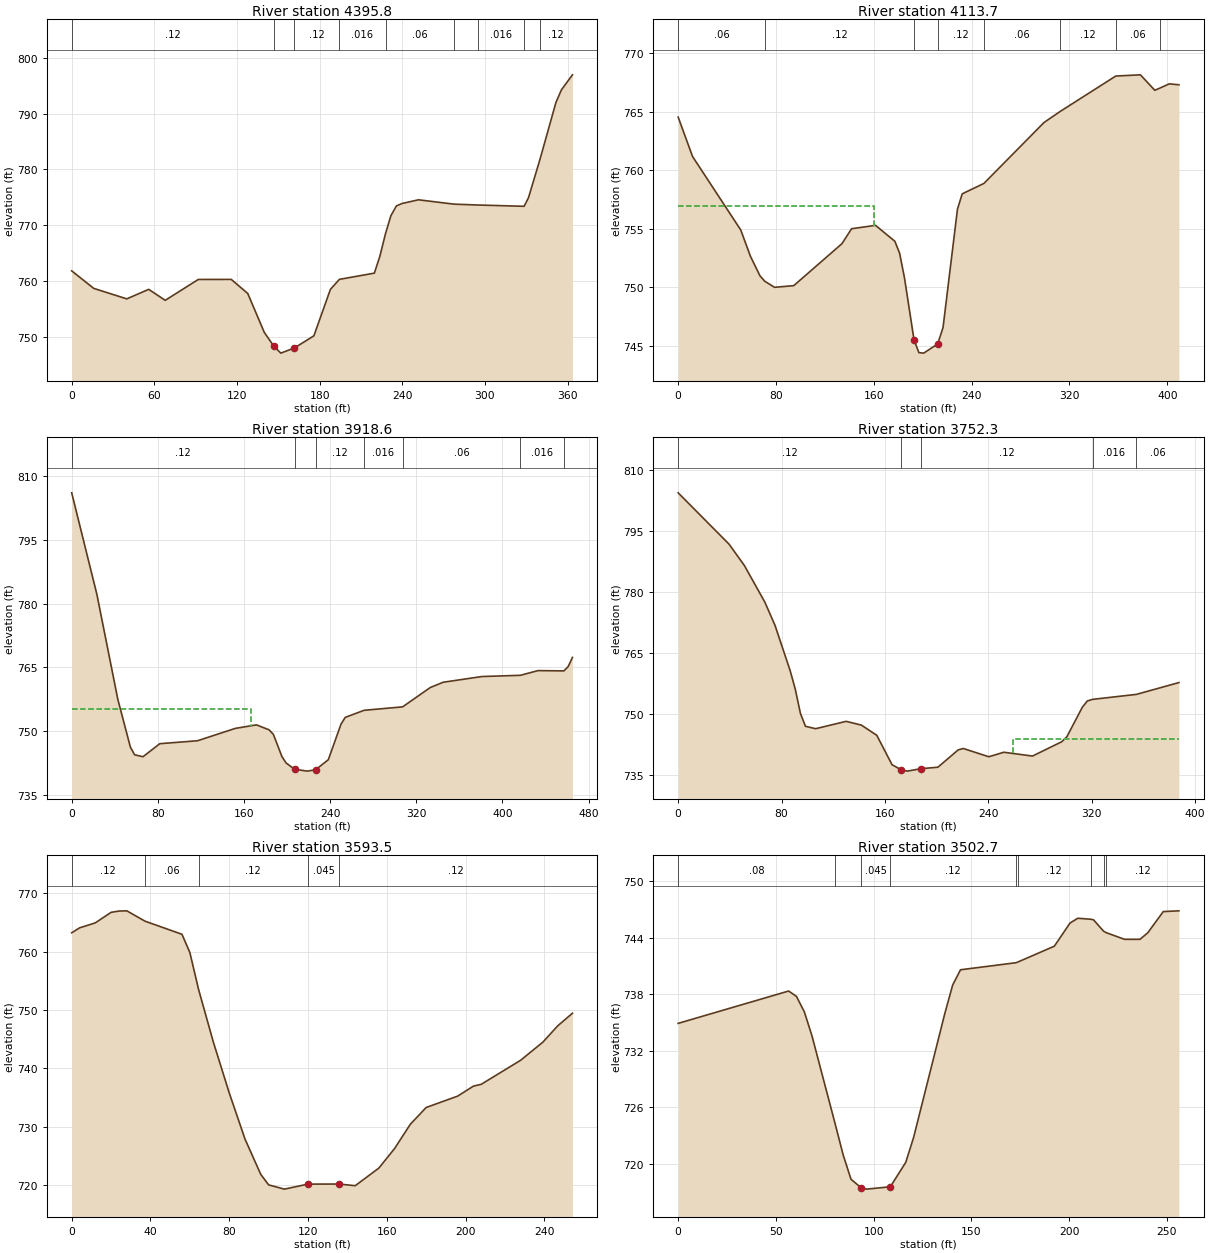
Type RM Length L Ch R = 1 ,4395.8  ,284.5,282.1,279.3
XS GIS Cut Line= 2
     1769724.057      413265.836      1770044.37      413093.961
#Sta/Elev= 30
       0  761.82      16  758.68      40   756.8    55.9  758.51    67.9  756.54
    91.9  760.28   115.8  760.29   127.8  757.77   139.8   750.8   146.7  748.33
   151.8  747.08   161.7  748.01   175.8  750.18   187.8   758.5  194.32760.2947
   219.7  761.41   223.7  764.43  227.84768.5251   231.7   771.7   235.7  773.45
   239.7  773.88   251.7  774.55  277.46773.7721  294.88773.6166   328.4 773.386
   331.6  774.93  339.93781.7978   351.5  791.98   355.5  794.25   363.5  796.94
#Mann= 9 ,-1 , 0
       0     .12       0   146.7    .045       0   161.7     .12       0
  194.32    .016       0  227.84     .06       0  277.46     .08       0
  294.88    .016       0   328.4     .08       0  339.93     .12       0
Bank Sta=146.7,161.7
XS Rating Curve= 0 ,0
Exp/Cntr=0.3,0.1

Type RM Length L Ch R = 1 ,4113.7  ,202.1,195.1,188.1
XS GIS Cut Line= 3
     1769836.804      413547.946     1770005.766      413432.299
     1770174.011      413315.602
#Sta/Elev= 30
       0  764.53    11.8  761.16    51.2  754.89    59.1  752.65    66.9  750.98
   70.87750.5135    78.8     750    94.5  750.14   133.9  753.72   141.8     755
   161.4  755.29   177.2  753.93   181.1  752.91   185.1  750.79   192.9   745.5
   196.9  744.42   200.8  744.38   212.2  745.16   216.6  746.56   228.4  756.67
   232.3  757.98  250.03758.8685   299.2  764.07  312.42765.0148  357.86768.0363
     378  768.14   389.8  766.82  393.81767.0006   401.6  767.37   409.5  767.29
#Mann= 8 ,-1 , 0
       0     .06       0   70.87     .12       0   192.9    .045       0
   212.2     .12       0  250.03     .06       0  312.42     .12       0
  357.86     .06       0  393.81    .016       0
#XS Ineff= 2 , 0
          160.46  756.95
Permanent Ineff=
       F       F
Bank Sta=192.9,212.2
XS Rating Curve= 0 ,0
Exp/Cntr=0.3,0.1

Type RM Length L Ch R = 1 ,3918.6  ,172.2,166.3,159.9
XS GIS Cut Line= 4
     1770068.675      413757.843     1770097.972      413628.719
     1770201.054      413495.256      1770228.18       413333.58
#Sta/Elev= 30
       0     806    23.4  782.14    42.8  757.55    54.5  746.29    58.4   744.5
    66.2  744.04    81.8   747.1   116.8  747.79     152   750.7   171.6  751.52
   183.4  750.34   187.3  749.28   195.2  744.09   199.1  742.57   206.9  741.11
   218.7  740.66   226.5  740.98   238.3  743.34   250.1   751.7     254  753.28
  271.53754.9391  307.31755.7506     333  760.29     345  761.53     381  762.87
  416.65763.1569     433  764.26  457.05764.1926     461  765.19     465  767.36
#Mann= 7 ,-1 , 0
       0     .12       0   206.9    .045       0   226.5     .12       0
  271.53    .016       0  307.31     .06       0  416.65    .016       0
  457.05     .08       0
#XS Ineff= 2 , 0
          166.24  755.36
Permanent Ineff=
       F       F
Bank Sta=206.9,226.5
XS Rating Curve= 0 ,0
Exp/Cntr=0.3,0.1

Type RM Length L Ch R = 1 ,3752.3  ,193.9,158.9,127.3
XS GIS Cut Line= 4
      1770223.84      413814.266     1770317.156      413584.232
     1770332.002      413546.249     1770283.825      413460.312
#Sta/Elev= 30
       0  804.39    39.4  791.74    51.2  786.51      67  777.52    74.9  771.79
    86.7  760.55    90.6  756.06    94.6  750.08    98.5  746.89   106.4   746.3
     130  748.11   141.8  747.18   153.7  744.68   165.5  737.43   172.7  736.17
   177.3  735.85   187.7  736.44     201  736.82   216.7  741.08   220.7  741.42
   240.4  739.39     252   740.5   274.2  739.56   296.9   743.1   300.8  744.32
   312.7  751.55   316.6  753.12  320.71753.5259  354.57754.7487   387.5  757.66
#Mann= 5 ,-1 , 0
       0     .12       0   172.7    .045       0   187.7     .12       0
  320.71    .016       0  354.57     .06       0
#XS Ineff= 2 , 0
                          258.79          743.78
Permanent Ineff=
       F       F
Bank Sta=172.7,187.7
XS Rating Curve= 0 ,0
Exp/Cntr=0.3,0.1

Type RM Length L Ch R = 1 ,3593.5  ,85.5,90.8,92.6
XS GIS Cut Line= 3
     1770536.429      413689.478     1770358.044      413547.551
     1770348.929      413522.812
#Sta/Elev= 30
       0  763.22       4  764.07      12  764.93      20  766.73      24  766.95
      28  766.99   37.24 765.214      56  762.97      60  759.85   64.43753.5161
      72  744.42      80  735.79      88  727.88      96  721.83     100  720.02
     108  719.29     120  720.15   135.8  720.16     144  719.88     156   722.9
     164  726.26     172  730.42     180  733.28     196  735.23     204  736.94
     208  737.26     228  741.38   239.3  744.49   246.8  747.27   254.3  749.44
#Mann= 5 ,-1 , 0
       0     .12       0   37.24     .06       0   64.43     .12       0
     120    .045       0   135.8     .12       0
Bank Sta=120,135.8
XS Rating Curve= 0 ,0
Exp/Cntr=0.3,0.1

Type RM Length L Ch R = 1 ,3502.7  ,174,182.5,191.1
XS GIS Cut Line= 4
     1770592.419      413625.676     1770559.126      413602.678
     1770425.752      413494.166     1770433.565      413451.197
#Sta/Elev= 30
       0  734.91    56.5  738.35    60.5  737.78    64.5  736.15    68.4  733.61
   80.07724.3941    84.4  720.91    88.4  718.33    93.5  717.44    96.4  717.28
   108.5  717.53   116.4  720.13   120.4  722.77   136.4  735.98   140.4  738.99
   144.4  740.61   172.8 741.361  173.67741.4284   192.4  743.12   200.4  745.58
   204.4  746.09  210.88 745.987   212.4  745.93  217.58744.7138  219.02744.5477
   228.3  743.85   236.2  743.85   240.2  744.55   248.1   746.8   256.1  746.88
#Mann= 9 ,-1 , 0
       0     .08       0   80.07     .12       0    93.5    .045       0
   108.5     .12       0   172.8    .016       0  173.67     .12       0
  210.88    .016       0  217.58     .08       0  219.02     .12       0
Bank Sta=93.5,108.5
XS Rating Curve= 0 ,0
Exp/Cntr=0.3,0.1

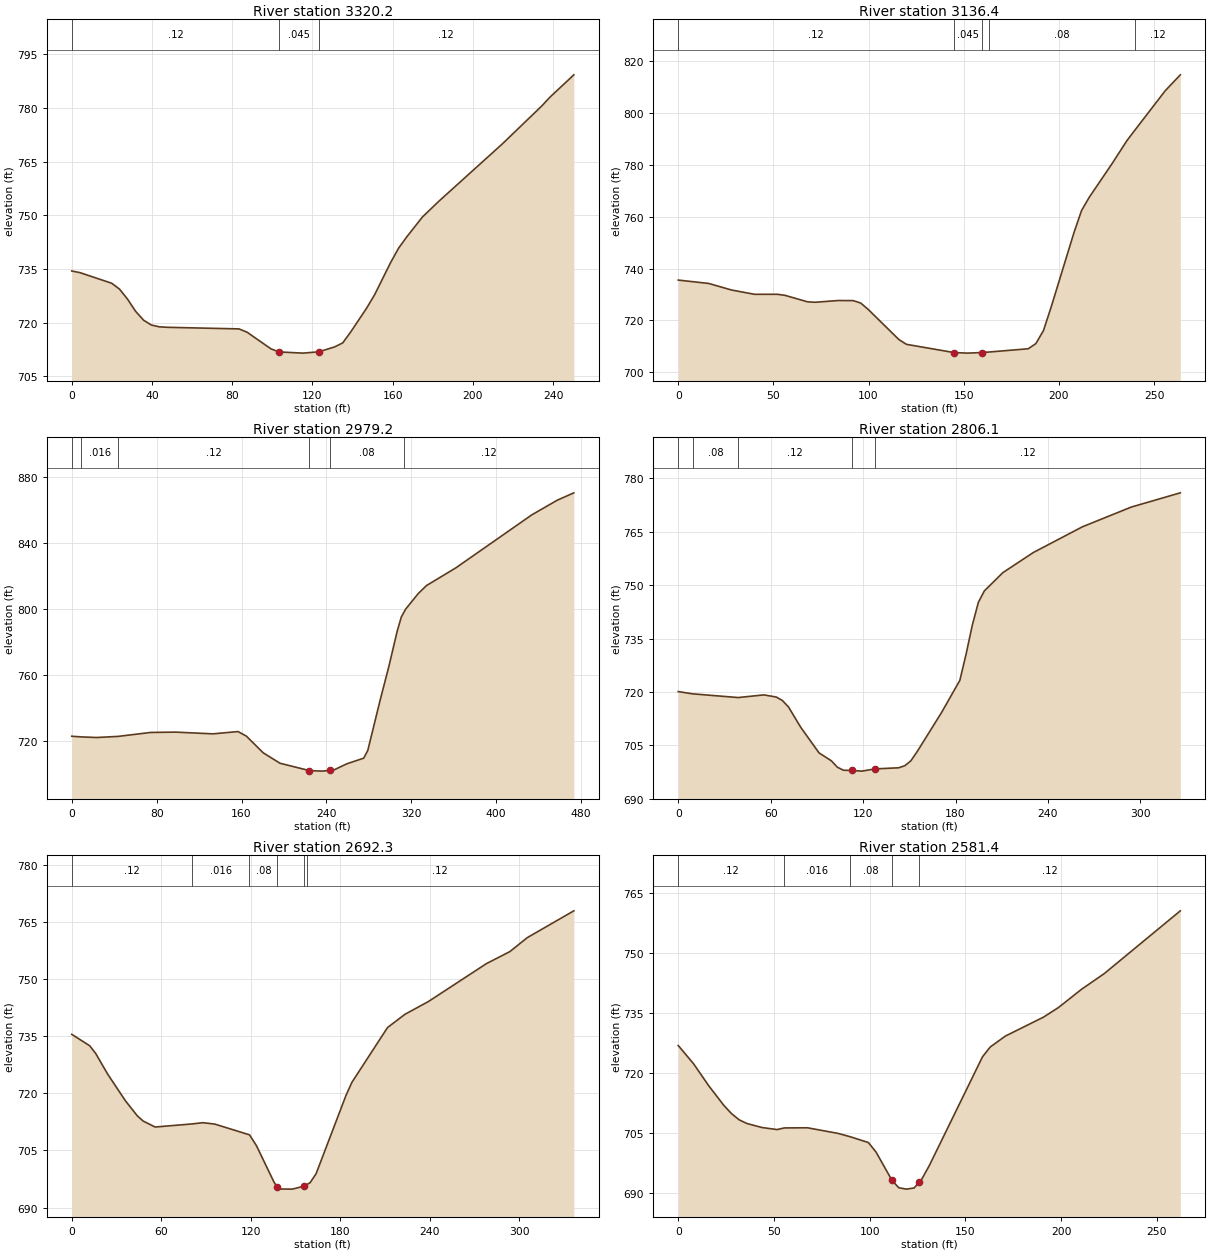
Type RM Length L Ch R = 1 ,3320.2  ,157.5,183.7,210
XS GIS Cut Line= 2
     1770704.526      413542.999     1770579.743      413325.985
#Sta/Elev= 30
       0  734.41       4  733.97    19.9  730.99    23.8  729.35    27.8  726.55
    31.8  723.16    35.8  720.66    39.7   719.3    43.7   718.8    47.7  718.67
    83.4  718.22    87.4   717.3    99.3  712.65   103.3  711.79   115.2  711.45
   123.2  711.82   131.1   713.2   135.1  714.32   139.1   717.4     147  724.03
     151  727.79   158.9  736.71   162.9  740.76   166.9  743.88   174.8   749.5
   182.8  753.81   214.6  769.92   234.4   780.6   238.4  783.02   250.3  789.26
#Mann= 3 ,-1 , 0
       0     .12       0   103.3    .045       0   123.2     .12       0
Bank Sta=103.3,123.2
XS Rating Curve= 0 ,0
Exp/Cntr=0.3,0.1

Type RM Length L Ch R = 1 ,3136.4  ,137.6,157.2,176.9
XS GIS Cut Line= 2
     1770729.137      413591.822     1770884.085       413378.28
#Sta/Elev= 30
       0  735.56      16  734.26      28  731.73      40  730.08      52  730.08
      56  729.69      68  727.16      72     727      84  727.67    91.9  727.64
    95.9   726.7    99.9  724.18   115.9  712.65   119.9  710.78   144.8  707.62
   151.9  707.39   159.8  707.63  163.44707.8253   183.9  709.07   187.9  711.06
   191.9  716.09   195.9  725.07   207.9  753.78   211.9  762.35   215.9  767.42
   227.9  780.41   235.8  789.38   239.8  793.23   255.8   808.5   263.8   814.7
#Mann= 5 ,-1 , 0
       0     .12       0   144.8    .045       0   159.8     .12       0
  163.44     .08       0   239.8     .12       0
Bank Sta=144.8,159.8
XS Rating Curve= 0 ,0
Exp/Cntr=0.3,0.1

Type RM Length L Ch R = 1 ,2979.2  ,172.5,173.2,173.7
XS GIS Cut Line= 4
     1770712.121      413732.886     1770786.991      413613.528
     1770987.729      413598.337     1771048.493      413482.235
#Sta/Elev= 30
       0  722.79    8.89722.3937    23.5  722.02   43.75722.6974    74.4   725.1
    97.8  725.29   133.1  724.24   156.7  725.63   164.6  722.84   180.4  712.74
   196.2  706.42   223.8  701.95   235.6  701.61   243.5  702.06   247.5  702.46
   259.3  706.06   275.1  709.47     279  714.16   290.9  745.38   298.8  765.01
   306.7  786.55   310.6  795.19  312.98797.9865   314.6  799.89   326.4  809.31
   334.3  814.26   362.1  825.06   433.5  857.16   457.4  866.03   473.2  870.57
#Mann= 6 ,-1 , 0
       0     .08       0    8.89    .016       0   43.75     .12       0
   223.8    .045       0   243.5     .08       0  312.98     .12       0
Bank Sta=223.8,243.5
XS Rating Curve= 0 ,0
Exp/Cntr=0.3,0.1

Type RM Length L Ch R = 1 ,2806.1  ,132.6,113.8,94.9
XS GIS Cut Line= 2
     1770742.503      413783.884     1771068.024      413767.608
#Sta/Elev= 30
       0   720.1    9.34719.4644   38.91  718.42    55.6  719.17    63.6  718.57
    67.6   717.6    71.6  715.76    79.5  710.07    91.4  702.87    99.4  700.64
   103.3  698.84   107.3  697.99   112.7  697.93   119.2  697.74   127.7  698.36
   143.1  698.68   147.1  699.26     151  700.64     155  703.16   170.9   714.2
   182.8  723.26   186.8  730.53   190.8  738.62   194.8  745.17   198.7   748.4
   210.7  753.53   230.5  759.19   262.3  766.41   294.1  771.97   325.9  775.97
#Mann= 5 ,-1 , 0
       0    .016       0    9.34     .08       0   38.91     .12       0
   112.7    .045       0   127.7     .12       0
Bank Sta=112.7,127.7
XS Rating Curve= 0 ,0
Exp/Cntr=0.3,0.1

Type RM Length L Ch R = 1 ,2692.3  ,114.5,110.9,107.3
XS GIS Cut Line= 3
     1770802.054      413994.166     1770937.471      413831.405
     1771055.003       413789.31
#Sta/Elev= 30
       0  735.45      12  732.46      16  730.46      24  725.06      36     718
    43.9  714.09    47.9  712.69    55.9  711.13   80.73711.9481    87.9  712.27
    95.9   711.9  119.15709.0851   123.8  706.25   135.8  696.51   137.7  695.52
   139.8  694.87   147.8  694.84   155.8  695.63  157.57696.0283   159.8  696.53
   163.8  698.88   183.8  719.38   187.8  722.85   211.7  737.23   223.4  740.71
     239  744.03     278     754   293.7  757.15   305.4  760.82   336.6  767.85
#Mann= 6 ,-1 , 0
       0     .12       0   80.73    .016       0  119.15     .08       0
   137.7    .045       0   155.8     .08       0  157.57     .12       0
Bank Sta=137.7,155.8
XS Rating Curve= 0 ,0
Exp/Cntr=0.3,0.1

Type RM Length L Ch R = 1 ,2581.4  ,273.7,268.1,262
XS GIS Cut Line= 2
     1770931.305      414038.876     1771064.769      413813.181
#Sta/Elev= 30
       0  726.84       8  722.28    15.9  716.78    23.8  711.86    27.8   709.8
    31.8  708.24    35.8  707.32    43.7  706.31    51.6  705.79   55.41706.1995
    67.5  706.24    83.4  704.84   89.73704.0114    99.3  702.55   103.3  700.17
  111.62693.0726   115.2  691.22   119.2  690.88   123.2  691.17   125.9  692.64
   127.1   693.3   131.1  696.76   158.9  724.01   162.9  726.45   170.8  729.19
   190.7  733.93   198.6  736.36   210.6  740.91   222.5  744.85   262.2  760.56
#Mann= 5 ,-1 , 0
       0     .12       0   55.41    .016       0   89.73     .08       0
  111.62    .045       0   125.9     .12       0
Bank Sta=111.62,125.9
XS Rating Curve= 0 ,0
Exp/Cntr=0.3,0.1

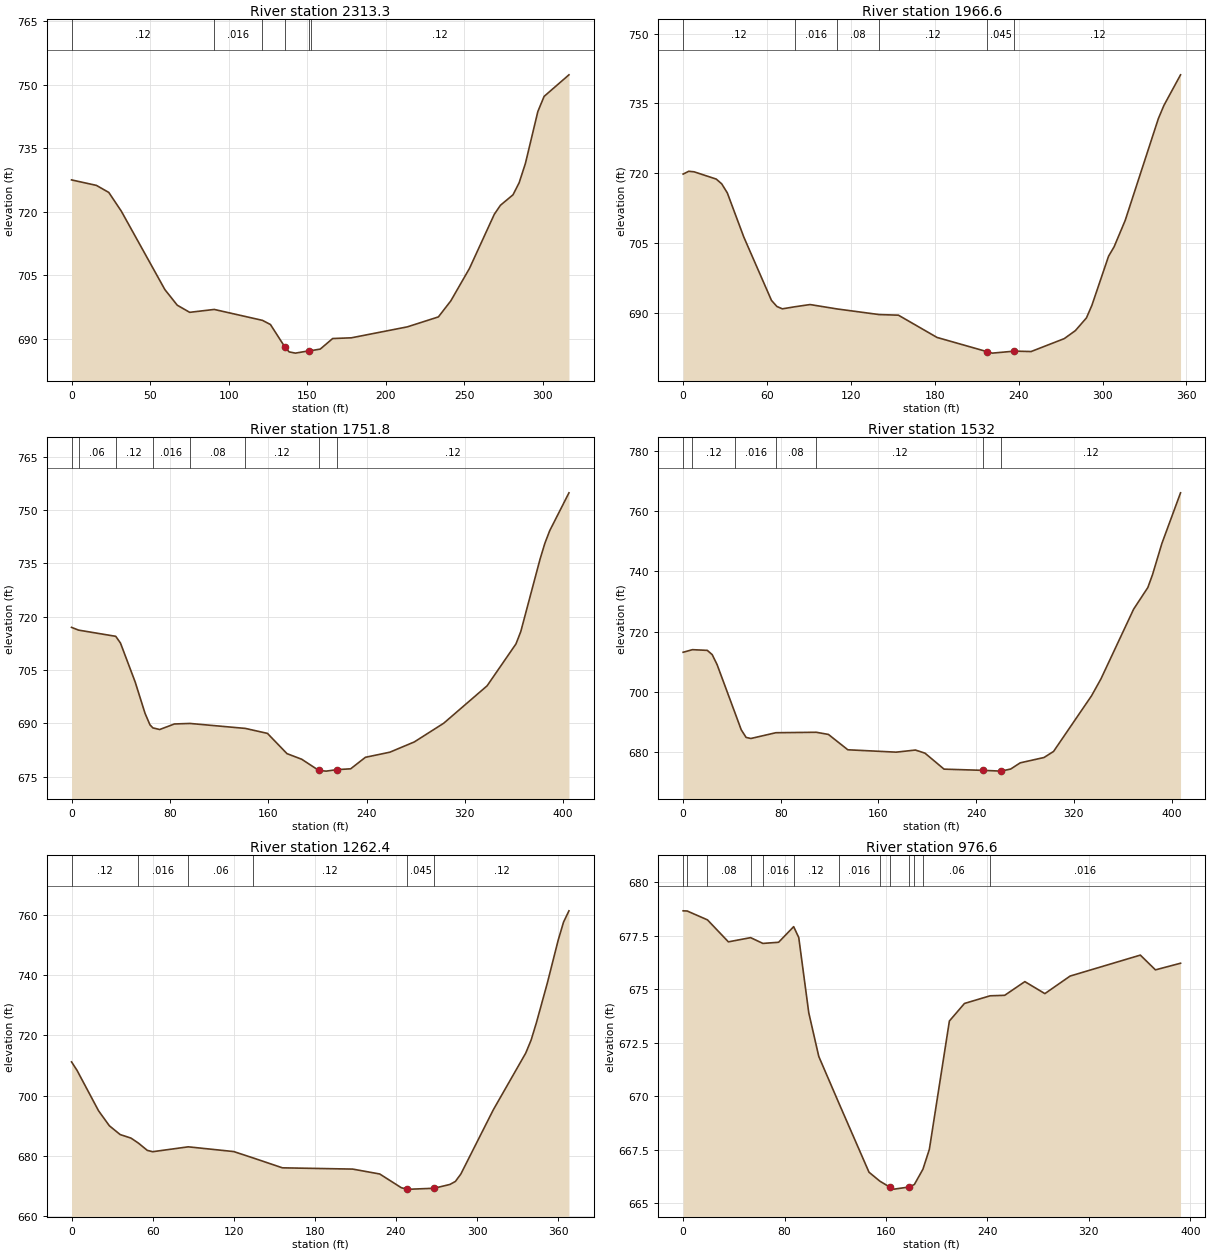
Type RM Length L Ch R = 1 ,2313.3  ,356.6,346.8,336.5
XS GIS Cut Line= 2
     1771203.273      414167.203      1771289.21      413862.516
#Sta/Elev= 30
       0  727.54    15.8  726.25    23.7  724.59    31.7  720.16    59.4  701.68
    67.3  697.99    75.2  696.31   90.83696.9913  121.52694.4187   126.6  693.44
   135.9  688.07   138.5  686.98   142.5  686.69   150.9  687.22  152.21687.2585
   158.3  687.64   166.2  690.13   178.1   690.3   213.7  692.88   233.5  695.23
   241.4  699.01   253.3  706.68   269.1  719.44     273  721.56     281  724.03
   284.9  726.87   288.9  731.44   296.8  743.66   300.8  747.24   316.6  752.32
#Mann= 6 ,-1 , 0
       0     .12       0   90.83    .016       0  121.52     .08       0
   135.9    .045       0   150.9     .08       0  152.21     .12       0
Bank Sta=135.9,150.9
XS Rating Curve= 0 ,0
Exp/Cntr=0.3,0.1

Type RM Length L Ch R = 1 ,1966.6  ,205.9,214.8,223.3
XS GIS Cut Line= 3
      1771546.54      414217.912     1771574.367      414058.479
     1771541.114      413867.435
#Sta/Elev= 30
       0  719.81       4  720.42     7.9   720.3    23.7  718.74    27.6  717.72
    31.6  715.78    43.4   706.3    63.2  692.69    67.1  691.38      71  690.88
   80.25691.3398    90.8   691.8  110.24690.8527  140.22689.6482     154  689.52
   181.6  684.74   217.2   681.7   221.2  681.37     237   681.8   248.9  681.71
   272.6  684.48   280.6  686.21   288.5  688.94   292.4  691.64   304.3  702.17
   308.3  704.22   316.2  709.86   339.9   731.7   343.9  734.56   355.8  741.13
#Mann= 6 ,-1 , 0
       0     .12       0   80.25    .016       0  110.24     .08       0
  140.22     .12       0   217.2    .045       0     237     .12       0
Bank Sta=217.2,237
XS Rating Curve= 0 ,0
Exp/Cntr=0.3,0.1

Type RM Length L Ch R = 1 ,1751.8  ,226.9,219.8,212.8
XS GIS Cut Line= 3
     1771726.661      414233.103     1771789.595      413936.879
     1771764.639      413838.138
#Sta/Elev= 30
       0  716.99    5.77716.2143   35.96714.4706    39.8  712.59    51.8   701.6
    59.8   692.8    63.8  689.57   66.16688.7047    71.7  688.24    83.7   689.8
   96.35689.9481  141.43688.5513   159.4  687.15   175.3  681.45   187.3  679.87
   201.2  676.72   207.2  676.53   216.2  676.96   227.1  677.18   239.1  680.42
     259  681.86   278.9  684.75   302.8  690.01   338.1  700.54   361.6  712.34
   365.5   715.8   381.2  736.21   385.1  740.65     389  744.17   404.7  754.86
#Mann= 8 ,-1 , 0
       0     .12       0    5.77     .06       0   35.96     .12       0
   66.16    .016       0   96.35     .08       0  141.43     .12       0
   201.2    .045       0   216.2     .12       0
Bank Sta=201.2,216.2
XS Rating Curve= 0 ,0
Exp/Cntr=0.3,0.1

Type RM Length L Ch R = 1 ,1532    ,246.4,269.5,292.4
XS GIS Cut Line= 4
     1771900.272      414265.655     1771982.738      414102.895
     1771970.802      413962.921     1771993.588      413881.541
#Sta/Elev= 30
       0  713.09    7.65713.9492    19.8  713.72    23.8  712.31    27.8     709
   42.82  692.53    47.6  687.26    51.6  684.72    55.5  684.37   75.93686.2909
  109.04686.4415     119  685.72   134.9  680.61   174.5  679.82   190.3  680.52
   198.1  679.48   213.7  674.16   245.5  673.76   260.5   673.5   268.3   674.2
   276.1  676.26   295.6  678.04   303.4  680.06   334.5  698.59   342.2  704.21
     369  727.46   380.6  734.64   384.4  738.88   392.1   749.3   407.4  766.19
#Mann= 7 ,-1 , 0
       0     .06       0    7.65     .12       0   42.82    .016       0
   75.93     .08       0  109.04     .12       0   245.5    .045       0
   260.5     .12       0
Bank Sta=245.5,260.5
XS Rating Curve= 0 ,0
Exp/Cntr=0.3,0.1

Type RM Length L Ch R = 1 ,1262.4  ,253.4,285.9,320.6
XS GIS Cut Line= 2
     1771982.136      414307.611     1772277.315      414087.916
#Sta/Elev= 30
       0  711.24       4  708.49      20  695.03      28  690.06      36  687.15
      44  685.98   49.54684.3041      56  681.93      60  681.47   86.36 683.089
     120  681.52  134.25679.4232     156  676.13     208  675.71     228  674.09
     244  669.53     248  669.08     252  669.07   268.3  669.36     280  670.63
     284  671.63     288  674.06     312  695.33     336  714.14     340  718.46
     344  724.36     352  737.36     360  751.53     364  757.58     368  761.31
#Mann= 6 ,-1 , 0
       0     .12       0   49.54    .016       0   86.36     .06       0
  134.25     .12       0     248    .045       0   268.3     .12       0
Bank Sta=248,268.3
XS Rating Curve= 0 ,0
Exp/Cntr=0.3,0.1

Type RM Length L Ch R = 1 ,976.6   ,96.4,99.8,98.9
XS GIS Cut Line= 2
      1772182.39      414314.483     1772523.408      414508.489
#Sta/Elev= 30
       0  678.67     3.2 678.662   19.21678.2469    35.7  677.22    53.2677.4163
   62.93677.1465    75.3   677.2   87.18677.9301    91.2  677.42    99.1   673.9
     107  671.86  122.66669.7054   146.6  666.45  155.14666.0334   163.4  665.74
   166.4  665.66   178.4  665.76  182.39665.8785  189.12666.5898   194.2  667.52
     210  673.52   221.9  674.34  242.12674.6976   253.6  674.72   269.5  675.36
   285.3   674.8   305.2  675.62   360.6   676.6   372.5  675.91   392.3  676.22
#Mann= 13 ,-1 , 0
       0     .08       0     3.2    .016       0   19.21     .08       0
    53.2     .12       0   62.93    .016       0   87.18     .12       0
  122.66    .016       0  155.14     .12       0   163.4    .045       0
   178.4     .12       0  182.39    .016       0  189.12     .06       0
  242.12    .016       0
Bank Sta=163.4,178.4
XS Rating Curve= 0 ,0
Exp/Cntr=0.3,0.1

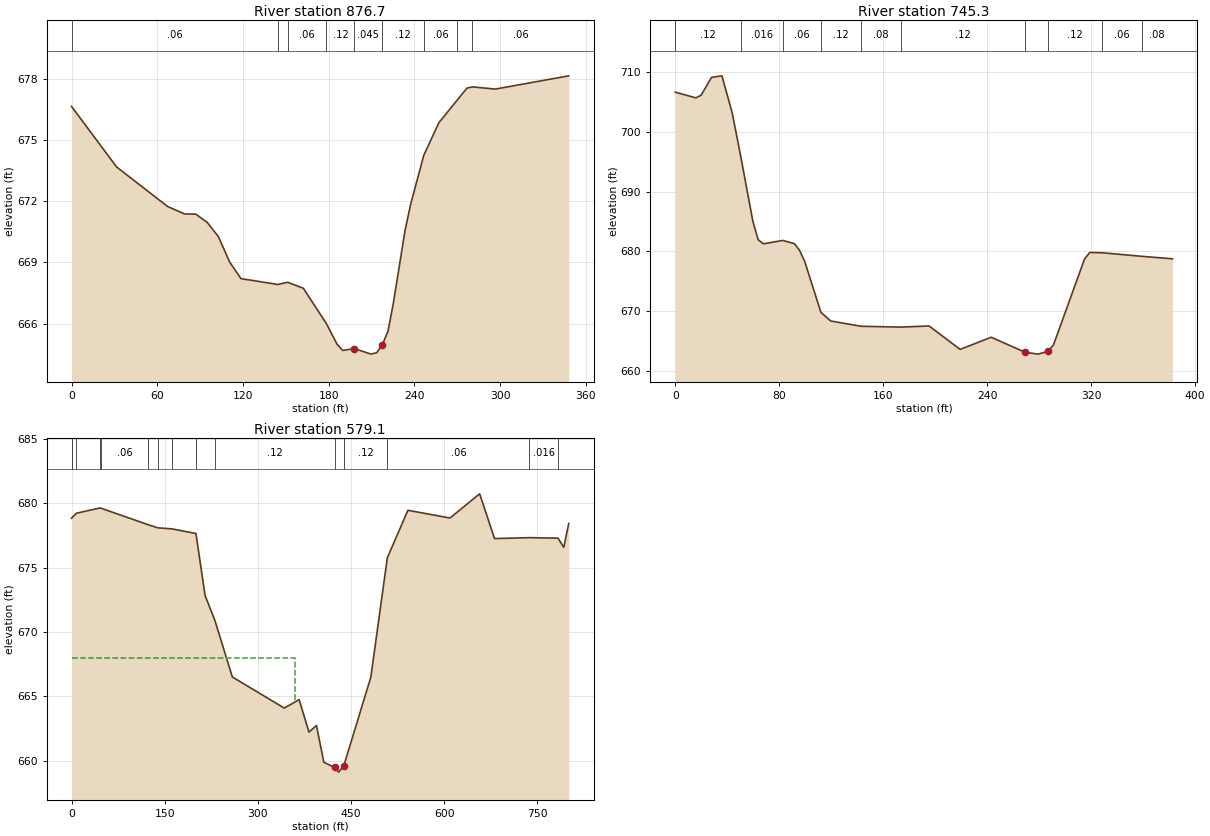
Type RM Length L Ch R = 1 ,876.7   ,159.6,131.4,105.3
XS GIS Cut Line= 2
     1772192.156      414388.268     1772493.805      414561.879
#Sta/Elev= 30
       0  676.64    31.6  673.67    67.2  671.74    79.1  671.37      87  671.36
    94.9  670.96   102.8  670.26   110.7  669.01   118.6   668.2  144.32667.9145
  151.31  668.02   162.2  667.73  178.39 665.994   185.9  664.98   189.8  664.68
     198  664.77   209.6   664.5   213.6  664.57   217.5  664.96   221.5  665.62
   225.4  667.06   233.4  670.55   237.3  671.83  246.55674.2466   257.1  675.84
  269.73676.9334   276.8  677.54  280.63677.5974   296.6  677.49     348  678.14
#Mann= 9 ,-1 , 0
       0     .06       0  144.32    .016       0  151.31     .06       0
  178.39     .12       0     198    .045       0   217.5     .12       0
  246.55     .06       0  269.73     .12       0  280.63     .06       0
Bank Sta=198,217.5
XS Rating Curve= 0 ,0
Exp/Cntr=0.3,0.1

Type RM Length L Ch R = 1 ,745.3   ,176,166.3,156.1
XS GIS Cut Line= 2
     1772151.012      414694.687     1772516.898      414582.707
#Sta/Elev= 30
       0  706.63    15.9  705.68    19.9  706.13    27.9  709.11    35.9  709.37
    43.8  703.18   50.28695.9912    59.8  684.93    63.8  681.93    67.8  681.24
   82.67681.8051    91.7  681.27    95.7  680.13    99.6   678.3  112.06669.7719
   119.6  668.32  142.95667.4335  173.83667.2932   195.3  667.49   219.2  663.56
   243.1   665.6   269.1  663.09     279  662.77     287  663.24     291   664.3
   314.9  678.68   318.9  679.79  328.27679.7451  359.16679.1439   382.6  678.73
#Mann= 10 ,-1 , 0
       0     .12       0   50.28    .016       0   82.67     .06       0
  112.06     .12       0  142.95     .08       0  173.83     .12       0
   269.1    .045       0     287     .12       0  328.27     .06       0
  359.16     .08       0
Bank Sta=269.1,287
XS Rating Curve= 0 ,0
Exp/Cntr=0.3,0.1

Type RM Length L Ch R = 1 ,579.1   ,90.8,90.3,90.9
XS GIS Cut Line= 2
      1772104.55         415055.     1772718.415      414541.263
#Sta/Elev= 30
       0  678.84     .84678.8883    7.74679.2289   46.26679.6447   46.86679.6312
  123.29678.3406   138.9678.0975   161.8 678.015  200.31677.6567     215  672.84
  230.95670.8766   258.9   666.5   342.5  664.08   366.4  664.74   382.3  662.21
   394.3  662.73   406.2  659.87   423.4  659.46   430.1   659.1   438.4   659.6
   481.9  666.49  508.43675.7667   541.6  679.46   609.3  678.86   657.1  680.74
     681  677.26  737.18677.3312   783.2677.2933   792.5  676.58   800.5  678.43
#Mann= 15 ,-1 , 0
       0     .06       0     .84     .12       0    7.74     .06       0
   46.26     .08       0   46.86     .06       0  123.29     .08       0
   138.9     .06       0   161.8    .016       0  200.31     .08       0
  230.95     .12       0   423.4    .045       0   438.4     .12       0
  508.43     .06       0  737.18    .016       0   783.2     .12       0
#XS Ineff= 2 , 0
       0  360.52     668               0
Permanent Ineff=
       F       F
Bank Sta=423.4,438.4
XS Rating Curve= 0 ,0
Exp/Cntr=0.3,0.1