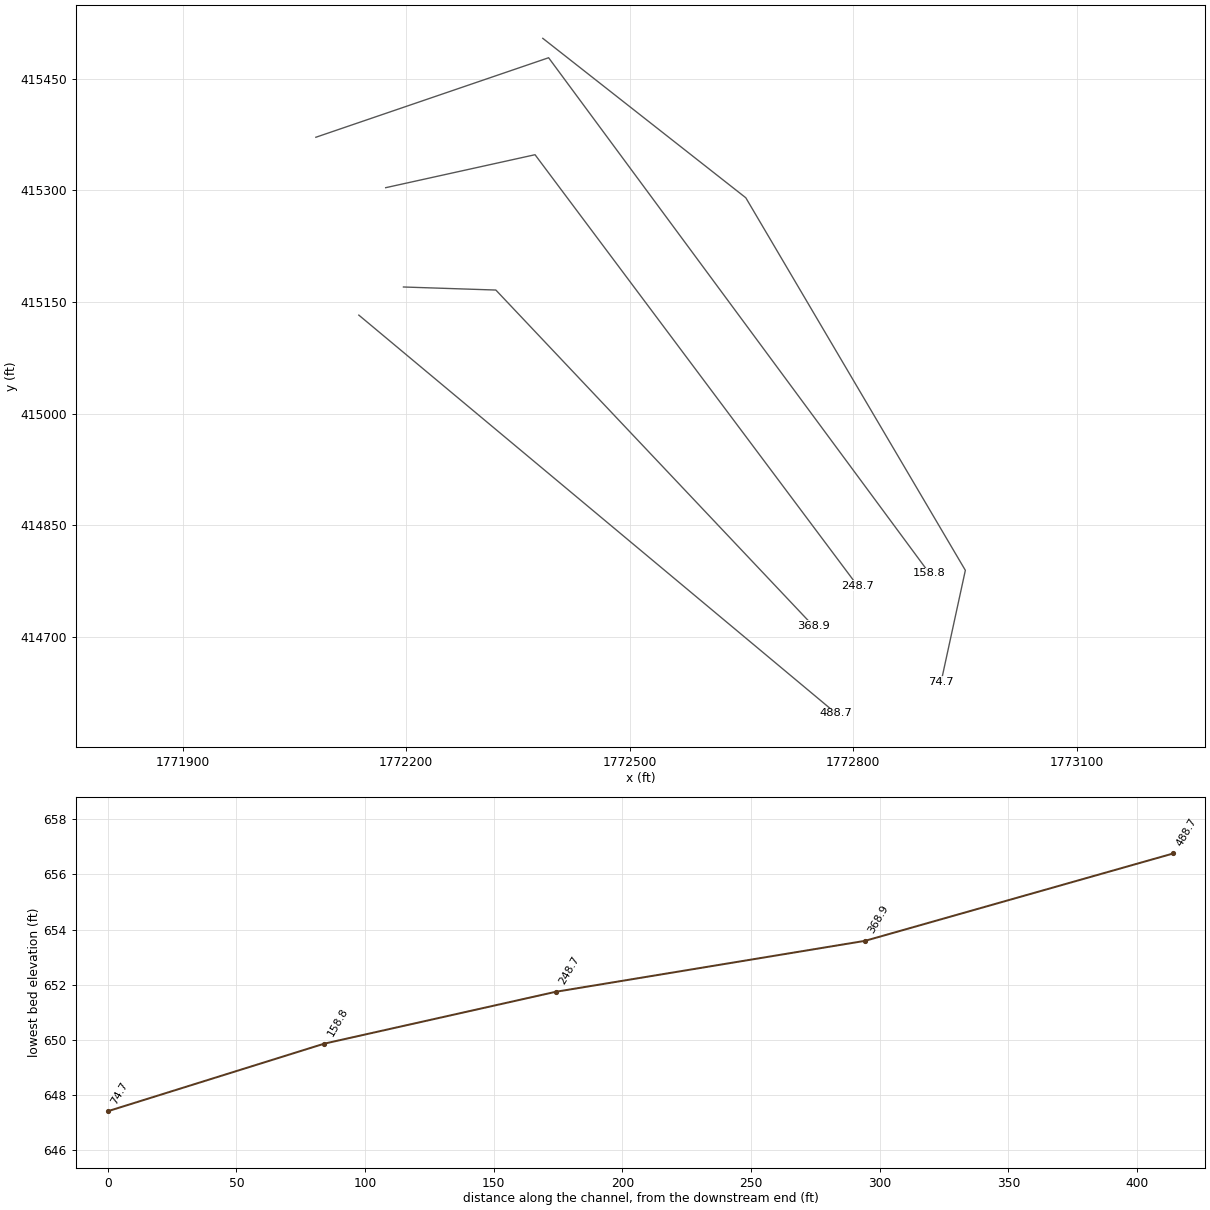
HEC-RAS study DRAWDYCK.prj: DRAWDYCK

--- DRAWDYCK.g01 (geometry) --- (continued)

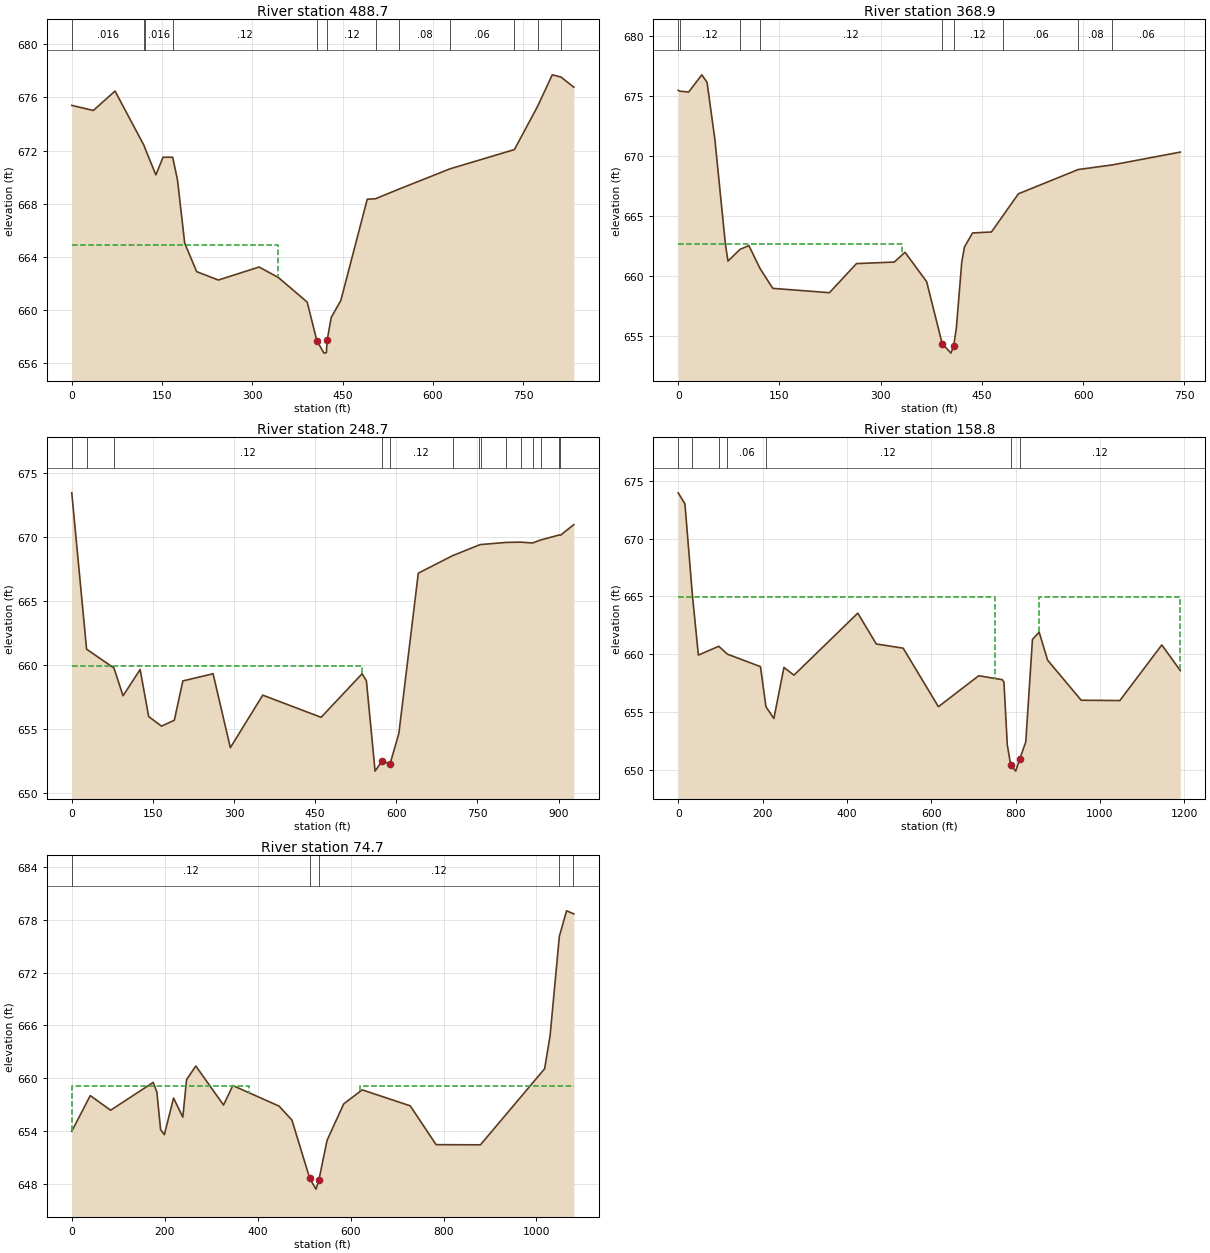
Type RM Length L Ch R = 1 ,488.7   ,121.4,119.8,117.4
XS GIS Cut Line= 2
     1772136.314      415132.381     1772777.008      414597.686
#Sta/Elev= 30
       0   675.4    35.9  675.02    71.9  676.48  120.24672.3717  121.61672.1902
   139.8  670.17   151.7   671.5  167.71671.4986   175.7   669.8   187.7  665.04
   207.6  662.89   243.6  662.26   311.4  663.24   343.4  662.45   391.3   660.6
   407.4  657.69   419.2  656.76   423.2   656.8  424.53  657.74   431.2  659.44
   447.2  660.72   491.1  668.34  504.94668.3768  543.41669.0931  628.68670.6266
  735.76672.0762  774.23675.3275   798.6   677.7  813.07677.5328   834.5  676.77
#Mann= 12 ,-1 , 0
       0    .016       0  120.24     .12       0  121.61    .016       0
  167.71     .12       0   407.4    .045       0  424.53     .12       0
  504.94     .06       0  543.41     .08       0  628.68     .06       0
  735.76     .08       0  774.23    .016       0  813.07     .08       0
#XS Ineff= 2 , 0
       0     343  664.92               0
Permanent Ineff=
       F       F
Bank Sta=407.4,424.53
XS Rating Curve= 0 ,0
Exp/Cntr=0.3,0.1

Type RM Length L Ch R = 1 ,368.9   ,122.9,120.3,117.7
XS GIS Cut Line= 3
      1772196.21      415170.142     1772320.283      415166.041
     1772746.065       414715.52
#Sta/Elev= 30
       0  675.46    2.89675.3859    15.5  675.32    34.9  676.75    42.7  676.13
    54.3  671.38    69.8   662.7    73.7  661.25   91.55662.2226   104.7  662.54
   121.1660.6447   140.1  658.98   224.1  658.62   264.1  661.04   320.1  661.17
   336.1  661.98   368.1  659.54   391.1  654.39   404.1  653.59   408.1  654.17
   412.1  655.66   420.1  661.14   424.1  662.42   436.1  663.59   464.1  663.67
  480.87665.0016   504.1  666.85  592.71668.8684  643.43669.2543     744  670.32
#Mann= 9 ,-1 , 0
       0     .08       0    2.89     .12       0   91.55    .016       0
   121.1     .12       0   391.1    .045       0   408.1     .12       0
  480.87     .06       0  592.71     .08       0  643.43     .06       0
#XS Ineff= 2 , 0
       0     332   662.7               0
Permanent Ineff=
       F       F
Bank Sta=391.1,408.1
XS Rating Curve= 0 ,0
Exp/Cntr=0.3,0.1

Type RM Length L Ch R = 1 ,248.7   ,90,89.9,89.7
XS GIS Cut Line= 3
     1772172.364      415303.461     1772372.885      415347.732
      1772805.96      414768.905
#Sta/Elev= 30
       0  673.46   27.38  661.26   78.02659.7852    94.8  657.62   126.4  659.67
   142.2     656   165.9  655.25   189.6  655.71   205.4  658.78   261.3  659.34
   293.2  653.57   353.1  657.67     461  655.94   536.8  659.34   544.8  658.78
   560.8  651.74   573.6  652.52   588.6  652.32   604.8  654.69   640.7  667.19
  704.09668.5549  753.39669.3911  756.07669.4246   802.7669.5887  829.84669.6108
     852669.5471  866.73669.7758   901.3670.1725  903.62670.1551   928.3  670.98
#Mann= 14 ,-1 , 0
       0     .12       0   27.38    .016       0   78.02     .12       0
   573.6    .045       0   588.6     .12       0  704.09     .08       0
  753.39     .12       0  756.07     .08       0   802.7     .12       0
  829.84     .08       0     852     .12       0  866.73     .08       0
   901.3     .12       0  903.62     .08       0
#XS Ineff= 2 , 0
       0     536  659.98               0
Permanent Ineff=
       F       F
Bank Sta=573.6,588.6
XS Rating Curve= 0 ,0
Exp/Cntr=0.3,0.1

Type RM Length L Ch R = 1 ,158.8   ,86.4,84.1,81.7
XS GIS Cut Line= 3
     1772078.614      415371.169     1772391.114       415477.94
     1772902.315      414785.832
#Sta/Elev= 30
       0  673.96    15.9     673   33.69665.0603    47.8  659.91   96.11 660.671
  116.67659.9883     195  658.91  208.02 655.436   226.8  654.42   250.7  658.84
   274.5  658.17   425.8  663.54   469.7  660.87   533.4  660.51     617  655.44
   712.6  658.12   768.4  657.78   772.4  657.58   780.4  652.13   788.3  650.43
   800.3  649.86   809.5  650.87   824.2  652.39   840.1  661.27     856  661.89
     876  659.47   955.6     656  1047.3  655.97  1146.8  660.79  1190.7  658.57
#Mann= 7 ,-1 , 0
       0     .12       0   33.69    .016       0   96.11     .12       0
  116.67     .06       0  208.02     .12       0   788.3    .045       0
   809.5     .12       0
#XS Ineff= 2 , 0
       0     752  664.94     856       0  664.94
Permanent Ineff=
       F       F
Bank Sta=788.3,809.5
XS Rating Curve= 0 ,0
Exp/Cntr=0.3,0.1

Type RM Length L Ch R = 1 ,74.7    ,75.3,74.7,74.1
XS GIS Cut Line= 4
     1772383.302      415503.982     1772655.845      415289.933
      1772950.62      414789.744     1772918.067      414640.004
#Sta/Elev= 30
       0  653.98    39.8  658.03    83.6  656.37   175.3  659.53   183.2  658.41
   191.2  654.15   199.2  653.59   219.1  657.75     239  655.58     247  659.84
   266.9  661.39   326.6  656.96   346.6  659.17     446  656.84   473.8  655.25
  512.15  648.62   525.5  647.41  531.83  648.46   549.4  652.96   585.2  657.09
   624.9  658.68   728.3  656.87     784  652.46   879.4  652.44  1017.5  661.08
  1029.3  664.84 1049.18676.1052  1064.7  679.01  1079.4678.6875  1080.4  678.66
#Mann= 5 ,-1 , 0
       0     .12       0  512.15    .045       0  531.83     .12       0
 1049.18     .06       0  1079.4    .016       0
#XS Ineff= 2 , 0
       0   382.3  659.11   620.8       0  659.11
Permanent Ineff=
       F       F
Bank Sta=512.15,531.83
XS Rating Curve= 0 ,0
Exp/Cntr=0.3,0.1

Chan Stop Cuts=-1
Use User Specified Reach Order=0
Composite Channel Slope=5